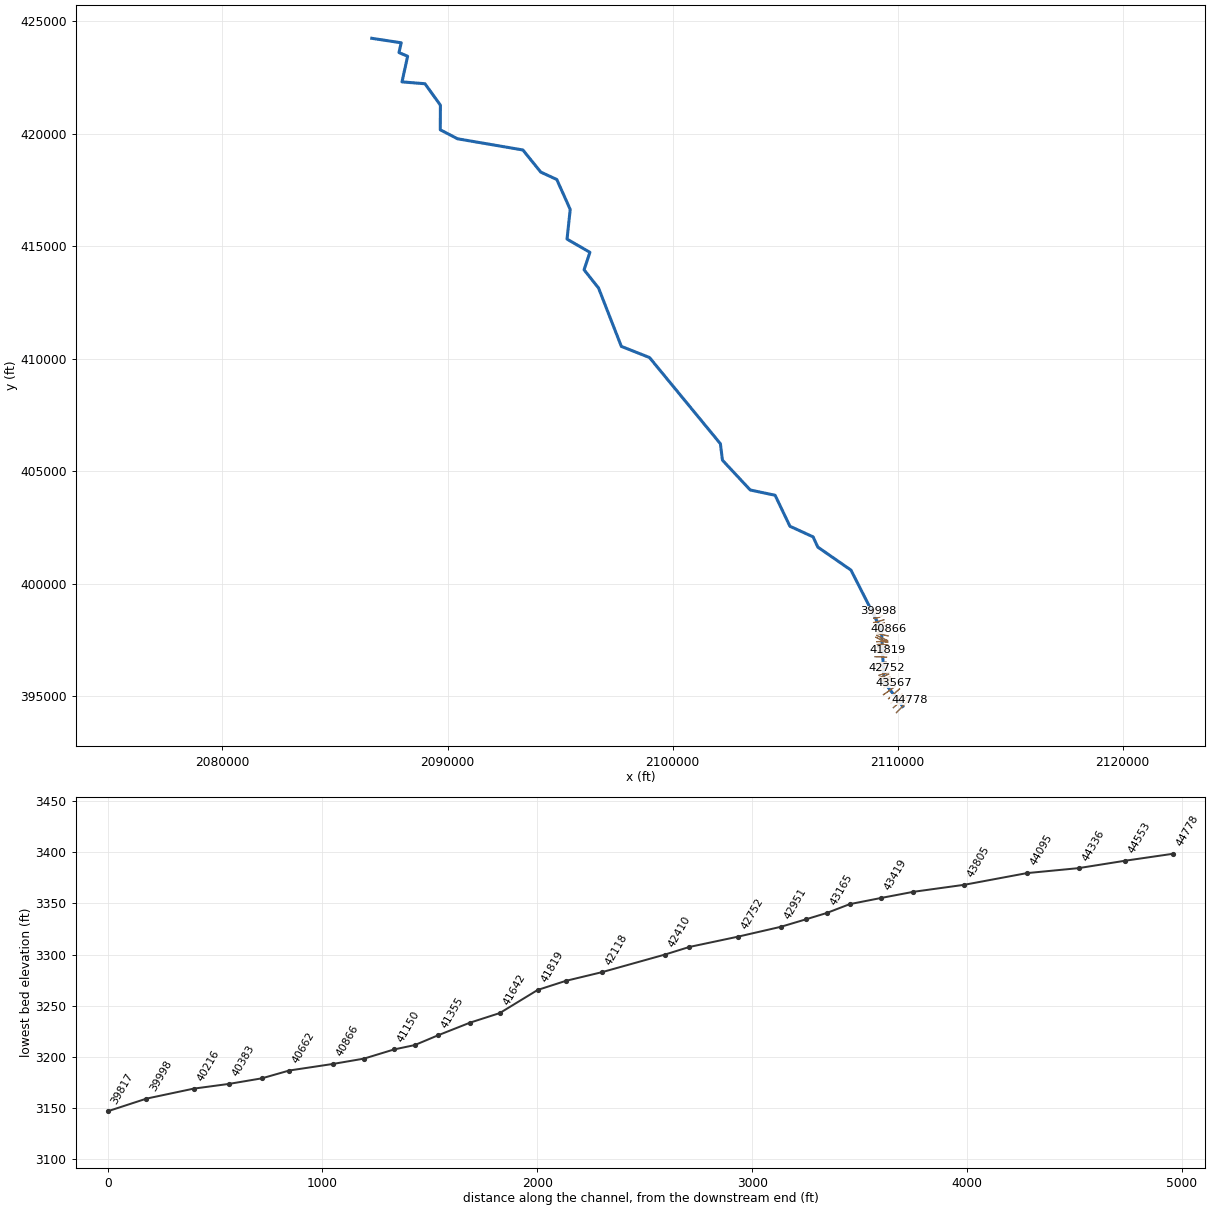
--- LAURELCK4.prj (project) ---

Proj Title=LAURELCK4
Current Plan=p01
Default Exp/Contr=0,0
English Units
Geom File=g01
Flow File=f01
Plan File=p01
BEGIN DESCRIPTION:
Stream Name- Laurel Creek 4
Flood Zone: Zone A
Greenbrier County, WV
County-Wide Study
WVDHSEM-2018-3, Flood Risk Project
HEC-RAS Version: 5.0.7
General Notes:
For the Hydrology regression was used.
END DESCRIPTION:
DSS Export Rating Curves= 0
DSS Export Rating Curve Sorted= 0
DSS Export Volume Flow Curves= 0
DXF OffsetX= 0
DXF OffsetY= 0
DXF ScaleX= 0
DXF ScaleY= 0

--- LAURELCK4.p01 (plan) ---

Plan Title=Floodplain
Program Version=5.07
Short Identifier=Floodplain
Geom File=g01
Flow File=f01
Subcritical Flow
K Sum by GR= 0
Std Step Tol= 0.01
Critical Tol= 0.01
Num of Std Step Trials= 20
Max Error Tol= 0.3
Flow Tol Ratio= 0.001
Split Flow NTrial= 30
Split Flow Tol= 0.02
Split Flow Ratio= 0.02
Log Output Level= 0
Friction Slope Method= 1
Unsteady Friction Slope Method= 2
Unsteady Bridges Friction Slope Method= 1
Parabolic Critical Depth
Global Vel Dist= 0 , 0 , 0
Global Log Level= 0
CheckData=True
Encroach Param=-1 ,0,0, 0
Computation Interval=1MIN
Output Interval=1HOUR
Instantaneous Interval=1HOUR
Mapping Interval=1HOUR
Computation Time Step Use Courant=        0
Computation Time Step Use Time Series=    0
Computation Time Step Count To Double=0
Computation Time Step Max Doubling=0
Computation Time Step Max Halving=0
Computation Time Step Residence Courant=0
Run HTab= 0
Run UNet= 0
Run Sediment= 0
Run PostProcess= 0
Run WQNet= 0
Run RASMapper= 0
UNET Theta= 1
UNET Theta Warmup= 1
UNET ZTol= 0.02
UNET ZSATol= 0.02
UNET MxIter= 20
UNET Max Iter WO Improvement= 0
UNET MaxInSteps= 0
UNET DtIC= 0
UNET DtMin= 0
UNET MaxCRTS= 20
UNET WFStab= 2
UNET SFStab= 1
UNET WFX= 1
UNET SFX= 1
UNET 1D Methodology=Finite Difference
UNET DSS MLevel= 4
UNET Pardiso=0
UNET DZMax Abort= 100
UNET Use Existing IB Tables=-1
UNET Froude Reduction=False
UNET Froude Limit= 0.8
UNET Froude Power= 4
UNET D1 Cores= 0
UNET D2 Coriolis=0
UNET D2 Cores= 0
UNET D2 Theta= 1
UNET D2 Theta Warmup= 1
UNET D2 Z Tol= 0.01
UNET D2 Volume Tol= 0.01
UNET D2 Max Iterations= 20
UNET D2 Equation= 0
UNET D2 RampUpFraction=0.1
UNET D2 TimeSlices= 1
UNET D2 BCVolumeCheck=0
UNET D1D2 MaxIter= 0
UNET D1D2 ZTol=0.01
UNET D1D2 QTol=0.1
UNET D1D2 MinQTol=1
Write IC File= 0
Write IC File at Fixed DateTime=0
Write IC File at Sim End=0
Echo Input=False
Echo Parameters=False
Echo Output=False
Write Detailed= 0
HDF Write Warmup=0
HDF Write Time Slices=0
HDF Flush=0
HDF Face Node Velocities=0
HDF Compression= 1
HDF Chunk Size= 1
HDF Spatial Parts= 1
HDF Use Max Rows=0
HDF Fixed Rows= 1
Calibration Method= 0
Calibration Iterations= 20
Calibration Max Change=0.05
Calibration Tolerance=0.2
Calibration Maximum=1.5
Calibration Minimum=0.5
Calibration Optimization Method= 1
WQ AD Non Conservative
WQ ULTIMATE=-1
WQ Max Comp Step=1HOUR
WQ Output Interval=15MIN
WQ Output Selected Increments= 0
WQ Output face flow=0
WQ Output face velocity=0
WQ Output face area=0
WQ Output face dispersion=0
WQ Output cell volume=0
WQ Output cell surface area=0
WQ Output cell continuity=0
WQ Output cumulative cell continuity=0
WQ Output face conc=0
WQ Output face dconc_dx=0
WQ Output face courant=0
WQ Output face peclet=0
WQ Output face adv mass=0
WQ Output face disp mass=0
WQ Output cell mass=0
WQ Output cell source sink temp=0
WQ Output nsm pathways=0
WQ Output nsm derived pathways=0
WQ Output MaxMinRange=-1
WQ Daily Max Min Mean=-1
WQ Daily Range=0
WQ Daily Time=0
WQ Create Restart=0
WQ Fixed Restart=0
WQ System Summary=0
WQ Write To DSS=0
WQ Use Fixed Temperature=0
Sorting and Armoring Iterations= 10
XS Update Threshold= 0.02
Bed Roughness Predictor= 0
Hydraulics Update Threshold= 0.02
Energy Slope Method= 1
Volume Change Method= 1
Sediment Retention Method= 0
XS Weighting Method= 0
Number of US Weighted Cross Sections= 1
Number of DS Weighted Cross Sections= 1
Upstream XS Weight=0
Main XS Weight=1
Downstream XS Weight=0
Number of DS XS's Weighted with US Boundary= 1
Upstream Boundary Weight= 1
Weight of XSs Associated with US Boundary= 0
Number of US XS's Weighted with DS Boundary= 1
Downstream Boundary Weight= 0.5
Weight of XSs Associated with DS Boundary= 0.5
Percentile Method= 0
Sediment Output Level= 3
Mass or Volume Output= 0
Output Increment Type= 1
Profile and TS Output Increment= 1
XS Output Flag= 0
XS Output Increment= 10
Write Gradation File= 0
Read Gradation Hotstart= 0
Write HDF5 File= 1
Write Binary Output= 1
Write DSS Sediment File= 0
SV Curve= 0
Specific Gage Flag= 0

--- LAURELCK4.f01 (steady flow) ---

Flow Title=Flow
Program Version=5.07
Number of Profiles= 6
Profile Names=f1p,f10p,f4p,f2p,f02p,f1pplus
River Rch & RM=LAURELCK4,Main            ,44778
     445     233     311     376     625     658
River Rch & RM=LAURELCK4,Main            ,42118
     759     406     537     644    1060    1120
River Rch & RM=LAURELCK4,Main            ,39388
    1020     551     724     867    1410    1510
River Rch & RM=LAURELCK4,Main            ,32375
    1540     845    1100    1310    2110    2280
River Rch & RM=LAURELCK4,Main            ,32022
    1950    1080    1400    1670    2660    2880
River Rch & RM=LAURELCK4,Main            ,30172
    2170    1210    1570    1860    2960    3210
River Rch & RM=LAURELCK4,Main            ,24871
    2540    1420    1840    2180    3450    3760
River Rch & RM=LAURELCK4,Main            ,24204
    2970    1670    2160    2550    4020    4390
River Rch & RM=LAURELCK4,Main            ,21482
    3320    1880    2420    2850    4490    4910
River Rch & RM=LAURELCK4,Main            ,20211
    3690    2100    2690    3180    4980    5460
River Rch & RM=LAURELCK4,Main            ,9743
    4100    2340    3000    3540    5530    6070
River Rch & RM=LAURELCK4,Main            ,5176
    4770    2740    3500    4120    6410    7060
Boundary for River Rch & Prof#=LAURELCK4,Main            , 1
Up Type= 0
Dn Type= 3
Dn Slope=0.004581
Boundary for River Rch & Prof#=LAURELCK4,Main            , 2
Up Type= 0
Dn Type= 3
Dn Slope=0.004581
Boundary for River Rch & Prof#=LAURELCK4,Main            , 3
Up Type= 0
Dn Type= 3
Dn Slope=0.004581
Boundary for River Rch & Prof#=LAURELCK4,Main            , 4
Up Type= 0
Dn Type= 3
Dn Slope=0.004581
Boundary for River Rch & Prof#=LAURELCK4,Main            , 5
Up Type= 0
Dn Type= 3
Dn Slope=0.004581
Boundary for River Rch & Prof#=LAURELCK4,Main            , 6
Up Type= 0
Dn Type= 3
Dn Slope=0.004581
DSS Import GetInterval= 0
DSS Import GetPeak= 0
DSS Import FillOption= 0

--- LAURELCK4.g01 (geometry) ---

Geom Title=Geometry
Program Version=5.07

River Reach=LAURELCK4       ,Main
Reach XY= 30
2110229.95705104394556.344112203 2109395.8570132395643.798958287
2109283.42876038397948.669020444 2107927.7067343400612.752603039
2106453.26217663401636.0858581962106244.92893186 402089.69682762
2105214.37325022402561.9193083642104557.15113947 403938.30795978
2103451.31772122404172.4748142812102217.15122628405497.196902364
2102126.03985995406226.9191962032098975.20659471410058.030300364
2097724.09557986410553.0302946122096712.23441464413144.002474859
2096068.90105563413955.2524927852096328.06786013414731.919246525
2095311.40125829415318.1690582782095452.65097579416636.919045448
 2094855.9845182417968.1693356932094142.65097111418296.919334367
2093350.15124381419279.0026720322090446.81781164419776.085995451
 2089679.3177062 420176.085851612089684.73436204421269.835960701
2088999.31775388422221.9190302792087977.65116203422304.419193372
2088228.90098763423443.1692124462087844.31776729423606.502547204
 2087942.6049723424041.8268077822086635.32184005424240.757926817

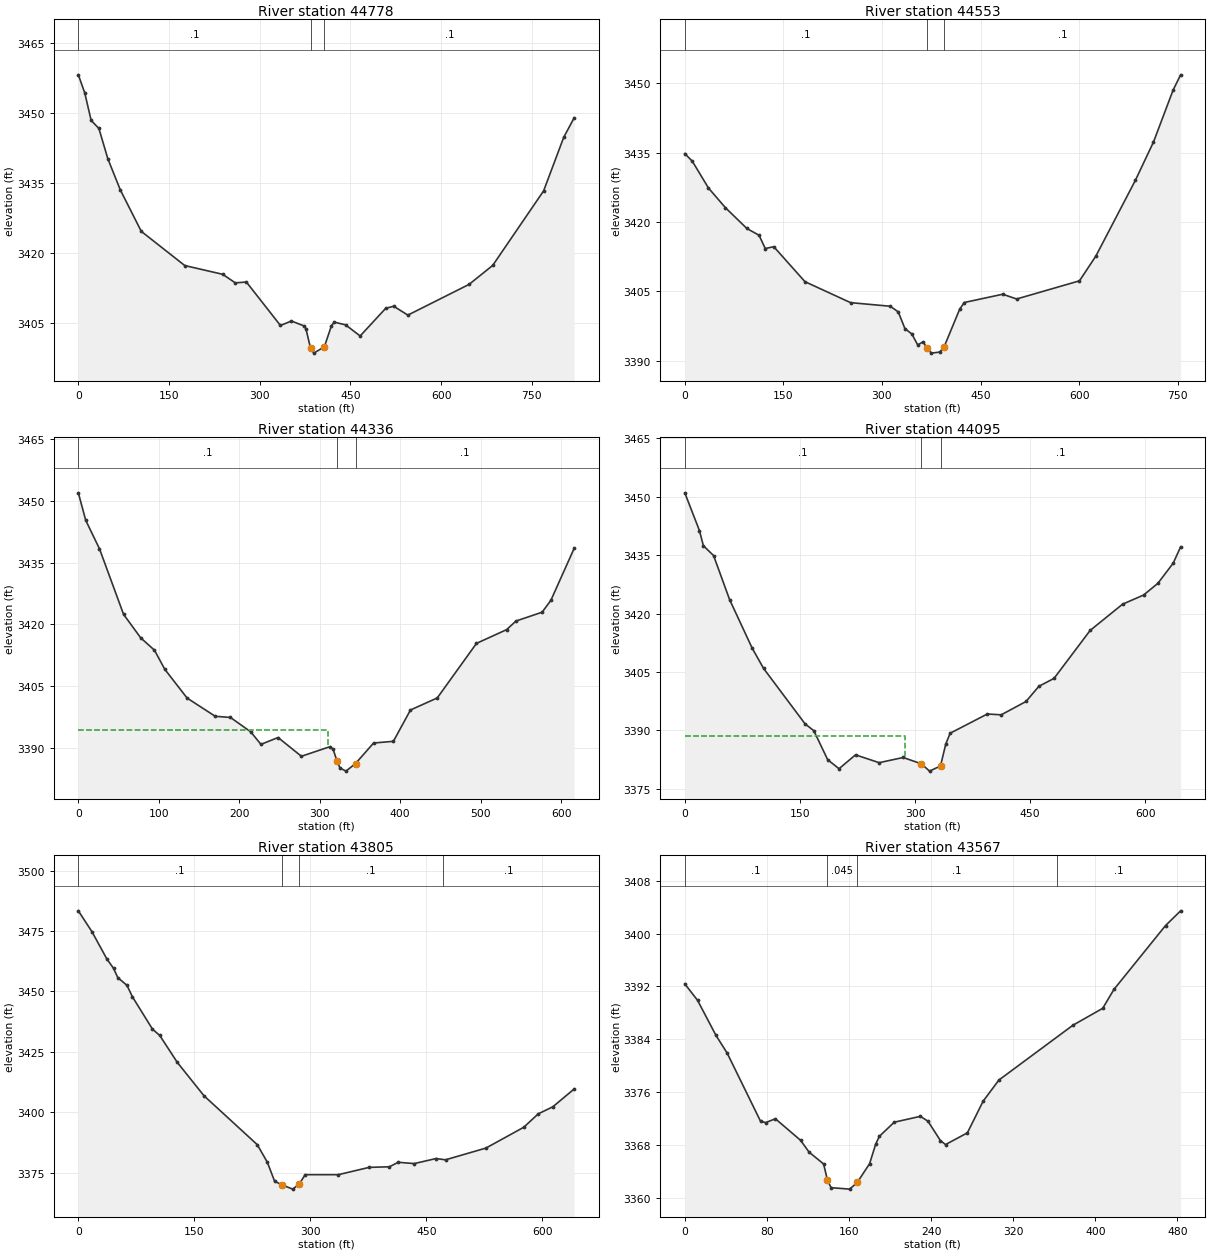
Type RM Length L Ch R = 1 ,44778   ,226.2,225.1,223.5
XS GIS Cut Line= 3
2109945.34377512394278.7032632832110220.75595397 394560.07212311
2110519.64938504394863.842184871
#Sta/Elev= 30
       0 3458.23    10.6 3454.36    21.2 3448.44      34 3446.72    48.8 3440.21
    69.3 3433.56   104.1 3424.63     176 3417.29   238.7 3415.41   259.6 3413.57
   277.9 3413.75   334.2 3404.43   352.4 3405.38   373.2 3404.33   376.4  3403.7
  383.963399.552   389.5 3398.49  406.843399.855   418.5 3404.35   423.2 3405.14
   441.9 3404.56     466 3402.17   508.2  3408.1   521.5 3408.56   544.9 3406.65
   646.2 3413.25   685.2 3417.32   769.4 3433.32   802.7 3444.83   819.9    3449
#Mann= 3 ,-1 , 0
       0      .1       0  383.96    .045       0  406.84      .1       0
Bank Sta=383.96,406.84
XS Rating Curve= 0 ,0
Exp/Cntr=0.3,0.1

Type RM Length L Ch R = 1 ,44553   ,216.3,216.8,216.8
XS GIS Cut Line= 3
2109810.62160364394503.0089170342110046.73267996394705.786398619
2110395.34385937394979.397728026
#Sta/Elev= 30
       0  3434.8    11.4 3433.16      36 3427.36    61.8  3423.1    94.4 3418.61
     113 3417.13   122.4 3414.27   135.4 3414.66   182.8  3407.1   252.2 3402.56
   312.7 3401.78   324.8 3400.55   334.9 3396.96   345.5 3395.77   354.4 3393.41
   362.7  3394.1  367.883392.849   375.2 3391.64   387.8 3391.87  394.26 3392.91
   418.2 3401.13   425.2 3402.59   483.7 3404.38   504.9 3403.35   600.5 3407.28
   625.5 3412.65   685.6 3429.03   713.1  3437.3     743 3448.55   754.4 3451.84
#Mann= 3 ,-1 , 0
       0      .1       0  367.88    .045       0  394.26      .1       0
Bank Sta=367.88,394.26
XS Rating Curve= 0 ,0
Exp/Cntr=0.3,0.1

Type RM Length L Ch R = 1 ,44336   ,239.8,240.9,240.9
XS GIS Cut Line= 3
2109709.40625489394701.2148854432109974.18492478 394921.52514036
2110190.65627661395085.589772865
#Sta/Elev= 30
       0  3451.9     9.2 3445.23    26.3 3438.32    56.2 3422.43    77.5 3416.73
    94.6 3413.73   107.4 3409.11   135.1 3402.13   170.1  3397.7     189 3397.42
   214.1 3393.95   226.9 3390.89   248.2 3392.55   277.2    3388   312.3 3390.31
   316.5 3389.75  321.483386.823   325.1 3385.16   332.6  3384.4  344.453386.246
   366.9 3391.22   391.5 3391.63   412.7 3399.23     446 3402.15   494.7 3415.38
   532.1 3418.71   543.9 3420.81   576.3 3422.95   587.2 3425.84   616.1 3438.43
#Mann= 3 ,-1 , 0
       0      .1       0  321.48    .045       0  344.45      .1       0
#XS Ineff= 2 , 0
          310.58 3394.37
Permanent Ineff=
       F       F
Bank Sta=321.48,344.45
XS Rating Curve= 0 ,0
Exp/Cntr=0.3,0.1

Type RM Length L Ch R = 1 ,44095   ,289.6,290.3,288.3
XS GIS Cut Line= 2
2109600.03147364 394901.21481353 2110081.2811673395332.464607194
#Sta/Elev= 30
       0 3450.99    19.1 3441.29    24.2 3437.41    37.5 3434.88    58.4 3423.57
    87.9 3411.07   102.7 3405.89   156.7 3391.68   168.2  3389.9   186.2 3382.47
     201 3380.15   222.5 3383.71   253.3  3381.7   284.6 3383.03  308.343381.406
     319 3379.53  333.273380.861   340.1 3386.47   345.8 3389.26   394.3  3394.2
   412.4 3393.99   444.7 3397.41   461.5 3401.32   481.2 3403.34   528.3 3415.66
   570.5 3422.39     598 3424.75   616.6 3427.76   636.6 3432.95   646.2 3437.13
#Mann= 3 ,-1 , 0
       0      .1       0  308.34    .045       0  333.27      .1       0
#XS Ineff= 2 , 0
          287.21 3388.43
Permanent Ineff=
       F       F
Bank Sta=308.34,333.27
XS Rating Curve= 0 ,0
Exp/Cntr=0.3,0.1

Type RM Length L Ch R = 1 ,43805   ,240.3,238.1,237.1
XS GIS Cut Line= 3
2109373.98960286395080.3814499532109603.15646738395239.756459281
2109897.94787255395450.173033193
#Sta/Elev= 30
       0 3483.32    17.6 3474.69    36.9  3463.4    45.6 3459.48    51.1 3455.65
    62.9  3452.5    69.9 3447.77    95.9 3434.37   105.3 3431.75     128 3420.61
   162.5  3406.8   231.4 3386.57   244.4 3379.33   253.8 3371.47  262.913369.989
   277.3 3368.16  285.663370.252   293.4 3374.14   336.2 3374.13   376.1 3377.16
   402.3 3377.41   413.8 3379.27   434.5 3378.73   462.7 3380.82   474.9 3380.29
   527.2 3385.15   576.1 3393.76   594.9 3399.32   613.7 3402.22   641.3  3409.6
#Mann= 4 ,-1 , 0
       0      .1       0  262.91    .045       0  285.66      .1       0
  471.23      .1       0
Bank Sta=262.91,285.66
XS Rating Curve= 0 ,0
Exp/Cntr=0.3,0.1

Type RM Length L Ch R = 1 ,43567   ,147.7,148.2,151.5
XS GIS Cut Line= 3
2109396.90622371 395401.214797782109587.53117055395489.756287366
2109834.40633297395606.423048779
#Sta/Elev= 30
       0 3392.37    12.4 3389.89    30.4 3384.56    41.3 3381.88    73.8 3371.56
    78.8 3371.35    88.3 3371.93   112.8 3368.67   121.1 3366.88   135.3 3365.08
  139.053362.598   142.6 3361.49   160.7 3361.27  168.15  3362.3   180.1 3365.13
     186 3368.07   189.6 3369.27   204.1 3371.41   229.6  3372.3     237 3371.56
   249.1 3368.63   254.1 3368.02   275.4  3369.8   290.8 3374.61   306.1  3377.8
   378.2  3386.1   407.3 3388.67   418.2 3391.53   468.5 3401.21   483.2 3403.44
#Mann= 4 ,-1 , 0
       0      .1       0  139.05    .045       0  168.15      .1       0
  362.37      .1       0
Bank Sta=139.05,168.15
XS Rating Curve= 0 ,0
Exp/Cntr=0.3,0.1

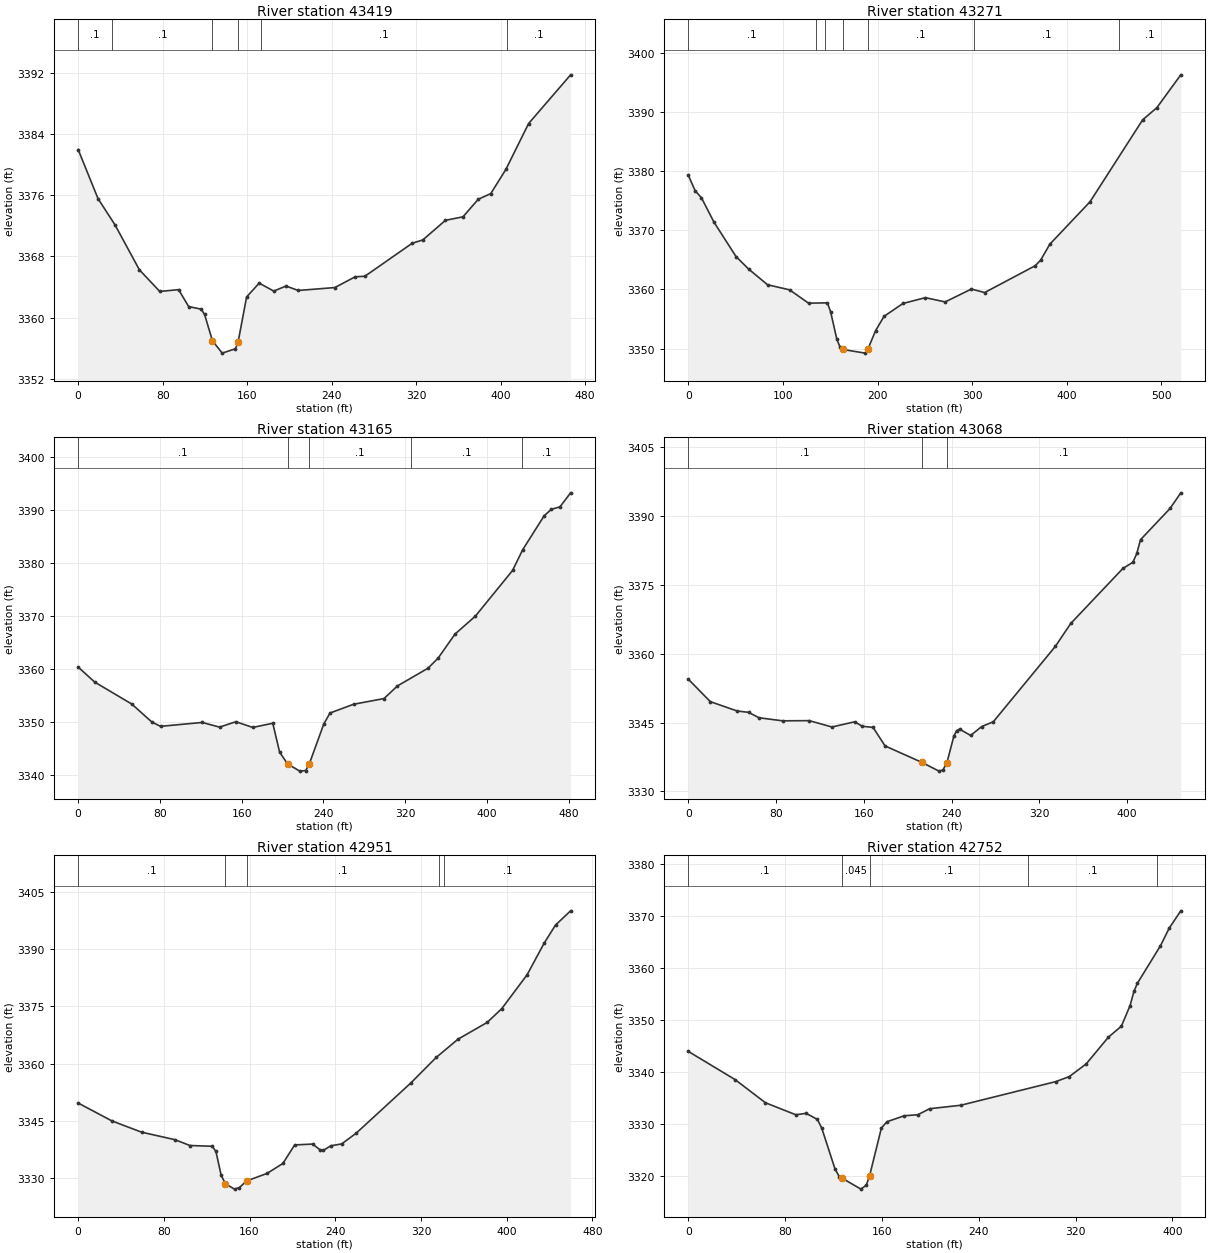
Type RM Length L Ch R = 1 ,43419   ,154,147.9,144.8
XS GIS Cut Line= 2
2109329.19802579395511.631571695 2109726.0728882395756.423076868
#Sta/Elev= 30
       0 3381.99    18.8 3375.57    34.9 3372.13      58 3366.25    77.3 3363.42
    95.1 3363.66   104.6 3361.45   116.5  3361.1   119.7 3360.41  127.173356.963
   136.4 3355.35   148.9 3355.92  151.393356.759   159.5  3362.7   171.4 3364.51
   185.2 3363.47   196.8 3364.13   208.4 3363.55     243 3363.93   262.3 3365.34
   271.5 3365.41   316.3 3369.73   326.3 3370.16   347.8 3372.73   364.4 3373.19
   378.8 3375.48   390.7 3376.23     405 3379.39   426.5 3385.39   466.3 3391.77
#Mann= 6 ,-1 , 0
       0      .1       0   32.29      .1       0  127.17    .045       0
  151.39      .1       0  173.54      .1       0  405.78      .1       0
Bank Sta=127.17,151.39
XS Rating Curve= 0 ,0
Exp/Cntr=0.3,0.1

Type RM Length L Ch R = 1 ,43271   ,110.1,106.2,106.1
XS GIS Cut Line= 3
2109204.19794771395680.3815622782109442.73979345395721.006481037
2109705.23959655 395813.71462895
#Sta/Elev= 30
       0 3379.27     7.2 3376.65    13.8 3375.49    27.1 3371.35    50.4 3365.54
    63.7 3363.43    83.7 3360.78     107 3359.92     127 3357.67   146.9 3357.72
   150.3 3356.25   156.9 3351.59   160.3 3350.25  163.143349.851   186.9 3349.23
  189.663349.877   197.8    3353   206.8 3355.44   226.8 3357.62   250.5  3358.6
   271.4 3357.88   299.2 3360.06   313.1 3359.46   366.6    3364   372.3 3364.94
     382 3367.63   424.5  3374.8   480.1 3388.64   495.1 3390.69   520.4 3396.24
#Mann= 7 ,-1 , 0
       0      .1       0  134.78      .1       0  144.82      .1       0
  163.14    .045       0  189.66      .1       0     302      .1       0
  454.83      .1       0
Bank Sta=163.14,189.66
XS Rating Curve= 0 ,0
Exp/Cntr=0.3,0.1

Type RM Length L Ch R = 1 ,43165   ,92.3,97.1,99.3
XS GIS Cut Line= 3
2109188.57297897395799.1313247832109473.98973095395819.964616448
2109667.73967153395847.048223704
#Sta/Elev= 30
       0 3360.29    16.2 3357.45    52.5  3353.3    72.1 3349.91    80.6  3349.1
   121.4 3349.83   138.3 3348.95   154.3 3349.97   170.8 3348.89   190.4 3349.68
   197.1 3344.22  204.883342.008   216.8 3340.64   222.6 3340.75     2263341.927
   240.3 3349.53   246.4 3351.61   269.5 3353.27   299.2 3354.34   312.4 3356.73
   342.2 3360.06   352.2 3361.98   368.7 3366.52   388.6  3369.9     425 3378.53
     435 3382.47   455.9 3388.85   462.8 3390.06   471.4 3390.55   481.8 3393.19
#Mann= 5 ,-1 , 0
       0      .1       0  204.88    .045       0     226      .1       0
   325.6      .1       0  434.55      .1       0
Bank Sta=204.88,226
XS Rating Curve= 0 ,0
Exp/Cntr=0.3,0.1

Type RM Length L Ch R = 1 ,43068   ,114.3,116.7,115.2
XS GIS Cut Line= 3
2109182.07660088395836.1732454452109359.15990812395894.506462112
 2109602.9097487 395991.72870861
#Sta/Elev= 30
       0 3354.44      20 3349.56    44.5 3347.52    54.9 3347.23    64.4 3346.05
      86 3345.38   110.2 3345.42   130.9 3344.04   151.6 3345.17   158.5  3344.2
   168.4 3343.95   179.3 3339.92  212.693336.354   228.5 3334.43   232.1  3334.7
  235.653336.221   242.1  3342.1   244.6 3343.23   247.2 3343.58   257.3  3342.2
   267.4 3344.13     278 3345.18   334.5 3361.57   348.6 3366.58   396.1 3378.55
   405.2  3379.9   408.8 3381.82   412.2 3384.82   439.1 3391.61   448.9 3395.02
#Mann= 3 ,-1 , 0
       0      .1       0  212.69    .045       0  235.65      .1       0
Bank Sta=212.69,235.65
XS Rating Curve= 0 ,0
Exp/Cntr=0.3,0.1

Type RM Length L Ch R = 1 ,42951   ,194.8,198.5,198
XS GIS Cut Line= 3
2109175.03133938395939.7563716172109379.19792581396010.589891359
 2109614.6147778396073.089766368
#Sta/Elev= 30
       0 3349.68    31.4 3345.01    59.2 3342.05    90.4 3340.08   104.3 3338.56
   125.2 3338.36   128.6    3337   133.5 3330.77  137.523328.513     146 3327.14
   150.5 3327.55  157.17 3329.27   176.3 3331.25   191.1 3333.86   202.1 3338.71
   218.9 3338.94   225.6 3337.47     229 3337.31   235.8 3338.48     246 3338.98
   259.6  3341.8   310.5 3354.92   334.3 3361.63   354.6  3366.4   381.8 3370.78
   395.4 3374.38   419.1 3383.26   434.9 3391.49   445.6 3396.27   459.7    3400
#Mann= 5 ,-1 , 0
       0      .1       0  137.52    .045       0  157.17      .1       0
  336.86      .1       0   341.8      .1       0
Bank Sta=137.52,157.17
XS Rating Curve= 0 ,0
Exp/Cntr=0.3,0.1

Type RM Length L Ch R = 1 ,42752   ,230.4,227.9,222.9
XS GIS Cut Line= 2
2109156.26628503396113.5667195322109528.48863772396278.010944456
#Sta/Elev= 30
       0    3344    38.6 3338.59    63.7 3334.14    88.8 3331.83    97.3 3332.11
   106.7 3330.93   110.3 3329.22   121.1 3321.48   124.7 3319.94  126.963319.664
   142.6 3317.55   147.1 3318.33  149.753320.112   159.5 3329.28   164.1 3330.49
   178.5 3331.65   189.6 3331.83   199.3 3332.99   225.1 3333.66   303.8 3338.21
   314.8 3339.17   328.7 3341.59   347.1 3346.74   357.8 3348.84     365 3352.81
   368.2 3355.53     371 3357.07   390.1 3364.29   397.3 3367.66   406.9    3371
#Mann= 5 ,-1 , 0
       0      .1       0  126.96    .045       0  149.75      .1       0
  280.57      .1       0  387.03      .1       0
Bank Sta=126.96,149.75
XS Rating Curve= 0 ,0
Exp/Cntr=0.3,0.1

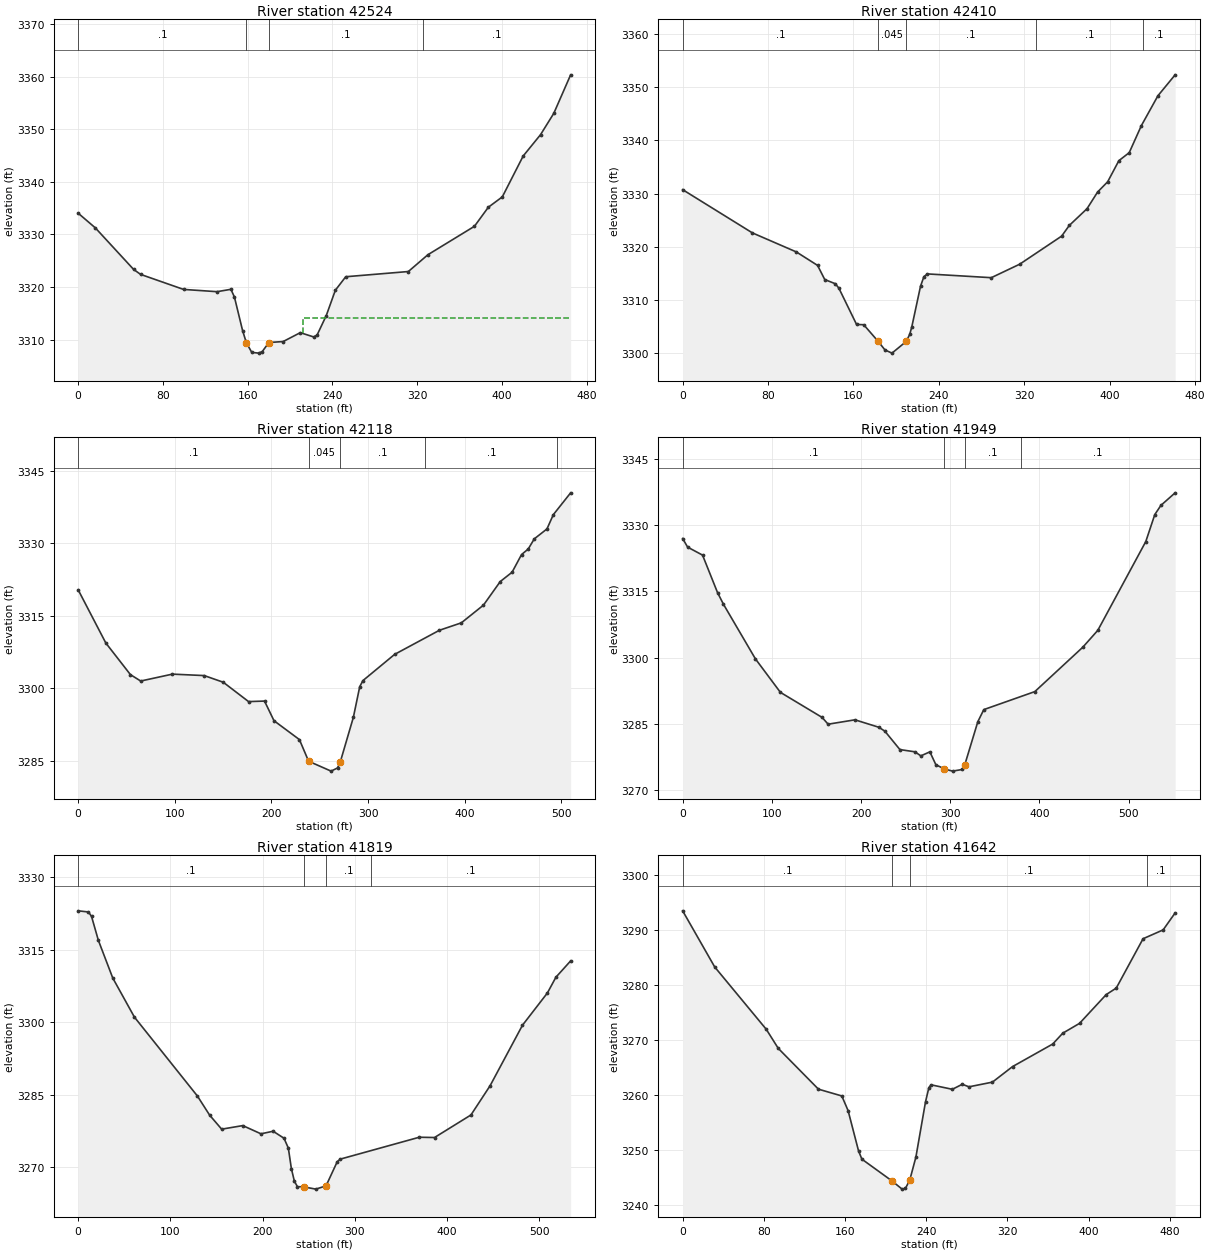
Type RM Length L Ch R = 1 ,42524   ,111.4,114.8,115.8
XS GIS Cut Line= 2
 2109027.7849147 396368.38149862 2109492.2291958 396388.38145861
#Sta/Elev= 30
       0 3334.03    16.2 3331.24    52.3 3323.35    58.9  3322.4    99.5 3319.54
   131.1 3319.11   144.2 3319.56   147.5  3318.1   155.2 3311.73  158.823309.376
   163.9 3307.57   170.5 3307.43   173.8 3307.73  180.063309.448   193.5 3309.63
   209.7 3311.32   222.3 3310.51   225.5 3310.85   234.2 3314.56   242.8 3319.39
   252.6 3321.95   311.7 3322.94   330.2 3326.14   374.1 3331.54   387.2 3335.16
   400.4 3337.13   420.1  3344.9   436.5 3348.96     449 3353.01   464.9 3360.33
#Mann= 4 ,-1 , 0
       0      .1       0  158.82    .045       0  180.06      .1       0
  325.37      .1       0
#XS Ineff= 1 ,-1
  211.94  464.87 3314.07
Permanent Ineff=
       F
Bank Sta=158.82,180.06
XS Rating Curve= 0 ,0
Exp/Cntr=0.3,0.1

Type RM Length L Ch R = 1 ,42410   ,291.9,291.6,288.1
XS GIS Cut Line= 2
 2109027.2813068 396454.405604782109483.11471272396525.239124537
#Sta/Elev= 30
       0 3330.73    65.3 3322.59   106.5    3319   126.4 3316.46   133.1  3313.8
     143 3313.01   146.3 3312.19   162.9 3305.34   169.6 3305.29  183.213302.137
   189.5 3300.54   196.1 3299.94  209.393302.137   212.7 3303.47   214.7 3304.94
   222.8 3312.53     226 3314.35   229.3 3314.86   289.1 3314.15   315.7 3316.69
     355 3321.98   362.2    3324   378.8 3327.15   388.7 3330.29   398.1 3332.21
   408.6 3336.19   418.3  3337.7   429.7  3342.8   445.2 3348.42   461.3 3352.36
#Mann= 5 ,-1 , 0
       0      .1       0  183.21    .045       0  209.39      .1       0
  331.17      .1       0  430.91      .1       0
Bank Sta=183.21,209.39
XS Rating Curve= 0 ,0
Exp/Cntr=0.3,0.1

Type RM Length L Ch R = 1 ,42118   ,171.8,168.6,166.3
XS GIS Cut Line= 2
2108998.98280695 396767.36593686 2109508.0103322396745.838092789
#Sta/Elev= 30
       0 3320.39    28.6 3309.38    54.1 3302.82    64.7  3301.5    97.5 3302.93
   130.4 3302.63   150.1 3301.25   176.3 3297.24   192.8 3297.35   202.6 3293.28
   228.9 3289.37  238.41 3284.89   261.7 3282.84   268.3  3283.5  271.073284.667
   284.7 3293.97   291.3 3300.33   294.6 3301.59   327.4 3307.02   373.7 3312.01
   396.4 3313.55   419.3 3317.22   436.7 3322.11   448.9 3324.03   458.7 3327.69
   465.6 3328.84   471.9 3330.95     485    3333   491.6 3335.96   509.5 3340.48
#Mann= 5 ,-1 , 0
       0      .1       0  238.41    .045       0  271.07      .1       0
   359.2      .1       0  495.64      .1       0
Bank Sta=238.41,271.07
XS Rating Curve= 0 ,0
Exp/Cntr=0.3,0.1

Type RM Length L Ch R = 1 ,41949   ,128.6,130.6,135
XS GIS Cut Line= 3
2108989.26038545396983.3379458642109199.67728746396939.588033363
2109528.84395197396865.976960123
#Sta/Elev= 30
       0 3326.92     5.6 3324.97    22.3 3323.17    39.1  3314.7    45.8 3312.04
    81.6 3299.71   109.6 3292.14   156.4 3286.47   163.1 3284.94   193.2 3285.93
   220.1 3284.24   226.8 3283.35   243.6  3279.2   260.4  3278.7   267.1 3277.78
   277.2 3278.69   283.9 3275.79  293.513274.812   302.7 3274.33   313.7 3274.71
  316.433275.826     331 3285.52   337.7 3288.24   394.9 3292.31   448.7 3302.35
   465.5 3306.16   519.3 3326.23   529.4 3332.33   536.2  3334.4   552.2 3337.25
#Mann= 4 ,-1 , 0
       0      .1       0  293.51    .045       0  316.43      .1       0
  379.12      .1       0
Bank Sta=293.51,316.43
XS Rating Curve= 0 ,0
Exp/Cntr=0.3,0.1

Type RM Length L Ch R = 1 ,41819   ,175.4,176.8,176
XS GIS Cut Line= 4
2109003.18775433397027.7764966832109213.41168279397026.543410067
 2109316.0411732397040.1004090272109535.60943369397057.744636389
#Sta/Elev= 30
       0 3323.09    11.2 3322.85    14.5 3321.93    21.9 3316.98    37.5 3309.19
      61 3301.09   129.3 3284.76   142.6 3280.79   155.6  3277.9   178.5 3278.64
   198.2 3276.94   211.4 3277.47   223.2 3276.02   227.9 3273.98   231.2 3269.72
   234.5 3267.09   237.8    3266   244.5 3265.96   257.7 3265.49  268.783266.168
   280.9 3271.16   284.2  3271.7   369.9 3276.23   386.4 3276.17   425.9 3280.84
   446.6 3286.87   481.8 3299.42   508.8 3306.09     518 3309.34     534 3312.73
#Mann= 4 ,-1 , 0
       0      .1       0   244.5    .045       0  268.78      .1       0
  317.86      .1       0
Bank Sta=244.5,268.78
XS Rating Curve= 0 ,0
Exp/Cntr=0.3,0.1

Type RM Length L Ch R = 1 ,41642   ,138,138.5,137.4
XS GIS Cut Line= 2
 2109081.4363822397164.3103529512109564.21428806397212.643589616
#Sta/Elev= 30
       0 3293.42    31.6 3283.22    82.4  3271.9    94.2 3268.44   133.8 3261.03
   156.8  3259.8     163 3257.14   173.3 3249.82   176.6 3248.32   206.3 3244.36
   216.2 3242.88   219.5 3243.01   223.8 3244.55   229.8  3248.7   239.3 3258.76
   242.6 3261.32   244.8 3261.82   265.7 3261.01   275.5 3261.92   282.1 3261.46
   305.2 3262.31     325 3265.13   364.6 3269.23   374.5  3271.2     391 3272.98
   417.3 3278.21   427.2 3279.39   453.6 3288.35   473.4 3289.96   485.2 3293.04
#Mann= 4 ,-1 , 0
       0      .1       0   206.3    .045       0   223.8      .1       0
  457.25      .1       0
Bank Sta=206.3,223.8
XS Rating Curve= 0 ,0
Exp/Cntr=0.3,0.1

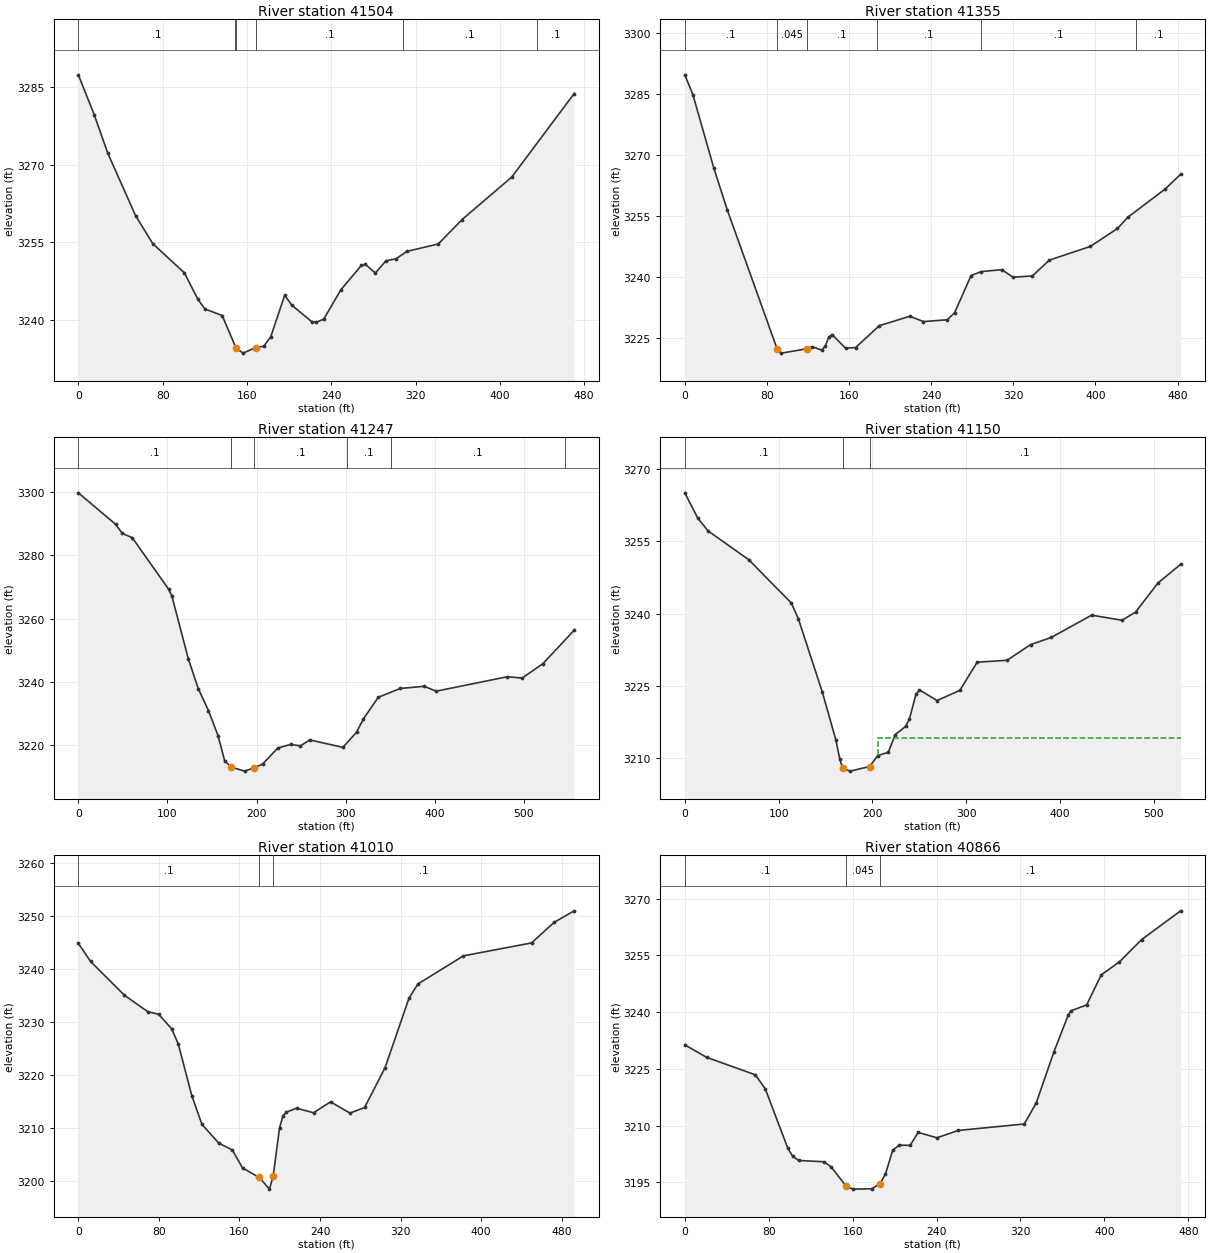
Type RM Length L Ch R = 1 ,41504   ,153.8,148.2,148.6
XS GIS Cut Line= 3
2109098.10301554397304.3104010372109294.76961696397319.865816116
2109565.32517821397281.532559454
#Sta/Elev= 30
       0 3287.43      15 3279.74    27.9 3272.27    54.3 3260.16    70.7 3254.71
   100.6 3249.08   113.5 3243.93   120.1 3242.08   136.5  3240.8   149.7 3234.49
   156.3 3233.52   168.2 3234.58     176 3234.87   182.6 3236.69   195.8 3244.73
   202.7 3242.78   221.3 3239.64   225.9 3239.48   232.9 3240.12   249.1 3245.78
   268.7 3250.55   272.4 3250.71   281.9 3249.04   291.9 3251.41   301.4 3251.79
   311.8 3253.23   341.6 3254.67   364.1 3259.39   411.2 3267.61   470.5  3283.8
#Mann= 6 ,-1 , 0
       0      .1       0  149.01      .1       0   149.7    .045       0
   168.2      .1       0  308.27      .1       0  435.28      .1       0
Bank Sta=149.7,168.2
XS Rating Curve= 0 ,0
Exp/Cntr=0.3,0.1

Type RM Length L Ch R = 1 ,41355   ,117.6,108.7,102.6
XS GIS Cut Line= 3
2109078.10305554397430.4213692842109278.65875679397445.421339288
2109557.54763472397404.310201034
#Sta/Elev= 30
       0 3289.64     7.9 3284.75    28.2 3266.78    41.5 3256.35   89.963222.258
      94 3221.23   119.5 3222.32   124.2 3222.81   133.5 3221.97   136.8 3222.93
   140.1  3225.1   143.4  3225.8   156.6 3222.46   166.4  3222.6   189.5 3227.98
   219.2 3230.29   232.5 3228.99   255.7 3229.43   262.8 3231.16   278.9 3240.31
   288.9 3241.28   308.8 3241.74   319.8  3239.9   338.6  3240.2   355.2  3244.1
     395 3247.45   421.5 3251.87   431.5 3254.61   467.9 3261.56     483  3265.2
#Mann= 6 ,-1 , 0
       0      .1       0   89.96    .045       0   119.5      .1       0
  187.15      .1       0  288.09      .1       0  439.55      .1       0
Bank Sta=89.96,119.5
XS Rating Curve= 0 ,0
Exp/Cntr=0.3,0.1

Type RM Length L Ch R = 1 ,41247   ,96.3,96.7,96.3
XS GIS Cut Line= 4
2109036.43647221397629.8658522812109252.54758856397515.976972446
 2109373.1031217397472.0879526142109554.21430805397440.976794362
#Sta/Elev= 30
       0 3299.83    41.9 3289.84    49.3 3286.98    60.4 3285.64   101.2 3269.33
   104.9 3267.19   123.4 3247.23   134.6 3237.78     146 3230.84   156.8 3222.85
   164.2  3214.9   171.7 3212.94   186.5 3211.65     197 3212.69   206.7 3213.88
   223.7 3218.96   238.2 3220.11   249.2 3219.66   259.7 3221.54   296.8 3219.18
   312.1 3223.97   319.8 3228.17   336.5 3235.04     361 3237.84   388.1 3238.53
   401.4 3236.98   481.3 3241.56     498 3241.14   521.3 3245.71   556.3 3256.29
#Mann= 6 ,-1 , 0
       0      .1       0   171.7    .045       0     197      .1       0
  301.56      .1       0  351.19      .1       0  546.08      .1       0
Bank Sta=171.7,197
XS Rating Curve= 0 ,0
Exp/Cntr=0.3,0.1

Type RM Length L Ch R = 1 ,41150   ,136.5,139.6,142.8
XS GIS Cut Line= 3
2109077.54761046397714.3102371992109295.88083521397601.532575622
2109553.65853488397484.865814194
#Sta/Elev= 30
       0 3265.07    13.9  3259.8    24.9 3257.16    68.3 3251.19   113.6 3242.22
     121    3239   146.7 3223.72   161.2 3213.76   165.3 3209.81   168.4 3207.97
   176.1 3207.37     197 3208.32   205.9 3210.61     217 3211.27   224.3 3214.92
   235.4 3216.63   239.4 3218.12   246.5 3223.27   250.1 3224.22     269 3222.01
   293.3 3224.11   311.7 3229.95   343.7 3230.36   368.9 3233.62   390.7 3235.08
   433.7  3239.7   466.2 3238.66   480.6 3240.33   504.5 3246.37   528.7 3250.25
#Mann= 3 ,-1 , 0
       0      .1       0   168.4    .045       0     197      .1       0
#XS Ineff= 2 , 0
                          206.45         3214.33
Permanent Ineff=
       F       F
Bank Sta=168.4,197
XS Rating Curve= 0 ,0
Exp/Cntr=0.3,0.1

Type RM Length L Ch R = 1 ,41010   ,136.2,144.4,151.4
XS GIS Cut Line= 3
2109100.88089713397798.1991770272109306.99203345397755.421375453
 2109580.3251482397686.532405615
#Sta/Elev= 30
       0 3244.87    12.2 3241.43    45.7 3235.07    68.7 3231.98    79.8 3231.44
    92.6 3228.74    99.2 3225.88   112.7 3216.08   122.8 3210.65   139.5 3207.11
   152.9 3205.84   163.1 3202.42   179.7 3200.63   189.8 3198.43   193.6    3201
   199.8 3209.98   203.2 3212.26   206.6 3212.97   216.7 3213.72   233.6 3212.86
   250.5 3214.92   269.7 3212.79   284.3 3213.85   304.6 3221.36   328.3 3234.47
   337.2 3237.18   382.5  3242.5   450.1 3244.94   472.4 3248.81   492.4    3251
#Mann= 3 ,-1 , 0
       0      .1       0   179.7    .045       0   193.6      .1       0
Bank Sta=179.7,193.6
XS Rating Curve= 0 ,0
Exp/Cntr=0.3,0.1

Type RM Length L Ch R = 1 ,40866   ,198.4,203.7,201.4
XS GIS Cut Line= 3
2109134.21416378397850.4211854492109335.32531011 397915.42138353
2109580.88092136398004.865758449
#Sta/Elev= 30
       0 3231.36    20.9 3228.05    67.2 3223.45    76.7 3219.76    98.2 3204.04
   102.8 3201.92   108.6 3200.81   132.7 3200.46   139.6 3199.08   153.4 3194.17
   160.1 3193.23   178.4 3193.33   186.1 3194.65   191.3 3197.21   198.2  3203.5
   204.4 3204.86   214.8 3204.79   222.5 3208.22   240.4  3206.8   260.8 3208.74
   323.7 3210.45   335.1 3216.05   351.7 3229.36   365.6 3239.29   368.3 3240.38
   383.1 3241.92   397.1 3249.88   414.1 3253.23   435.5 3259.17   472.7 3266.78
#Mann= 3 ,-1 , 0
       0      .1       0   153.4    .045       0   186.1      .1       0
Bank Sta=153.4,186.1
XS Rating Curve= 0 ,0
Exp/Cntr=0.3,0.1

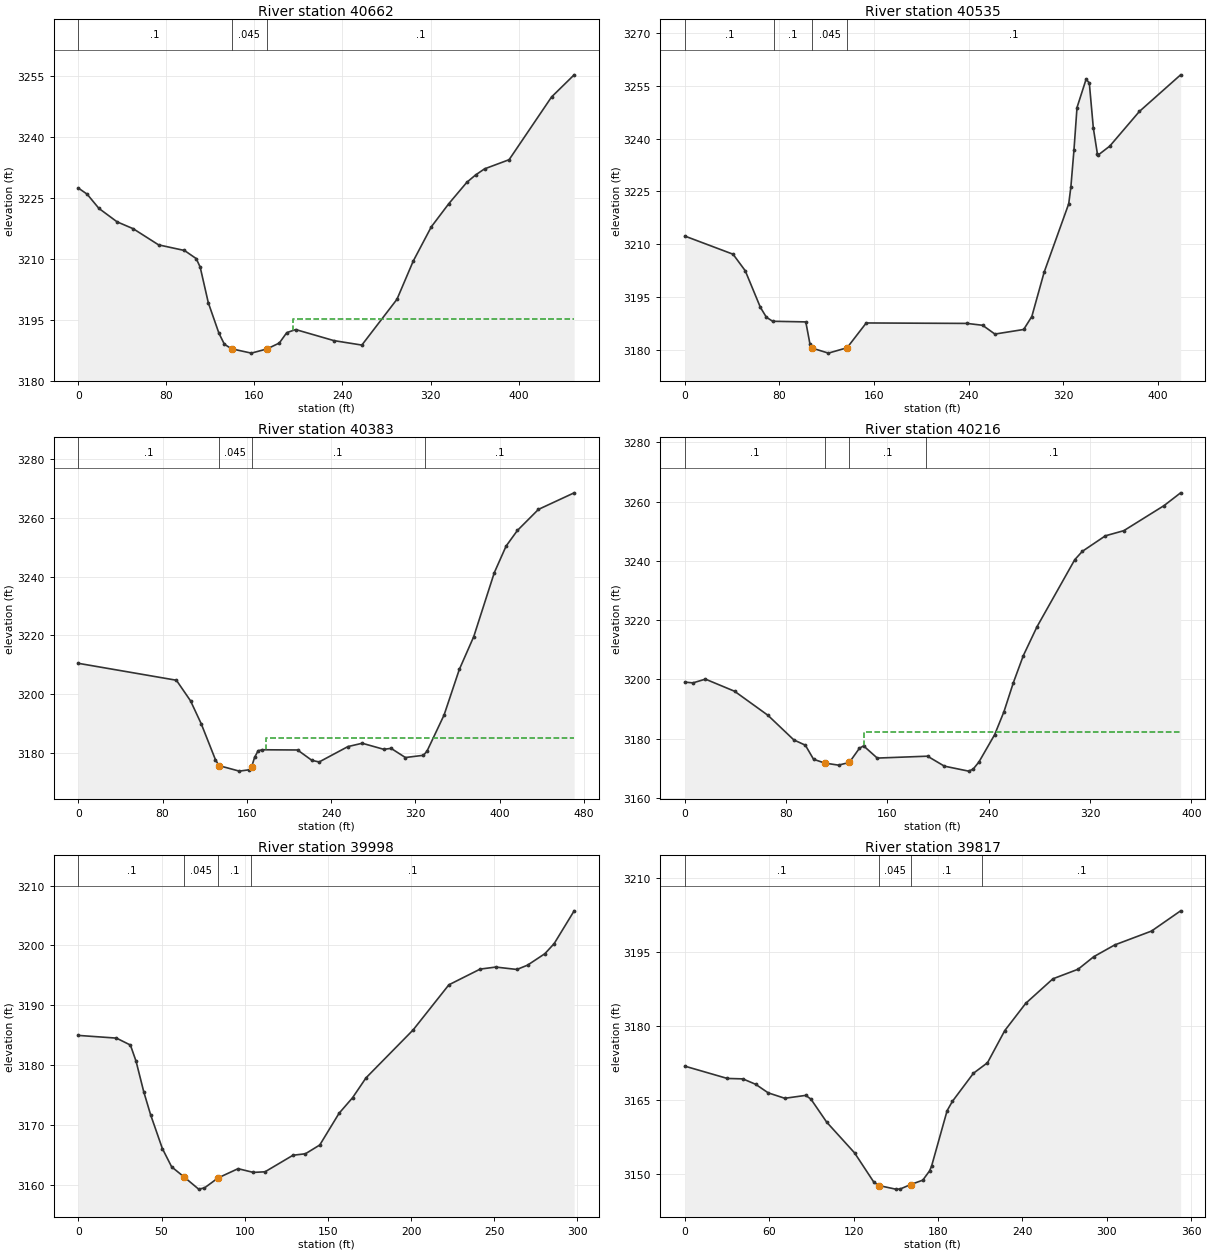
Type RM Length L Ch R = 1 ,40662   ,128.4,127.5,126.7
XS GIS Cut Line= 3
2109037.54736239397993.7545602022109215.32522205398070.976846695
2109449.76963505398175.421191618
#Sta/Elev= 30
       0 3227.38       8 3225.88    18.7 3222.38    35.2 3219.08    49.9 3217.38
    72.9 3213.42    96.4 3212.04   107.1 3210.05   110.7 3207.96   118.1 3199.19
   127.7 3191.74   132.7 3188.99   139.3 3187.87   157.2 3186.81  171.433187.844
   182.6 3189.29   189.4 3191.85   197.5  3192.6   232.3 3189.88   257.6 3188.79
   289.5 3200.04   304.3 3209.44   320.7 3217.85   336.6 3223.54     353  3228.8
     361 3230.61   369.1  3232.1   391.4 3234.35     430 3249.78   450.5 3255.21
#Mann= 3 ,-1 , 0
       0      .1       0   139.3    .045       0  171.43      .1       0
#XS Ineff= 2 , 0
                          194.68         3195.18
Permanent Ineff=
       F       F
Bank Sta=139.3,171.43
XS Rating Curve= 0 ,0
Exp/Cntr=0.3,0.1

Type RM Length L Ch R = 1 ,40535   ,153.5,151.9,150.1
XS GIS Cut Line= 3
2109013.47359163398130.2362426222109167.36239147398186.347350866
2109409.02890289398269.125072449
#Sta/Elev= 30
       0 3212.36    40.8 3207.21    51.1 3202.53    63.9 3192.16      69 3189.34
    74.3 3188.21   102.3 3188.03   105.8  3181.8   107.4 3180.63   121.4 3179.18
   137.2  3180.7   153.4 3187.73   238.6  3187.6   251.8 3187.07   262.2 3184.58
   286.5 3185.88   293.4 3189.56   303.8  3202.1   324.6 3221.52   326.4 3226.23
     329 3236.63   331.6 3248.78   339.3 3256.82     342 3255.72   345.4 3242.98
   348.9  3235.5   349.7 3235.37   359.3 3237.85   384.3 3247.66   419.2 3258.05
#Mann= 4 ,-1 , 0
       0      .1       0   75.43      .1       0   107.4    .045       0
   137.2      .1       0
Bank Sta=107.4,137.2
XS Rating Curve= 0 ,0
Exp/Cntr=0.3,0.1

Type RM Length L Ch R = 1 ,40383   ,168.8,166.3,164
XS GIS Cut Line= 3
2108936.99211729398281.5325279532109119.76963887398325.421219692
2109391.43641838398403.754724443
#Sta/Elev= 30
       0 3210.47    93.1 3204.71   106.5 3197.71   116.7 3189.86   130.2 3177.63
   133.6 3175.64   152.8 3173.77   162.4 3174.24   164.5 3175.19   167.3 3178.43
   170.7 3180.72   174.6 3181.04   208.1 3180.97   221.7 3177.44   228.6 3176.89
   255.9 3182.12   269.5 3183.26     290 3181.19   296.9 3181.52   310.5  3178.4
   327.6 3179.16     331 3180.57   347.2 3192.86   361.7 3208.41   375.4 3219.58
   394.9 3241.34   406.1 3250.39   416.8 3255.69   436.8 3262.87   470.7 3268.51
#Mann= 4 ,-1 , 0
       0      .1       0   133.6    .045       0   164.5      .1       0
  328.91      .1       0
#XS Ineff= 2 , 0
                          178.55         3185.03
Permanent Ineff=
       F       F
Bank Sta=133.6,164.5
XS Rating Curve= 0 ,0
Exp/Cntr=0.3,0.1

Type RM Length L Ch R = 1 ,40216   ,210.6,218.9,222.4
XS GIS Cut Line= 3
 2108942.3621853398473.0141003582109082.91800654398480.791643858
2109311.25121129398584.680543706
#Sta/Elev= 30
       0 3199.11     6.4 3198.85    16.3 3200.11    39.3 3196.03    65.6 3187.94
    86.1 3179.62    95.2 3177.84   101.7 3173.09   110.5 3171.81   121.4 3171.11
  129.963172.022   137.9 3176.79   141.2 3177.61     152 3173.49   191.7 3174.13
     205 3170.77   224.1 3169.09   227.7 3169.75   232.3 3172.17   244.7 3181.37
   252.1 3189.17   259.5 3198.93   267.4 3208.08   278.2  3217.8     308  3240.4
     314 3243.22   332.2 3248.45   346.7 3250.17   378.5 3258.63   391.6 3262.94
#Mann= 4 ,-1 , 0
       0      .1       0   110.5    .045       0  129.96      .1       0
  190.56      .1       0
#XS Ineff= 2 , 0
                          141.26         3182.16
Permanent Ineff=
       F       F
Bank Sta=110.5,129.96
XS Rating Curve= 0 ,0
Exp/Cntr=0.3,0.1

Type RM Length L Ch R = 1 ,39998   ,181.5,180.8,179
XS GIS Cut Line= 2
2108920.14011687398614.6804836992109161.80662829398789.125016704
#Sta/Elev= 30
       0    3185    22.9 3184.55    31.3 3183.39    34.7 3180.69    39.3 3175.62
    43.4  3171.8    50.5 3166.13    56.1 3163.07    63.7 3161.36    72.3 3159.36
    75.8 3159.56      84 3161.23      96 3162.77   105.2 3162.15   112.2 3162.25
     129 3165.01   136.5 3165.26   145.1 3166.72   156.7 3172.01   164.8  3174.6
   172.9 3177.92   201.2 3185.91   222.7 3193.44   241.5 3196.06   250.9  3196.4
   263.6    3196     270 3196.72   280.4 3198.63     286 3200.32     298 3205.78
#Mann= 4 ,-1 , 0
       0      .1       0    63.7    .045       0      84      .1       0
  103.52      .1       0
Bank Sta=63.7,84
XS Rating Curve= 0 ,0
Exp/Cntr=0.3,0.1

Type RM Length L Ch R = 1 ,39817   ,149.7,156.2,160.4
XS GIS Cut Line= 2
2108774.58463371398746.9029882852109085.14011496398913.569649696
#Sta/Elev= 30
       0  3171.9    30.2 3169.41    41.3 3169.32    50.4 3168.22    59.3 3166.49
    71.1 3165.39      86 3165.98    89.7 3165.21   100.9 3160.55   120.7 3154.33
   134.4  3148.4   138.1 3147.71   149.8 3146.99     153    3147   160.5 3147.91
   169.2 3148.81     174 3150.68   175.4  3151.6   186.5 3162.89   190.3 3164.79
   205.2 3170.46   215.2 3172.59   227.5 3179.11   242.4 3184.63   261.7 3189.59
   279.6 3191.53   290.8 3194.08   305.7 3196.46   331.8 3199.26   352.5 3203.36
#Mann= 4 ,-1 , 0
       0      .1       0   138.1    .045       0   160.5      .1       0
  211.61      .1       0
Bank Sta=138.1,160.5
XS Rating Curve= 0 ,0
Exp/Cntr=0.3,0.1