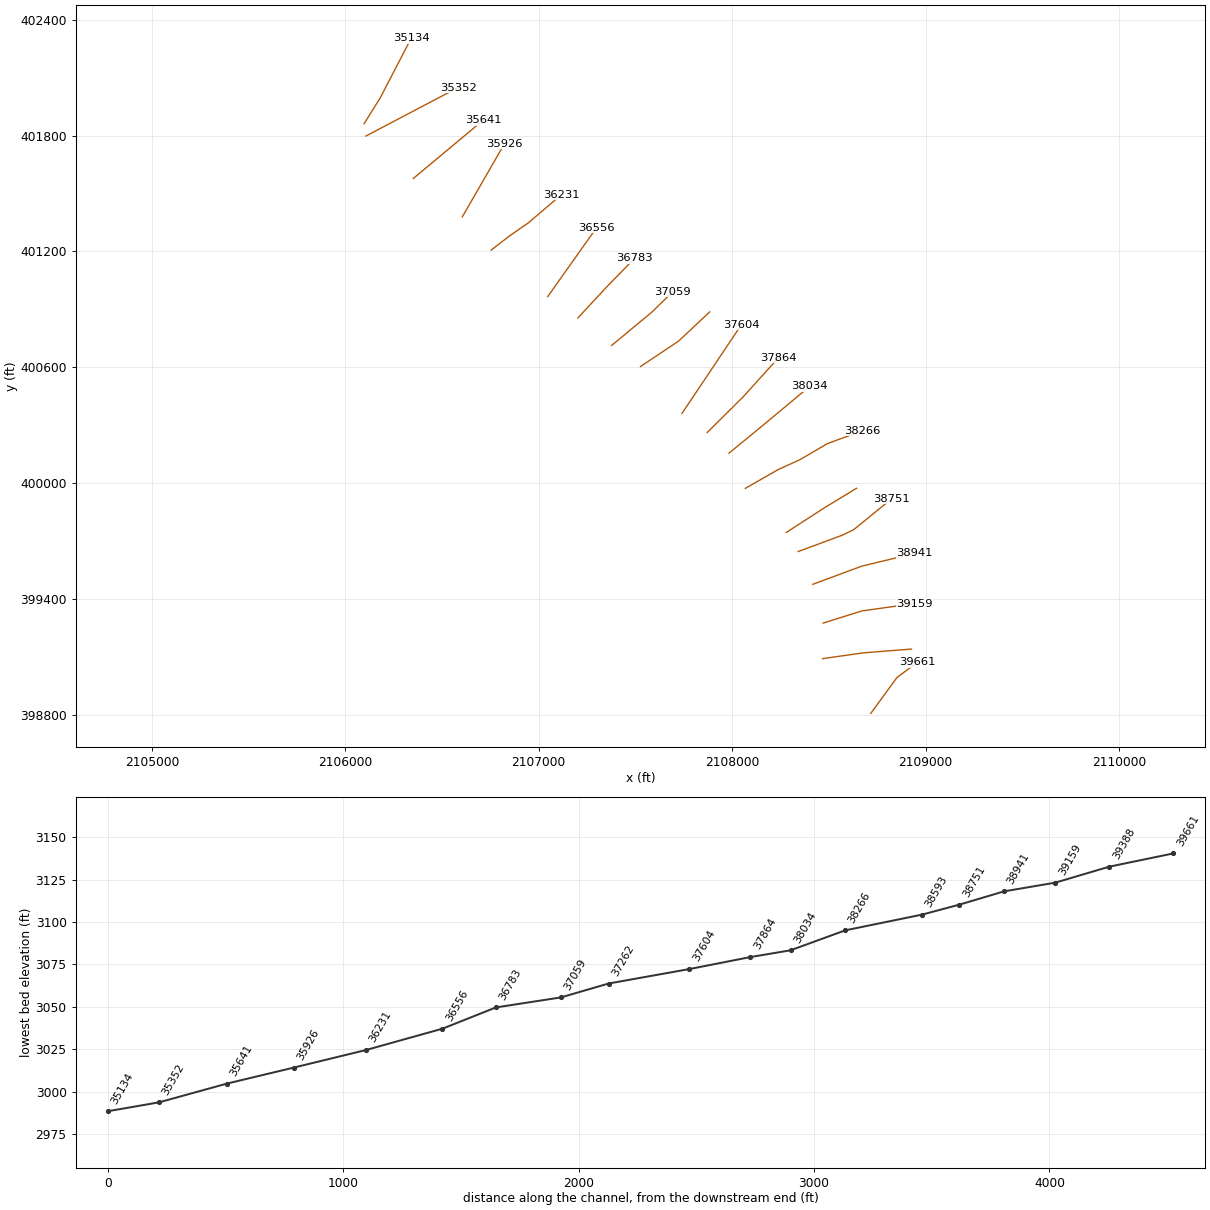
HEC-RAS study LAURELCK4.prj: LAURELCK4

--- LAURELCK4.g01 (geometry) --- (continued)

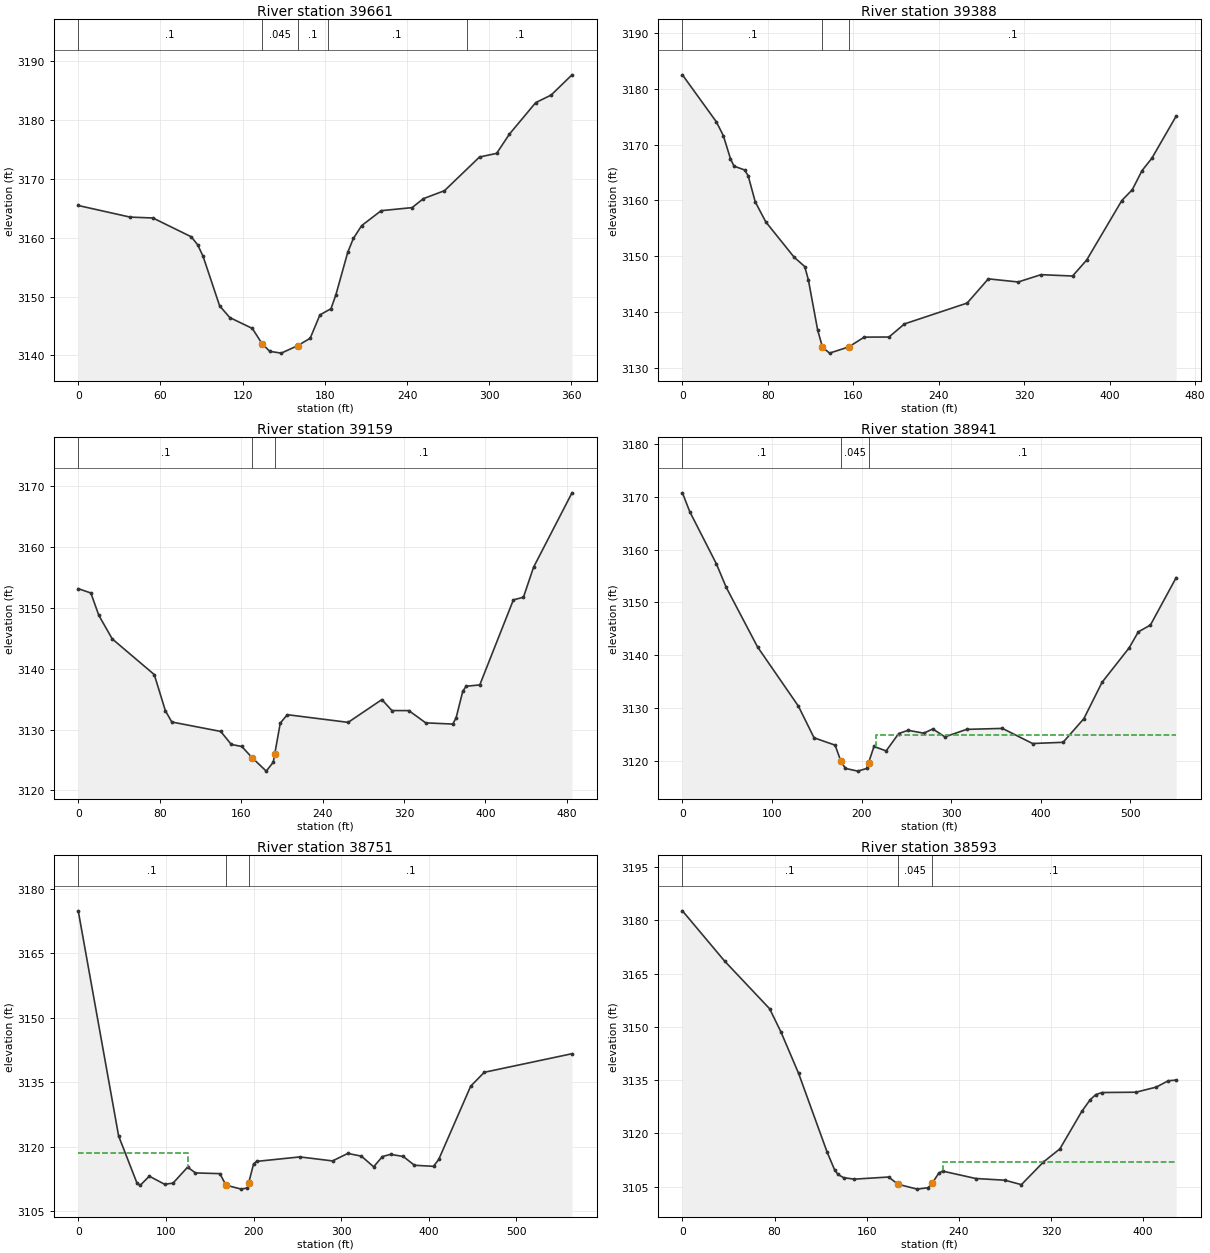
Type RM Length L Ch R = 1 ,39661   ,282.6,272.4,262.9
XS GIS Cut Line= 3
2108716.80686212398810.2361949532108852.36236531398995.791598111
2108956.80671021399074.125102863
#Sta/Elev= 30
       0 3165.46    37.8 3163.49    54.5 3163.34    82.5 3160.15    87.2 3158.78
    91.1 3156.85   103.2 3148.43   110.6 3146.44   127.1 3144.59   134.1 3142.03
   139.8  3140.7   148.2  3140.4   160.1 3141.66   169.3 3142.92   176.4 3146.89
   184.5 3147.94   188.1 3150.33   196.7  3157.5   200.8 3159.86   206.9 3162.05
   221.1 3164.58   243.7  3165.1   251.9 3166.62   267.3 3167.97   292.9 3173.69
   305.4 3174.31   314.7 3177.57   333.9 3182.92   345.2 3184.21   360.4 3187.64
#Mann= 5 ,-1 , 0
       0      .1       0   134.1    .045       0   160.1      .1       0
  182.19      .1       0  283.45      .1       0
Bank Sta=134.1,160.1
XS Rating Curve= 0 ,0
Exp/Cntr=0.3,0.1

Type RM Length L Ch R = 1 ,39388   ,226,229.1,228.7
XS GIS Cut Line= 3
 2108467.9179242399093.569617778 2108680.1402688399123.569557786
2108927.36221528399143.014072701
#Sta/Elev= 30
       0  3182.5    31.7 3174.09    38.3  3171.6      45 3167.44    48.3 3166.12
    58.2 3165.44    61.5 3164.42    68.2 3159.71    78.1 3156.11   104.6 3149.79
   114.5 3148.12   117.9 3145.75   126.6 3136.74   131.1 3133.67   137.7 3132.59
   155.7  3133.7   170.2 3135.46   193.4 3135.48   207.9 3137.83   266.6 3141.57
   286.4 3145.91   314.4 3145.35   335.7 3146.66   365.3 3146.42   378.5 3149.29
   411.4 3159.96   421.2  3161.9   430.3 3165.32   439.5 3167.54   462.3 3175.11
#Mann= 3 ,-1 , 0
       0      .1       0   131.1    .045       0   155.7      .1       0
Bank Sta=131.1,155.7
XS Rating Curve= 0 ,0
Exp/Cntr=0.3,0.1

Type RM Length L Ch R = 1 ,39159   ,217.1,218.2,219.5
XS GIS Cut Line= 3
2108470.69580579399277.4583576172108670.69573388399340.236119196
2108943.47340354399378.569375873
#Sta/Elev= 30
       0 3153.15    12.4 3152.44    20.2 3148.78    33.4  3144.9    74.7 3139.04
    85.6 3133.11    91.9 3131.25     140  3129.7   150.4 3127.56   160.7 3127.23
     171 3125.36   184.7 3123.18   191.6 3124.64     193 3125.95   198.5 3131.07
   205.4 3132.45   265.2 3131.19   298.3 3134.93   308.2 3133.13   324.8 3133.12
   341.4 3131.11   367.9 3130.91   371.2  3131.9   377.8  3136.3   381.1 3137.12
   394.5 3137.34   427.5  3151.3   437.4 3151.75   447.4 3156.69   485.1 3168.89
#Mann= 3 ,-1 , 0
       0      .1       0     171    .045       0     193      .1       0
Bank Sta=171,193
XS Rating Curve= 0 ,0
Exp/Cntr=0.3,0.1

Type RM Length L Ch R = 1 ,38941   ,188.5,190,189.3
XS GIS Cut Line= 3
2108417.36225104399478.0140588582108669.58451563399571.902978703
2108944.02884862399638.014066949
#Sta/Elev= 30
       0 3170.74     8.2 3167.17    37.9  3157.3    48.9 3152.84    83.9 3141.55
   129.5 3130.34     147 3124.34   170.5 3122.95  176.943119.906     182 3118.55
   195.8 3118.03   205.7 3118.53  207.913119.633   213.9  3122.7   227.5 3121.86
   241.5 3125.15     252 3125.76   269.5 3125.22   279.6 3126.02   293.1 3124.52
   317.4 3125.94   357.4 3126.12     391 3123.26   425.1 3123.49   448.3 3127.97
   468.6 3134.85     499 3141.41   509.1 3144.41   522.6 3145.69   551.4 3154.69
#Mann= 3 ,-1 , 0
       0      .1       0  176.94    .045       0  207.91      .1       0
#XS Ineff= 2 , 0
                           216.3         3124.95
Permanent Ineff=
       F       F
Bank Sta=176.94,207.91
XS Rating Curve= 0 ,0
Exp/Cntr=0.3,0.1

Type RM Length L Ch R = 1 ,38751   ,155.3,158.2,161.6
XS GIS Cut Line= 4
2108341.25118279399647.4582737832108569.02894247 399731.90298678
 2108627.9179323399760.2362634542108825.69575197399921.347161695
#Sta/Elev= 30
       0 3174.89    46.1 3122.54    67.1 3111.56    70.6 3111.05    81.1  3113.2
    98.6 3111.32   108.2 3111.59   124.8  3115.3   133.8 3113.96   161.6 3113.79
   168.6 3111.11   186.1 3110.19   193.1 3110.49   194.4 3111.57   200.1 3116.07
   203.6 3116.64   252.9 3117.68   290.2 3116.75   307.6 3118.49   323.1 3117.86
   337.1 3115.38   347.1 3117.77   356.4 3118.27   370.9 3117.78   383.6 3115.74
   405.4 3115.49   411.4 3117.12   447.8 3134.12   463.3 3137.35   563.4 3141.67
#Mann= 3 ,-1 , 0
       0      .1       0   168.6    .045       0   194.4      .1       0
#XS Ineff= 2 , 0
          125.64 3118.53
Permanent Ineff=
       F       F
Bank Sta=168.6,194.4
XS Rating Curve= 0 ,0
Exp/Cntr=0.3,0.1

Type RM Length L Ch R = 1 ,38593   ,323.6,326.8,324.9
XS GIS Cut Line= 3
2108280.14008453399746.3471836152108481.80667597399876.902696788
2108642.91790229399974.680716455
#Sta/Elev= 30
       0 3182.69    36.7 3168.52    75.7 3155.12    85.6 3148.54   100.9 3136.89
   125.5 3114.87   132.1 3109.77     135 3108.47   139.9 3107.56   149.2 3107.14
     179 3107.74   187.2  3105.7   203.8 3104.33   213.3 3104.73  216.69 3105.92
   222.7 3108.88   225.9  3109.4   254.7 3107.32     280 3106.84   294.3 3105.59
   313.4 3111.96   327.7 3115.66   346.8 3126.25     354 3129.49   358.8 3130.93
   364.3 3131.53   393.8 3131.62   411.3 3133.05   421.9 3134.85   428.7 3135.03
#Mann= 3 , 0 , 0
       0      .1       0   187.2    .045       0  216.69      .1       0
#XS Ineff= 2 , 0
                          226.37         3112.06
Permanent Ineff=
       F       F
Bank Sta=187.2,216.69
XS Rating Curve= 0 ,0
Exp/Cntr=0.3,0.1

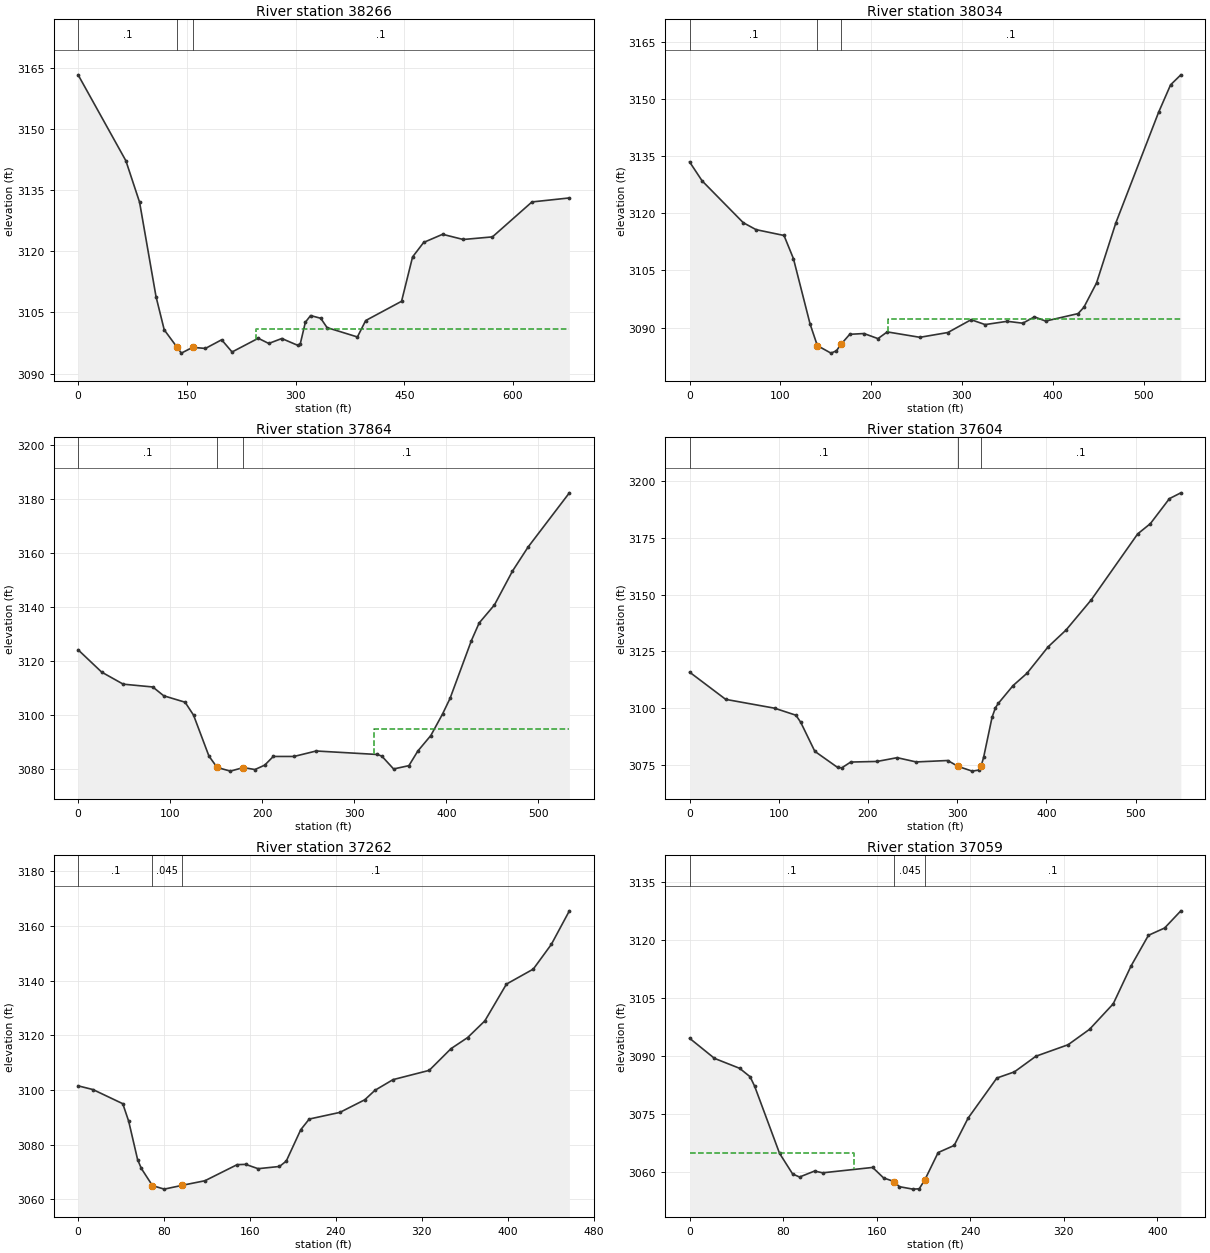
Type RM Length L Ch R = 1 ,38266   ,227.4,231.8,232.2
XS GIS Cut Line= 5
2108068.10310704399974.4028298712108235.46432087400070.236299619
2108353.51985905400124.4028579442108491.71413645400205.652695447
2108674.35320687400273.013781205
#Sta/Elev= 30
       0 3163.22    65.9 3142.17    84.8 3132.01   107.5 3108.87   118.8 3100.75
   135.8 3096.65   142.4 3095.04     1583096.455   175.6 3096.19     198 3098.31
   212.4 3095.32   248.5 3098.68     263 3097.41     281 3098.62   302.7 3096.97
   306.3 3097.18   313.5 3102.61   320.7 3104.24   334.7 3103.58   343.4  3101.3
   385.3    3099   396.7 3103.02   446.2 3107.74   461.4 3118.61   476.7 3122.16
   502.8 3124.15   531.3 3122.88   571.6 3123.52   626.1 3132.08   677.7 3133.06
#Mann= 3 ,-1 , 0
       0      .1       0   135.8    .045       0     158      .1       0
#XS Ineff= 2 , 0
                          244.82         3100.95
Permanent Ineff=
       F       F
Bank Sta=135.8,158
XS Rating Curve= 0 ,0
Exp/Cntr=0.3,0.1

Type RM Length L Ch R = 1 ,38034   ,168.6,170.1,171.2
XS GIS Cut Line= 3
2107983.38083553 400156.347347872108157.68626121400299.402836025
2108400.04765314400501.486093283
#Sta/Elev= 30
       0 3133.48    13.8  3128.5    59.1 3117.53    73.2  3115.7     104 3114.17
   114.4 3108.09   132.7 3090.96   140.7 3085.28   155.7  3083.3   161.7  3083.9
   166.6 3085.57   176.4 3088.24   192.1 3088.44   207.5 3087.11   217.7 3088.87
   253.7 3087.45   284.5 3088.71   310.1 3092.07   325.5 3090.79   349.9 3091.65
     367 3091.15   379.8 3092.82   392.1 3091.71   427.9 3093.67   434.3 3095.33
   448.2  3101.7   469.5 3117.48   516.5 3146.44   529.8  3153.7   541.1 3156.32
#Mann= 3 ,-1 , 0
       0      .1       0   140.7    .045       0   166.6      .1       0
#XS Ineff= 2 , 0
                          219.02         3092.26
Permanent Ineff=
       F       F
Bank Sta=140.7,166.6
XS Rating Curve= 0 ,0
Exp/Cntr=0.3,0.1

Type RM Length L Ch R = 1 ,37864   ,256.6,259.6,260.1
XS GIS Cut Line= 3
2107870.88073245400263.2916877872108056.29768446400447.319534943
2108238.93642679  400649.4027922
#Sta/Elev= 30
       0 3124.24    25.6 3115.98      49 3111.52    81.1 3110.48      93 3107.22
   116.2 3104.84   125.4 3100.05   142.1 3084.92     151  3080.7   165.4 3079.34
   179.4 3080.65   192.1 3079.93   202.7 3081.56     212 3084.77   234.5 3084.77
   258.6 3086.79     325  3085.5   329.9 3084.89   342.7 3080.14   359.3 3081.37
     369 3086.78   383.1 3092.51   395.8 3100.45     404 3106.26   427.2 3127.66
   435.6 3134.16   452.2 3140.83   471.8 3153.36   488.7 3162.23   533.6 3182.32
#Mann= 3 ,-1 , 0
       0      .1       0     151    .045       0   179.4      .1       0
#XS Ineff= 2 , 0
                          321.22         3094.82
Permanent Ineff=
       F       F
Bank Sta=151,179.4
XS Rating Curve= 0 ,0
Exp/Cntr=0.3,0.1

Type RM Length L Ch R = 1 ,37604   ,346.2,342.8,334.9
XS GIS Cut Line= 2
 2107741.0197717400362.5972634552108047.26981539400820.236111954
#Sta/Elev= 30
       0 3115.88    40.5 3103.87    95.2 3099.99   119.2 3096.89   124.6 3093.76
   140.4 3080.97   165.9 3073.88   170.7 3073.71   180.6 3076.25   210.2 3076.52
   232.7 3078.18     254  3076.3   289.4 3076.93     301 3074.32   316.8 3072.25
   324.7 3072.75  326.673074.315   329.6 3078.32   339.1 3096.03   342.9 3100.21
   346.2 3102.17   362.7 3109.98   378.3  3115.4   401.9 3127.02   421.9 3134.39
   450.3 3147.74   502.3 3176.79   516.5  3181.3   537.9 3192.34   550.7 3194.89
#Mann= 3 , 0 , 0
       0      .1       0     301    .045       0  326.67      .1       0
Bank Sta=301,326.67
XS Rating Curve= 0 ,0
Exp/Cntr=0.3,0.1

Type RM Length L Ch R = 1 ,37262   ,201.8,203,204.2
XS GIS Cut Line= 3
2107526.43653947400604.9583272782107722.96403354400736.208392859
2107884.07525986400887.597197697
#Sta/Elev= 30
       0 3101.53    13.9 3100.16    41.6 3094.99    47.1 3088.57    55.4 3074.54
    58.9 3071.29    69.2 3065.03    80.2 3063.74    96.8 3065.12    96.8 3065.13
   118.1 3066.81   148.1  3072.7     156  3072.8   167.6 3071.22   187.5 3072.03
   193.8 3073.99   207.3 3085.48   215.2 3089.38   243.7 3091.81   266.9 3096.43
   276.4  3099.9   293.2  3103.8   326.9 3107.19   347.2 3115.14   362.7  3119.2
   378.7  3125.3   398.8 3138.75   423.8 3144.24   440.6 3153.28   457.4 3165.56
#Mann= 3 ,-1 , 0
       0      .1       0    69.2    .045       0    96.8      .1       0
Bank Sta=69.2,96.8
XS Rating Curve= 0 ,0
Exp/Cntr=0.3,0.1

Type RM Length L Ch R = 1 ,37059   ,274.3,275.9,280.4
XS GIS Cut Line= 3
 2107377.1307357400713.9863244442107585.46430853400886.902973369
2107692.40864846400991.069431692
#Sta/Elev= 30
       0 3094.57    21.3 3089.36    42.8 3086.79    51.7 3084.62    55.6 3082.18
    76.9 3064.81    88.1 3059.46      94 3058.67   106.8 3060.21   113.8 3059.76
   156.5 3061.15   165.9 3058.43     175 3057.49   179.3 3056.18   190.8 3055.54
   196.3 3055.62   201.1 3057.93   212.5    3065   226.2 3066.84   238.1  3073.9
   262.7 3084.28   277.7 3085.87   296.1 3089.92   323.6 3092.89   341.9 3096.87
   362.2 3103.48   377.4 3113.25   392.3  3121.2   406.1 3123.08     420 3127.53
#Mann= 3 ,-1 , 0
       0      .1       0     175    .045       0   201.1      .1       0
#XS Ineff= 2 , 0
          140.63 3064.77
Permanent Ineff=
       F       F
Bank Sta=175,201.1
XS Rating Curve= 0 ,0
Exp/Cntr=0.3,0.1

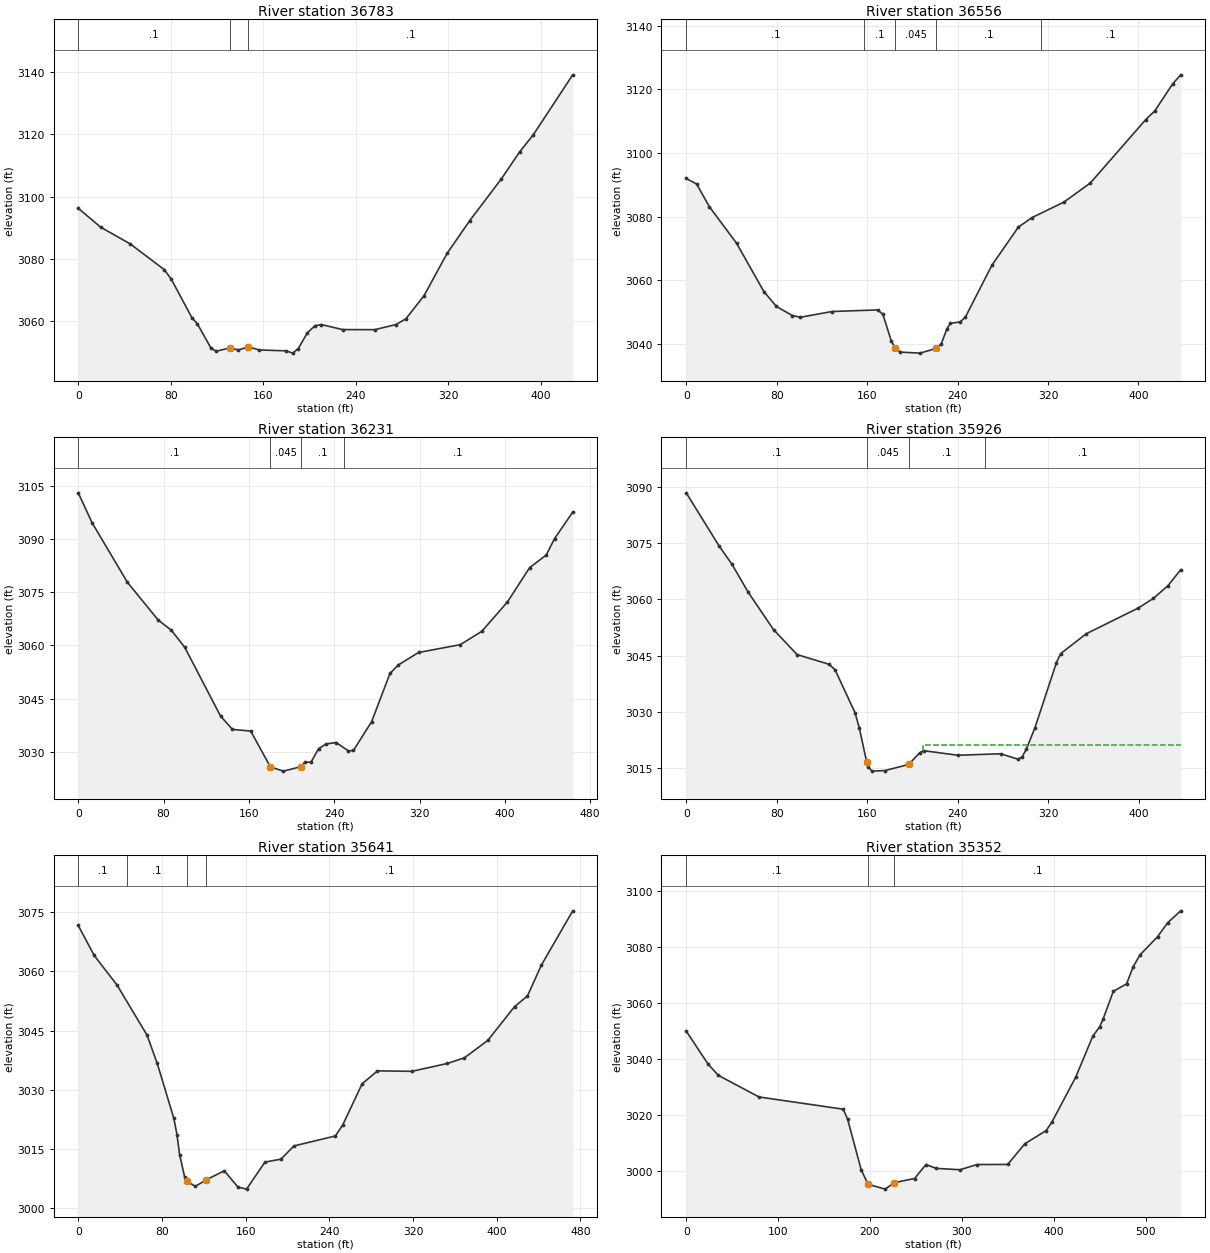
Type RM Length L Ch R = 1 ,36783   ,221.4,226.8,231.9
XS GIS Cut Line= 3
2107202.13075763400855.6527077852107350.74200895401016.069381699
2107496.57537872401165.375185445
#Sta/Elev= 30
       0 3096.21    19.4 3090.14    44.9 3084.76    74.3  3076.5    80.4 3073.42
    98.2 3061.05     103 3059.03   114.6 3051.32   119.2 3050.25   130.8  3051.3
   138.5 3050.67   147.1 3051.66   156.3 3050.66   179.6 3050.38   185.3 3049.64
   190.1 3051.08   198.1 3056.22   204.6 3058.43   210.1 3058.83   228.5 3057.21
   256.2 3057.18   274.7 3058.84   283.2 3060.68   298.9 3068.13   318.8  3081.7
   338.2 3092.16   365.8 3105.72   381.4 3114.31   393.3 3119.85   427.4 3139.13
#Mann= 3 ,-1 , 0
       0      .1       0   130.8    .045       0   147.1      .1       0
Bank Sta=130.8,147.1
XS Rating Curve= 0 ,0
Exp/Cntr=0.3,0.1

Type RM Length L Ch R = 1 ,36556   ,327.4,324.7,316.7
XS GIS Cut Line= 2
2107046.57529446400966.7640341222107299.35300413401323.708530203
#Sta/Elev= 30
       0 3092.01     9.2 3090.29    20.5 3083.13    44.6 3071.63    68.7 3056.47
    79.8 3051.79    93.9 3048.95     101 3048.41     129 3050.21   169.3 3050.71
   173.9 3049.38   181.3 3041.09  184.58 3038.85   189.4 3037.45   206.9 3037.13
     221  3038.6   225.5 3039.95   230.4 3044.56   233.6  3046.5   242.2 3046.92
   246.9 3048.42   270.4 3064.75   293.9 3076.77   305.9 3079.73     334 3084.57
   357.5  3090.6   406.4 3110.49   414.5 3113.26   430.3 3121.75   437.4 3124.59
#Mann= 5 ,-1 , 0
       0      .1       0  157.69      .1       0  184.58    .045       0
     221      .1       0  313.61      .1       0
Bank Sta=184.58,221
XS Rating Curve= 0 ,0
Exp/Cntr=0.3,0.1

Type RM Length L Ch R = 1 ,36231   ,297,305.4,311.8
XS GIS Cut Line= 4
2106753.51977822401207.041768789 2106850.0474723401281.347394452
2106945.18638963401347.3193753662107117.40848613401493.847297534
#Sta/Elev= 30
       0    3103    12.9  3094.6      46 3077.82      75 3067.13    87.4 3064.24
    99.9 3059.44   133.4 3040.09   144.6 3036.32   161.7 3035.86   180.2 3025.74
   192.3 3024.56   208.8 3025.81   212.4 3027.05   218.3  3027.1   225.3 3030.86
   232.4 3032.22   241.8 3032.62   253.4 3030.25   258.1 3030.42   275.1  3038.5
   292.3 3052.09     300 3054.46   319.1    3058   358.2  3060.2   378.4 3063.96
   402.4 3072.21   423.3 3081.93   438.8 3085.44   446.6 3090.07   463.7 3097.57
#Mann= 4 ,-1 , 0
       0      .1       0   180.2    .045       0   208.8      .1       0
  248.88      .1       0
Bank Sta=180.2,208.8
XS Rating Curve= 0 ,0
Exp/Cntr=0.3,0.1

Type RM Length L Ch R = 1 ,35926   ,286.4,285.1,282.6
XS GIS Cut Line= 2
2106604.90852687401379.2638652772106822.96419314401757.736205444
#Sta/Elev= 30
       0 3088.33      29  3074.2    40.3 3069.36    54.7  3061.9    77.1 3051.92
      98 3045.26   126.4 3042.67   131.6 3041.15   149.1 3029.82   152.9 3025.72
  159.493016.591   160.4 3015.47   164.2 3014.25   175.6  3014.4   196.5 3016.02
   206.1 3019.11   209.7  3019.7   239.9 3018.48   277.8 3018.87     293 3017.44
   296.7 3018.02   300.5 3020.14   308.1 3025.83     327 3043.12   330.8 3045.54
   353.5 3050.84     399 3057.61   412.7 3060.23   425.5  3063.6   436.8 3067.87
#Mann= 4 ,-1 , 0
       0      .1       0  159.49    .045       0   196.5      .1       0
  264.15      .1       0
#XS Ineff= 2 , 0
                          208.83         3021.26
Permanent Ineff=
       F       F
Bank Sta=159.49,196.5
XS Rating Curve= 0 ,0
Exp/Cntr=0.3,0.1

Type RM Length L Ch R = 1 ,35641   ,290.5,288.8,286.5
XS GIS Cut Line= 2
2106351.43626478401577.8750166152106714.63074836 401880.65295437
#Sta/Elev= 30
       0 3071.64    15.2 3064.05    37.1 3056.53    65.8 3043.81    75.5 3036.67
    91.4 3022.73    94.4 3018.56    96.9 3013.56   101.6 3007.98   103.7 3006.82
   111.9 3005.49   122.5 3007.15   139.6 3009.44   152.6 3005.33   160.9 3004.78
   178.5 3011.64   193.8 3012.38   206.2 3015.73   245.8 3018.26   252.8 3021.02
   271.4 3031.48   286.1 3034.77     319 3034.66   352.9 3036.65   369.2 3038.08
   391.6  3042.5   417.2 3051.08   429.5 3053.76   442.8 3061.58   472.8 3075.36
#Mann= 4 ,-1 , 0
       0      .1       0   46.15      .1       0   103.7    .045       0
   122.5      .1       0
Bank Sta=103.7,122.5
XS Rating Curve= 0 ,0
Exp/Cntr=0.3,0.1

Type RM Length L Ch R = 1 ,35352   ,214.5,217.8,230.5
XS GIS Cut Line= 2
2106106.29764745401797.3194596172106582.68645847402048.013840109
#Sta/Elev= 30
       0 3049.98    23.7 3038.28    34.8 3034.25    79.3 3026.52   170.9 3022.18
   175.7  3018.6   190.5 3000.58     198 2995.44   216.5 2993.72   226.7 2996.03
   248.6  2997.5     261 3002.48   272.1 3001.11   298.1 3000.62   316.5 3002.47
     350 3002.51   368.5 3009.83   391.9 3014.59   398.2 3017.65   424.1 3033.64
   442.6 3048.16   450.1  3051.5   453.8 3054.24   464.9  3064.1   479.4  3066.8
   486.6 3072.92   493.9 3077.05   513.1 3083.58   524.2 3088.58   538.3 3092.79
#Mann= 3 ,-1 , 0
       0      .1       0     198    .045       0   226.7      .1       0
Bank Sta=198,226.7
XS Rating Curve= 0 ,0
Exp/Cntr=0.3,0.1

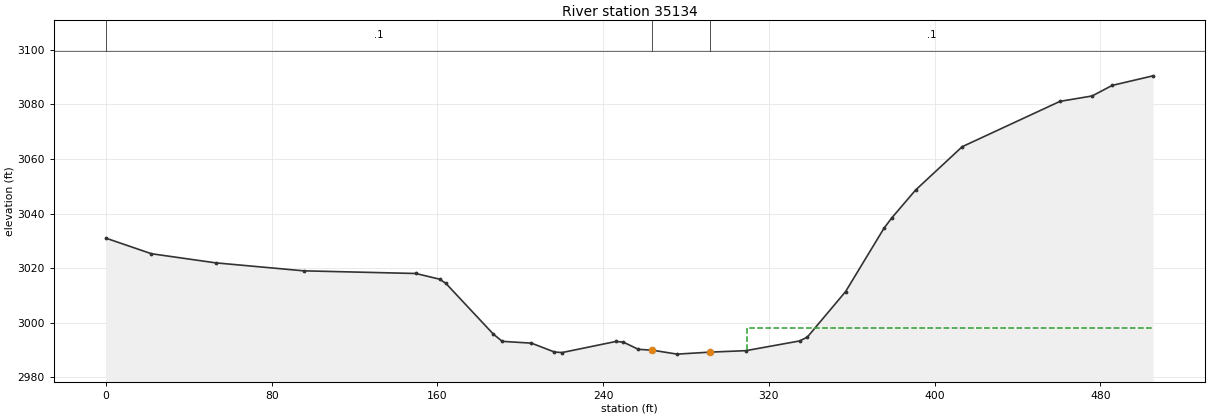
Type RM Length L Ch R = 1 ,35134   ,279.5,280.5,281.4
XS GIS Cut Line= 3
2106096.57522595401860.5138870332106180.60294503401995.236058533
2106340.32539463402302.875207037
#Sta/Elev= 30
       0 3030.97      22 3025.26    52.9 3021.93    95.4    3019   149.6 3018.02
   161.1 3015.93   164.1 3014.39     187 2995.81   191.3 2993.16   205.4  2992.5
   216.5 2989.25   220.2 2989.06   246.1 2993.11   249.7 2992.89     257 2990.24
   263.8 2989.92   275.7 2988.48  291.382989.203   308.9 2989.75   334.8 2993.31
   338.5 2994.69     357 3011.39   375.5 3034.55   379.2  3038.3   390.8 3048.61
   413.3 3064.48   460.5 3081.09     476 3083.06   485.7 3086.94   505.4 3090.44
#Mann= 3 ,-1 , 0
       0      .1       0   263.8    .045       0  291.38      .1       0
#XS Ineff= 2 , 0
                          309.34         2997.94
Permanent Ineff=
       F       F
Bank Sta=263.8,291.38
XS Rating Curve= 0 ,0
Exp/Cntr=0.3,0.1