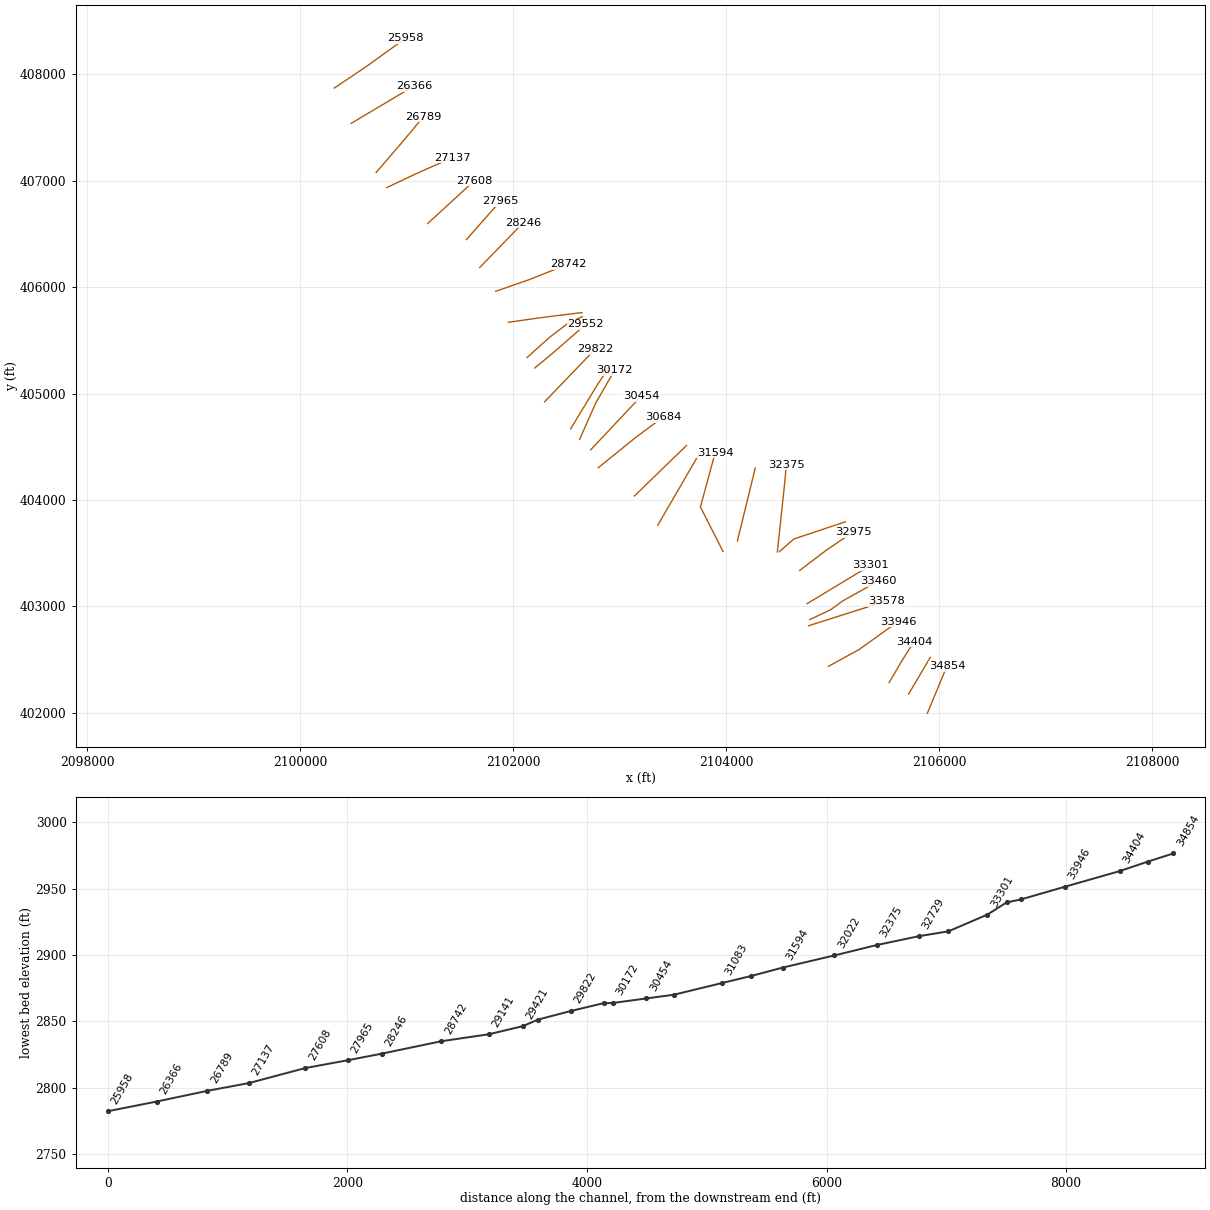
HEC-RAS study LAURELCK4.prj: LAURELCK4

--- LAURELCK4.g01 (geometry) --- (continued)

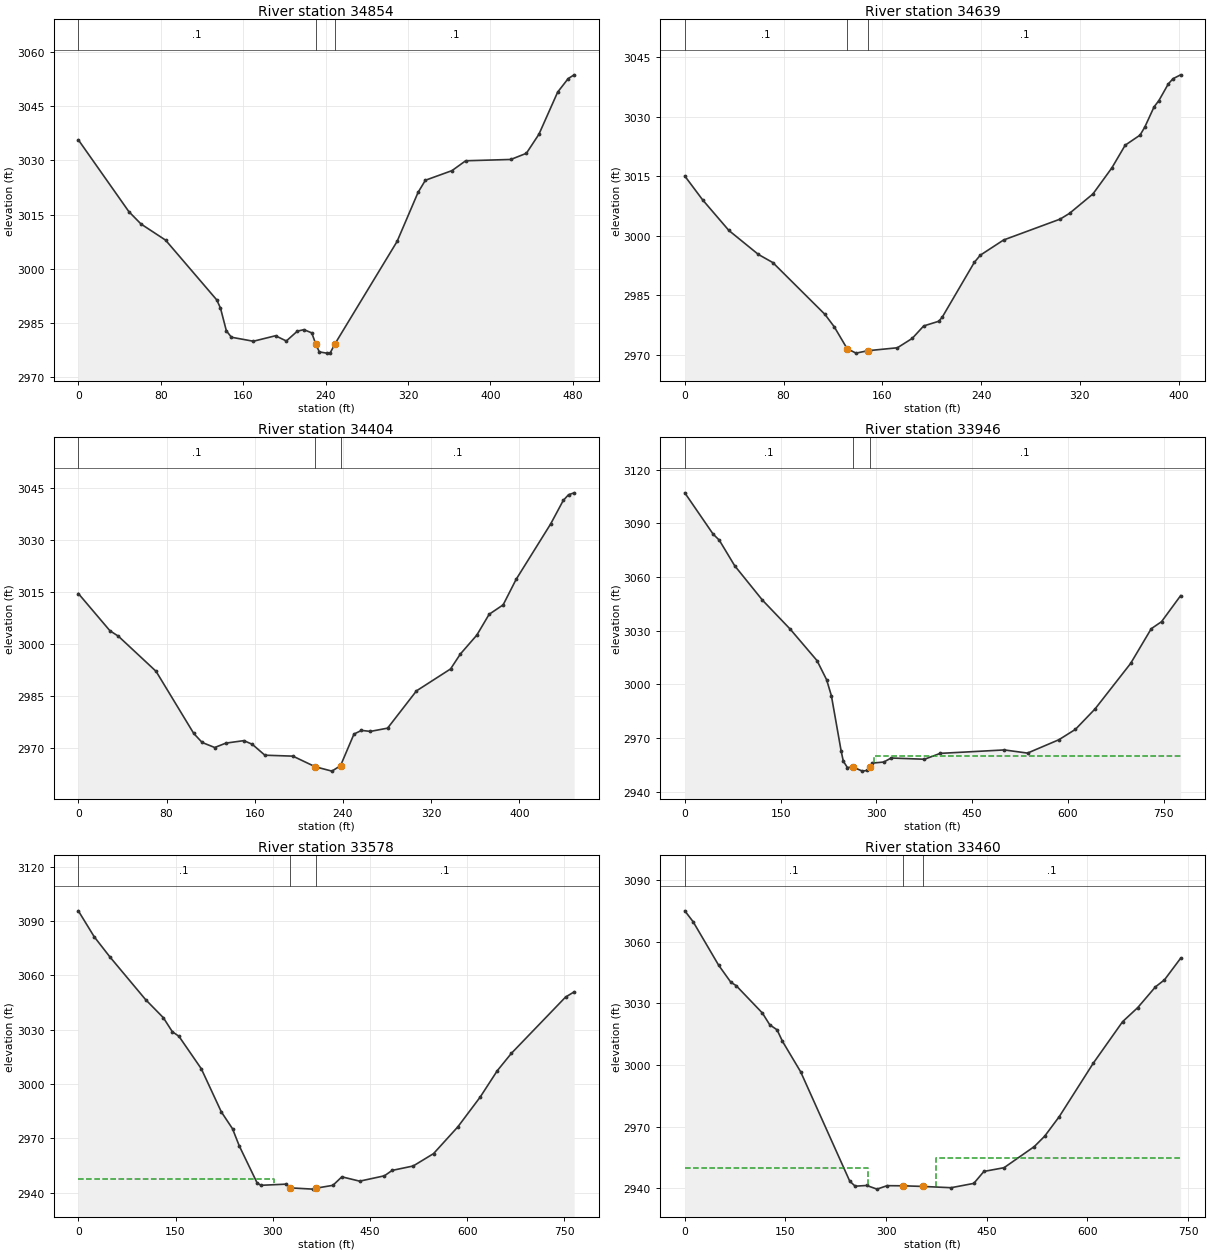
Type RM Length L Ch R = 1 ,34854   ,214.9,214.2,212.7
XS GIS Cut Line= 2
2105889.63075796401994.5418342052106074.35315755402438.986155286
#Sta/Elev= 30
       0 3035.69    49.1 3015.79    60.9 3012.37    84.7 3007.92   134.4 2991.36
     138 2989.09   143.7 2982.81   148.6 2981.04   169.9 2979.93   191.4 2981.45
   201.9    2980   212.6 2982.72     219 2983.14   226.6 2982.24   230.3 2979.29
   233.9 2976.98     241 2976.64   244.6 2976.76   249.1  2979.2   309.4 3007.55
   329.8 3021.15   336.9  3024.5   362.7 3027.16     376 3029.89   419.8 3030.25
   434.9 3031.95   447.1 3037.23   465.3  3048.9   475.5 3052.64   481.3 3053.68
#Mann= 3 ,-1 , 0
       0      .1       0   230.3    .045       0   249.1      .1       0
Bank Sta=230.3,249.1
XS Rating Curve= 0 ,0
Exp/Cntr=0.3,0.1

Type RM Length L Ch R = 1 ,34639   ,231.4,235.1,234.2
XS GIS Cut Line= 2
2105713.51988971402175.1668010352105917.68647611402521.000098869
#Sta/Elev= 30
       0 3015.07    14.4 3009.08    35.7 3001.35    59.6 2995.31    71.3 2993.26
   113.5 2980.21   121.1 2977.05   131.5 2971.56   138.7 2970.44   148.3 2971.05
   172.2 2971.79   184.2 2974.15   193.5 2977.29   205.8 2978.48   208.7  2979.6
   234.5 2993.31   239.3 2995.11   258.2 2998.95     304 3004.21   311.6 3005.66
   330.6 3010.56   345.9 3017.12   356.7 3022.84   368.7 3025.37   372.5 3027.35
   380.1  3032.5     384 3034.08   391.6 3038.27   395.4 3039.59   401.6 3040.57
#Mann= 3 ,-1 , 0
       0      .1       0   131.5    .045       0   148.3      .1       0
Bank Sta=131.5,148.3
XS Rating Curve= 0 ,0
Exp/Cntr=0.3,0.1

Type RM Length L Ch R = 1 ,34404   ,468.5,458.6,454.9
XS GIS Cut Line= 3
2105531.64459729402284.1249164492105647.50000861402482.963101447
2105764.97812012 402668.50013195
#Sta/Elev= 30
       0 3014.49    28.7 3003.74    36.3 3002.19    70.5 2992.06   104.7 2974.14
   112.3 2971.55   123.7  2970.1   133.9 2971.37   150.2 2972.08   157.8 2971.01
   169.2 2967.88   194.6 2967.61   214.8 2964.56     230 2963.29   237.8 2964.86
     250 2973.97   256.8 2975.03   264.9 2974.74   280.5 2975.68   306.7 2986.43
   337.6 2992.74   346.5 2997.05   361.4 3002.49   372.6  3008.5   385.3 3011.22
     397 3018.53   428.4 3034.55   439.8 3041.31   444.6 3042.96   449.7 3043.51
#Mann= 3 ,-1 , 0
       0      .1       0   214.8    .045       0   237.8      .1       0
Bank Sta=214.8,237.8
XS Rating Curve= 0 ,0
Exp/Cntr=0.3,0.1

Type RM Length L Ch R = 1 ,33946   ,371.2,367.5,366.9
XS GIS Cut Line= 3
2104961.43642011402436.9723797892105246.85317212 402593.22239536
2105613.51976162402855.722198442
#Sta/Elev= 30
       0 3106.97    44.3 3083.92      54 3080.52    78.1 3066.24   121.6    3047
   165.2 3030.74     207 3013.23     222 3002.56   229.5 2993.62   244.9  2962.5
   248.2 2956.99   254.6 2953.48  262.882953.784   278.1 2951.47   285.6 2951.87
   289.3 2953.51   293.6 2955.95   311.7 2956.56     323  2958.8   375.2 2958.11
   399.9 2961.39   500.3 2963.31   536.6 2961.55   585.7 2969.01   611.6 2974.81
   642.2 2986.17     698 3011.64   730.3 3031.04   746.4 3034.97   776.3 3049.52
#Mann= 3 ,-1 , 0
       0      .1       0  262.88    .045       0   289.3      .1       0
#XS Ineff= 2 , 0
                          296.55         2960.13
Permanent Ineff=
       F       F
Bank Sta=262.88,289.3
XS Rating Curve= 0 ,0
Exp/Cntr=0.3,0.1

Type RM Length L Ch R = 1 ,33578   ,118.9,117.9,126.5
XS GIS Cut Line= 2
2104775.18646455402818.314792946 2105504.3529852403050.259210944
#Sta/Elev= 30
       0 3095.59    24.5 3081.27    48.6 3070.19   103.7  3046.6   131.2 3036.57
     145 3028.87   155.3 3026.28   189.8 3008.36   220.7 2984.54     238 2975.22
   248.3 2965.83   275.8 2945.41   281.7 2944.01   320.6 2944.65  326.822942.598
   361.9  2941.9  366.962942.433   392.9    2944   406.7 2948.69   434.2  2946.3
   472.4 2949.26   484.3 2952.24   516.8 2954.68   548.2 2961.51   585.7  2976.3
   620.1  2992.7   646.6 3007.32   668.3 3016.88   751.9 3047.95   765.2 3050.84
#Mann= 3 ,-1 , 0
       0      .1       0  326.82    .045       0  366.96      .1       0
#XS Ineff= 2 , 0
          302.74 2947.74
Permanent Ineff=
       F       F
Bank Sta=326.82,366.96
XS Rating Curve= 0 ,0
Exp/Cntr=0.3,0.1

Type RM Length L Ch R = 1 ,33460   ,162.2,159.3,162.9
XS GIS Cut Line= 4
 2104785.7305556402876.1292915772104981.20337672402968.333452479
2105095.53653623403051.3171972912105428.39355709403237.569602313
#Sta/Elev= 30
       0 3075.02    12.4 3069.72    50.4 3048.59    68.6 3040.29    76.5 3038.65
   115.7 3025.28   126.6 3019.58   137.5 3017.14   145.5 3011.58   172.6 2996.75
   245.8 2943.54   253.9 2941.09     271 2941.45   286.4 2939.67   301.5 2941.35
     325 2941.29   355.5 2940.97   396.8 2940.36   430.6 2942.46   445.7 2948.28
   475.7 2950.09   520.8 2960.37   536.3 2965.45     558 2974.95   608.6  3000.9
   652.4 3021.13     675 3027.98   701.3 3038.04   714.7 3041.44   738.8 3051.96
#Mann= 3 ,-1 , 0
       0      .1       0     325    .045       0   355.5      .1       0
#XS Ineff= 2 , 0
          272.55 2949.95  373.97         2954.97
Permanent Ineff=
       F       F
Bank Sta=325,355.5
XS Rating Curve= 0 ,0
Exp/Cntr(USF)=0,0
Exp/Cntr=0.3,0.1

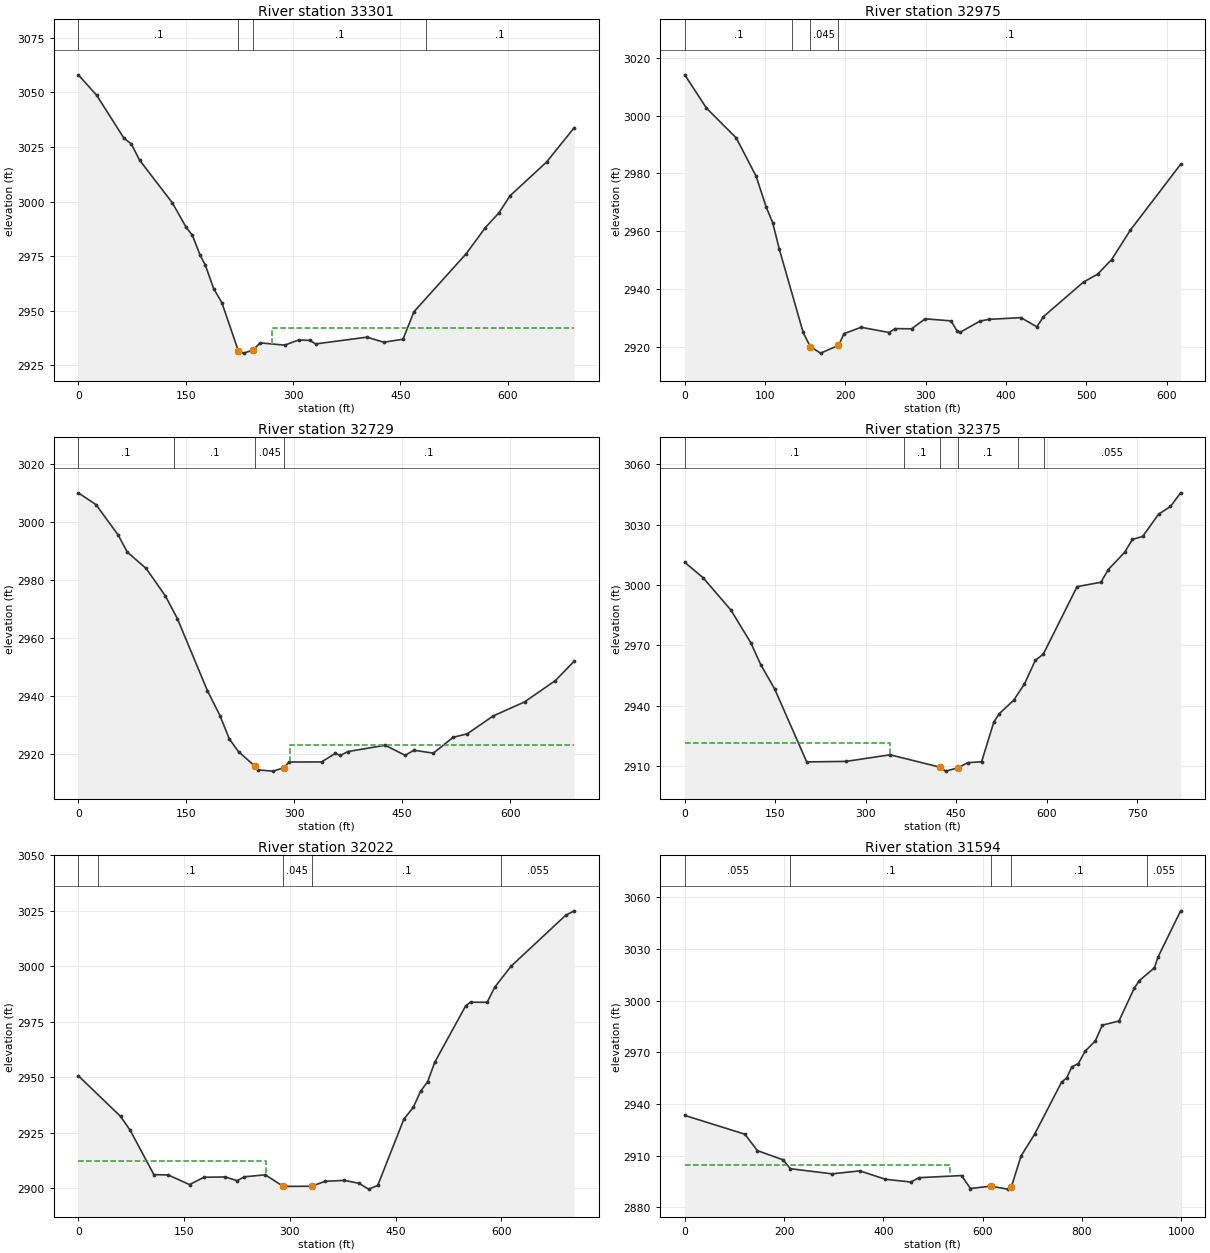
Type RM Length L Ch R = 1 ,33301   ,323.6,325.7,329.6
XS GIS Cut Line= 2
2104761.49653128 403026.090296032105354.20499155 403384.42356886
#Sta/Elev= 30
       0 3058.06    25.6  3048.7    63.8 3028.98      74 3026.42    85.5 3019.01
   131.5 2999.33   150.6  2988.2   159.4 2984.48   169.8 2975.66   177.5 2970.77
     189 2960.12   200.5 2953.64   223.5 2931.58   230.9 2930.53   243.6 2931.89
   254.1 2935.23   288.4 2934.19   307.8 2936.55   323.2 2936.38   331.4 2934.75
   403.1 2937.85   426.7 2935.53   453.5 2936.89   468.8 2949.49   541.7 2976.06
   568.5 2988.03   587.7 2994.89     603 3002.63     654 3018.08   692.6 3033.82
#Mann= 4 ,-1 , 0
       0      .1       0   223.5    .045       0   243.6      .1       0
  485.44      .1       0
#XS Ineff= 2 , 0
                          270.57         2941.98
Permanent Ineff=
       F       F
Bank Sta=223.5,243.6
XS Rating Curve= 0 ,0
Exp/Cntr=0.3,0.1

Type RM Length L Ch R = 1 ,32975   ,251.5,246.1,239.2
XS GIS Cut Line= 3
2104691.70500422403338.590327203 2104946.9131552403532.340267777
2105192.74665305403699.006929204
#Sta/Elev= 30
       0 3014.09      27 3002.58    64.1 2992.27    88.8 2979.04   101.2 2968.51
   109.4 2963.03   117.7 2953.82   147.4 2925.04   156.2 2920.16   169.1 2917.91
  191.362920.572   198.4 2924.65   219.5 2926.85   254.6 2925.03   261.8 2926.38
   282.4 2926.32   299.3 2929.76   331.4 2929.06   339.3  2925.5   343.3 2925.19
   367.8 2929.02   379.2 2929.59   418.6 2930.17   438.4 2927.01   446.4 2930.47
   496.5 2942.49   513.9 2945.17   531.5 2950.25   554.9 2960.46   617.4 2983.18
#Mann= 4 ,-1 , 0
       0      .1       0  133.66      .1       0   156.2    .045       0
  191.36      .1       0
Bank Sta=156.2,191.36
XS Rating Curve= 0 ,0
Exp/Cntr=0.3,0.1

Type RM Length L Ch R = 1 ,32729   ,337.9,354.1,375
XS GIS Cut Line= 3
2104501.08005738403515.673634455 2104636.4964532403633.382060453
2105119.82980412403794.840398952
#Sta/Elev= 30
       0 3009.97    24.6  3005.9    55.1 2995.55    68.1 2989.57    94.2 2983.97
     121  2974.5   137.7 2966.66   179.4 2941.92   196.8 2933.35   209.8 2925.33
   222.7 2920.91  245.862915.861     250 2914.66   270.7 2914.25  285.912915.427
   292.7 2917.38     338 2917.41   357.2 2920.37   364.1 2919.63   374.5 2920.98
   426.4 2923.15     454  2919.7   466.5 2921.43   493.3 2920.43   520.9 2925.89
   540.5 2927.09   576.2 2933.19   620.1 2938.06   662.9  2945.4     689 2952.05
#Mann= 4 ,-1 , 0
       0      .1       0  133.07      .1       0  245.86    .045       0
  285.91      .1       0
#XS Ineff= 2 , 0
                          293.94         2923.22
Permanent Ineff=
       F       F
Bank Sta=245.86,285.91
XS Rating Curve= 0 ,0
Exp/Cntr=0.3,0.1

Type RM Length L Ch R = 1 ,32375   ,357,352.8,349.3
XS GIS Cut Line= 3
2104481.28810221403512.5486406982104547.95496362404136.507038444
2104565.66326153404330.256979033
#Sta/Elev= 30
       0 3011.23    30.2 3003.64    76.4 2987.58   109.4 2971.31   125.9 2960.44
     149 2948.33   202.2  2912.1   267.7 2912.37   340.3 2915.65   422.8 2909.51
   422.8  2909.5   432.7 2907.53  453.662909.251     469 2911.73   492.1 2912.19
   512.3 2931.84   521.2 2936.03   545.1 2942.67   563.2 2950.84   581.2 2962.58
   594.4 2965.63   650.4 2999.18     690 3001.36   702.1 3007.65   729.5 3016.31
     742 3022.62   759.2 3024.12   785.5 3035.16   805.3    3039   822.1 3045.78
#Mann= 6 ,-1 , 0
       0      .1       0  363.49      .1       0   422.8    .045       0
  453.66      .1       0  552.13      .1       0  595.65    .055       0
#XS Ineff= 2 , 0
          340.12 2921.71
Permanent Ineff=
       F       F
Bank Sta=422.8,453.66
XS Rating Curve= 0 ,0
Exp/Cntr=0.3,0.1

Type RM Length L Ch R = 1 ,32022   ,424.8,428.7,424.8
XS GIS Cut Line= 2
2104106.32297286403615.6055212022104273.46896404404298.831188872
#Sta/Elev= 30
       0 2950.74    59.9 2932.45    73.4 2926.28   107.2 2906.24   127.4 2906.09
   157.8 2901.75   178.1 2905.06   208.5 2905.18   225.4  2903.5   235.5 2905.26
   265.2 2906.15  290.792900.932  330.832901.011   350.4 2903.25   377.4 2903.64
   398.2 2902.32   411.7 2899.71   424.7 2901.35   461.8  2931.2   475.3 2936.58
   485.5 2943.74   495.6 2948.15   505.7 2956.86   549.6 2982.26   556.4 2983.85
     580 2983.81   590.8 2990.65   613.8 3000.01   691.2 3022.94   703.4 3024.98
#Mann= 5 ,-1 , 0
       0      .1       0   27.67      .1       0  290.79    .045       0
  330.83      .1       0  600.04    .055       0
#XS Ineff= 2 , 0
          266.67 2912.36
Permanent Ineff=
       F       F
Bank Sta=290.79,330.83
XS Rating Curve= 0 ,0
Exp/Cntr=0.3,0.1

Type RM Length L Ch R = 1 ,31594   ,259.2,263.2,257
XS GIS Cut Line= 4
 2103970.8308821403517.0143944152103758.85468232403934.752781088
2103884.27453247404396.4346681982103898.67315616404446.310848084
#Sta/Elev= 30
       0 2933.37   120.8 2922.51   146.4 2912.94   197.9 2907.62   212.6 2902.47
   296.5 2899.49   352.7 2901.21   403.9 2896.34   455.4 2894.74   472.1 2897.27
   557.6 2898.49   575.4 2890.98   616.2 2892.33   650.2 2890.62   657.8 2891.88
   677.4 2909.88   704.6 2922.42     759 2952.67   769.2 2955.12   779.5  2961.5
   792.9 2963.47   806.2 2970.55     827 2976.62     841 2985.72   874.6 2988.14
   905.2 3007.06   915.4  3011.5     946    3019   953.2 3025.18   998.8 3052.04
#Mann= 5 ,-1 , 0
       0    .055       0  212.14      .1       0   616.2    .045       0
   657.8      .1       0  930.56    .055       0
#XS Ineff= 2 , 0
           534.8  2904.8
Permanent Ineff=
       F       F
Bank Sta=616.2,657.8
XS Rating Curve= 0 ,0
Exp/Cntr=0.3,0.1

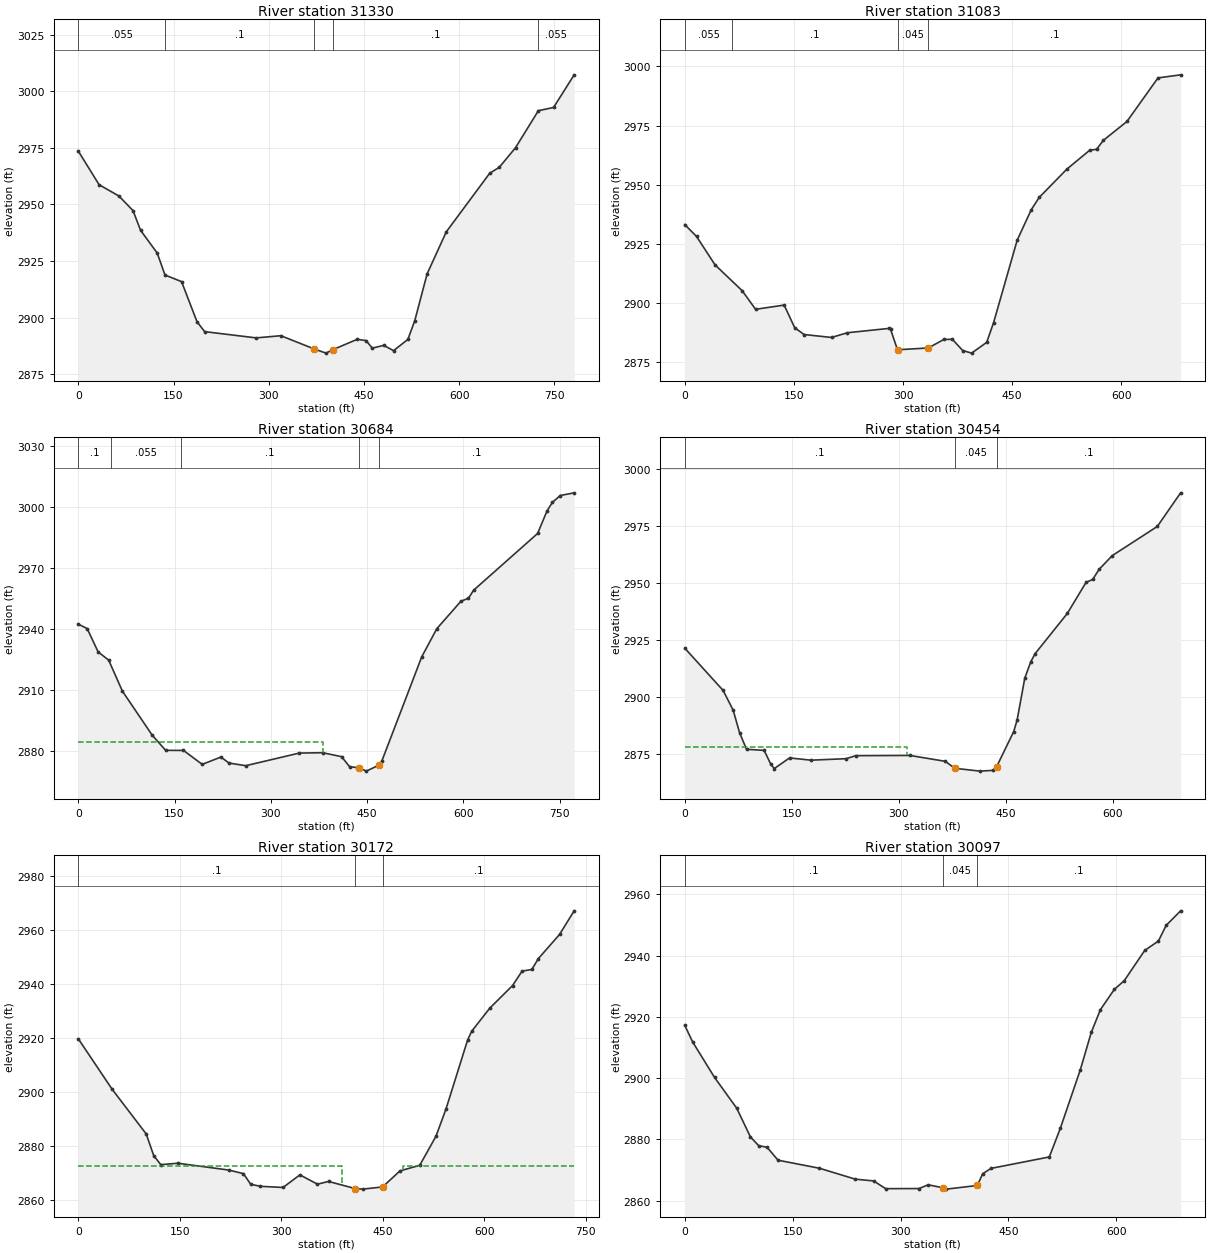
Type RM Length L Ch R = 1 ,31330   ,252.7,247.6,243.2
XS GIS Cut Line= 2
2103358.26365806403762.753864852 2103749.9773189404438.543155093
#Sta/Elev= 30
       0 2973.49    32.7 2958.66      64 2953.65    86.1 2947.24    98.1 2938.49
   124.3 2928.46   136.5 2918.77   162.6 2915.86     187 2898.12     199 2893.76
   280.2    2891     319 2891.96   371.2 2886.16   390.1 2884.27   401.12885.807
   439.4 2890.38   453.4  2889.8     463 2886.47   481.1  2887.7   496.6 2885.36
   519.1 2890.31   529.9 2898.49   549.5 2919.31   579.7 2937.86     648  2963.7
   663.2 2966.36   688.7 2974.98   724.7 2991.34   748.7 2992.78   781.1 3007.19
#Mann= 5 ,-1 , 0
       0    .055       0   136.5      .1       0   371.2    .045       0
   401.1      .1       0   724.7    .055       0
Bank Sta=371.2,401.1
XS Rating Curve= 0 ,0
Exp/Cntr(USF)=0,0
Exp/Cntr=0.3,0.1

Type RM Length L Ch R = 1 ,31083   ,400,398.7,395.1
XS GIS Cut Line= 2
2103138.82654828404037.7411598712103628.06474304404512.338963956
#Sta/Elev= 30
       0 2933.19    16.1 2928.19    41.6 2916.17    78.8 2905.28    97.3  2897.4
   136.6 2899.18   151.1  2889.6     164 2886.74   201.7  2885.5   223.4 2887.49
   280.6 2889.32   282.9  2888.9   292.4 2880.29   334.8 2881.07     356 2884.64
   367.8 2884.73     382 2879.99   394.3 2878.88     415 2883.43   424.4 2891.66
   456.9 2926.58   476.2 2939.44   487.1 2944.64   525.1 2956.59   556.7 2964.63
     566 2964.98   575.4 2968.79   607.8 2976.76   650.5 2995.17   681.6 2996.47
#Mann= 4 ,-1 , 0
       0    .055       0    65.1      .1       0   292.4    .045       0
   334.8      .1       0
Bank Sta=292.4,334.8
XS Rating Curve= 0 ,0
Exp/Cntr=0.3,0.1

Type RM Length L Ch R = 1 ,30684   ,227.6,230.6,236.3
XS GIS Cut Line= 3
2102799.65367022 404303.711100372103151.05487028 404587.79288128
2103408.45658645404779.529046372
#Sta/Elev= 30
       0 2942.33    13.8 2940.14    30.9 2928.66    47.3 2924.65    68.6 2909.46
   114.9 2887.89   136.1 2880.33   163.9 2880.28   193.1 2873.44   222.2 2877.03
   234.8 2874.09   260.9 2872.79   344.4 2878.99   380.9 2879.16   410.3 2877.22
   422.7 2872.32   437.92871.717   448.8 2870.12   468.9  2873.1     473 2875.04
   535.2 2926.25   558.7 2940.08   596.2 2953.53     608 2955.04   616.1 2958.99
   715.8 2986.86   730.7 2998.06   738.9 3002.13   751.1 3005.51   772.8 3006.83
#Mann= 5 ,-1 , 0
       0      .1       0   50.65    .055       0  159.54      .1       0
   437.9    .045       0   468.9      .1       0
#XS Ineff= 2 , 0
          380.76 2884.32
Permanent Ineff=
       F       F
Bank Sta=437.9,468.9
XS Rating Curve= 0 ,0
Exp/Cntr=0.3,0.1

Type RM Length L Ch R = 1 ,30454   ,276.6,281.7,285.3
XS GIS Cut Line= 2
2102727.67087454 404470.857419612103203.48882055404977.176616952
#Sta/Elev= 30
       0 2921.32    53.7 2902.76    67.8 2894.07    76.8 2884.16    86.5  2876.9
   111.2 2876.43   120.7 2870.23   125.5 2868.46   146.8 2873.11     177 2872.12
   226.1 2872.78   239.6 2874.09   315.4  2874.2     365 2871.62  378.382868.546
   413.7 2867.31   432.1 2867.65   436.9 2869.22   460.9 2884.68   465.7 2889.77
   476.4 2908.14   484.8 2915.35     491 2918.97     536 2936.59   562.3 2950.24
   571.6 2951.54   580.8 2956.06     599    2962   662.1 2974.81   694.8 2989.59
#Mann= 3 ,-1 , 0
       0      .1       0  378.38    .045       0   436.9      .1       0
#XS Ineff= 2 , 0
          311.38 2878.12
Permanent Ineff=
       F       F
Bank Sta=378.38,436.9
XS Rating Curve= 0 ,0
Exp/Cntr=0.5,0.3

Type RM Length L Ch R = 1 ,30172   ,75.3,74.6,74
XS GIS Cut Line= 4
2102623.96701372404569.6813689472102777.69275612404914.954300448
2102871.63646588405078.4401939512102954.59955454405222.405785277
#Sta/Elev= 30
       0 2919.53      50 2900.85   100.3 2884.32   111.4  2876.3   121.8 2872.94
     147 2873.47   222.4 2870.94     244 2869.62   254.7 2865.68   269.1 2864.92
   302.5  2864.5   327.4 2869.16   353.4 2865.71   369.7 2866.72  409.422864.073
   420.1 2863.88  449.612864.684   475.2 2870.62   504.5  2872.7   528.5 2883.46
   543.3 2893.55   575.2 2919.06   581.3 2922.36     608  2930.9   641.7 2939.29
   655.8 2944.63   670.2 2945.23   679.8 2949.25   711.1  2958.2   732.7 2966.95
#Mann= 3 ,-1 , 0
       0      .1       0  409.42    .045       0  449.61      .1       0
#XS Ineff= 2 , 0
           389.4  2872.5   479.6          2872.5
Permanent Ineff=
       F       F
Bank Sta=409.42,449.61
XS Rating Curve= 0 ,0
Exp/Cntr=0.5,0.3

Type RM Length L Ch R = 1 ,30097   ,279.1,275.2,270.3
XS GIS Cut Line= 4
 2102539.7841112404668.5049902052102706.93010238404944.235409871
2102786.23309338405074.7800962782102903.35753104405254.126850456
#Sta/Elev= 30
       0  2917.2    10.8 2911.84    41.3 2900.23    72.2 2890.16    91.3 2880.77
   102.8 2877.92   114.4 2877.42   129.6 2873.19     187 2870.58   237.1    2867
   262.5 2866.43   279.3  2863.9   325.7 2863.94   338.4 2865.16   358.9 2864.19
   363.7 2863.75   406.7 2864.94   414.2 2868.77   425.8 2870.52   506.8 2874.25
   522.1 2883.57     550 2902.75   565.2 2914.93   577.9 2922.34   597.3 2928.97
   611.1 2931.81   639.5 2941.67   658.5 2944.72   669.3 2949.85   689.4 2954.59
#Mann= 3 ,-1 , 0
       0      .1       0   358.9    .045       0   406.7      .1       0
Bank Sta=358.9,406.7
XS Rating Curve= 0 ,0
Exp/Cntr=0.5,0.3

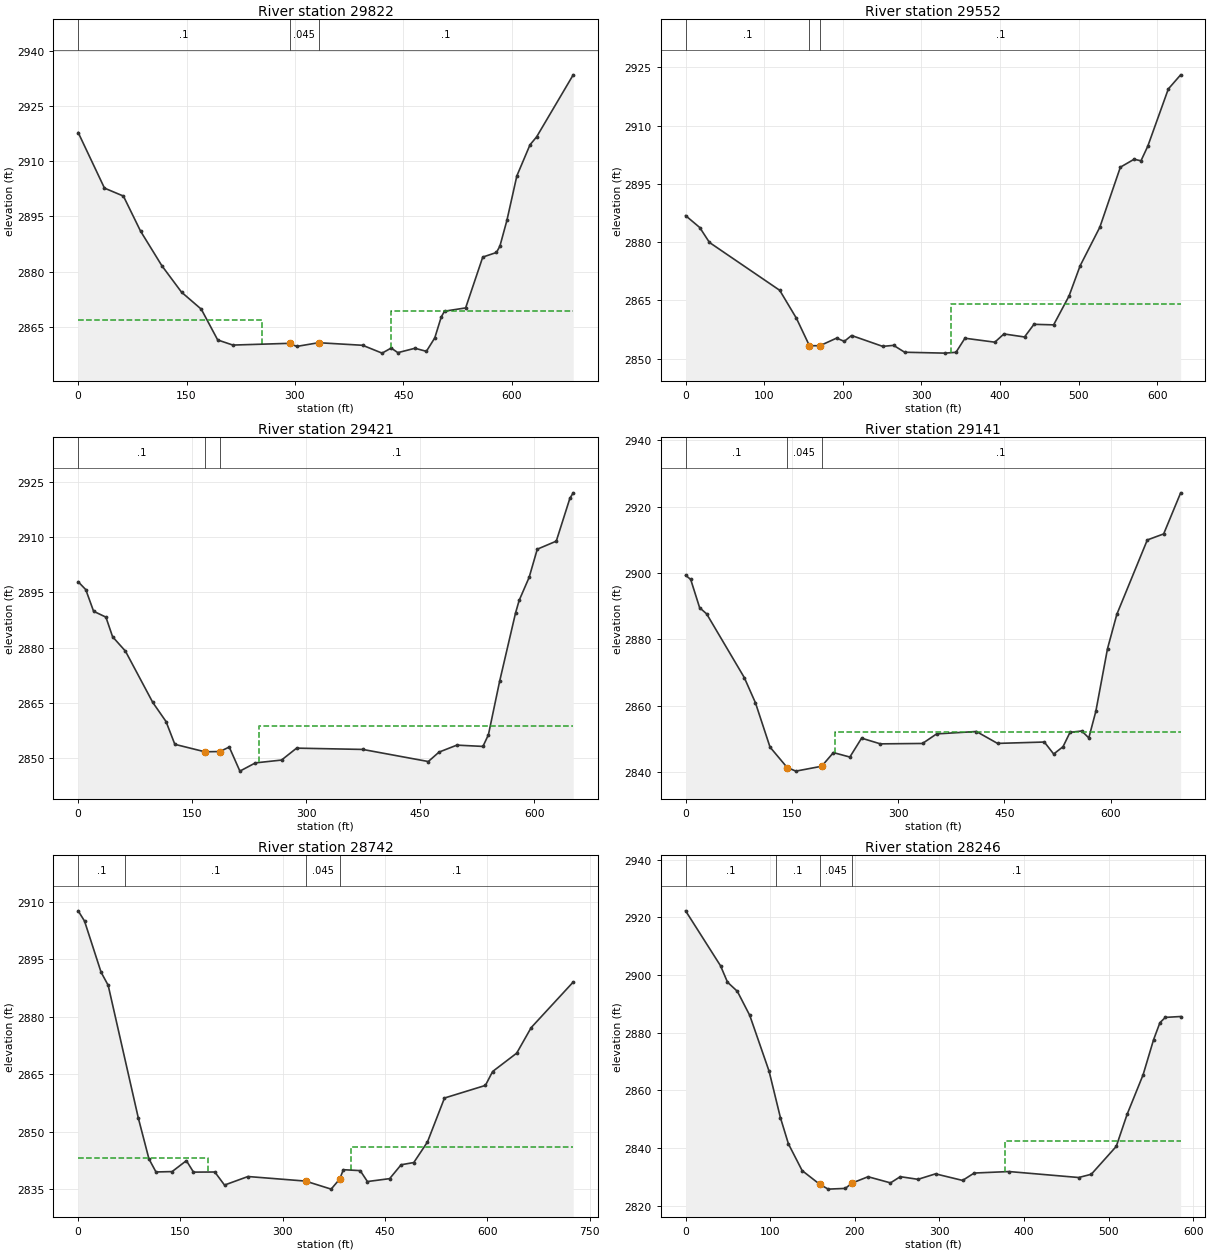
Type RM Length L Ch R = 1 ,29822   ,271.9,270.5,269.3
XS GIS Cut Line= 2
2102294.55461478 404922.274495782102769.15241888 405416.39293012
#Sta/Elev= 30
       0  2917.8    36.4 2902.68    62.6 2900.52    86.3    2891   115.8 2881.59
   143.1 2874.38   170.4 2869.76   193.1  2861.4   214.1 2860.01  292.712860.486
   302.3 2859.64  332.722860.652   393.7 2859.95   420.6 2857.82   433.2  2859.2
   442.4 2857.95   466.1 2859.14   481.9 2858.31   493.5 2861.96   502.5 2867.68
     507 2869.22   536.2 2870.11   559.9 2883.93   578.8 2885.18   583.6 2886.89
   593.3 2893.89   607.1 2906.01   625.3 2914.46   634.4  2916.6   685.1 2933.48
#Mann= 3 ,-1 , 0
       0      .1       0  292.71    .045       0  332.72      .1       0
#XS Ineff= 2 , 0
          254.33 2866.76  432.99         2869.27
Permanent Ineff=
       F       F
Bank Sta=292.71,332.72
XS Rating Curve= 0 ,0
Exp/Cntr=0.3,0.1

Type RM Length L Ch R = 1 ,29552   ,130.8,130.4,132.6
XS GIS Cut Line= 3
2102203.01488607405240.4190028742102371.23372557405379.547366374
2102681.11053519405650.215273548
#Sta/Elev= 30
       0 2886.85      18 2883.78    30.3 2879.94   119.7 2867.61     141 2860.39
   157.5 2853.34   170.8 2853.34   192.1  2855.3   201.8 2854.46   211.1 2855.97
   250.7 2853.17   264.6 2853.43   278.6 2851.66   329.7 2851.43   343.9 2851.64
   355.3 2855.27   393.3 2854.25   404.9 2856.37   431.1 2855.59   443.1 2858.85
   468.1 2858.71   487.7 2866.14   501.8 2873.92   526.9 2883.87     553 2899.32
   570.5 2901.37   579.2 2900.96   587.8 2904.69     614 2919.47   629.7 2923.11
#Mann= 3 ,-1 , 0
       0      .1       0   157.5    .045       0   170.8      .1       0
#XS Ineff= 2 , 0
                          337.13         2864.17
Permanent Ineff=
       F       F
Bank Sta=157.5,170.8
XS Rating Curve= 0 ,0
Exp/Cntr(USF)=0,0
Exp/Cntr=0.3,0.1

Type RM Length L Ch R = 1 ,29421   ,291.6,280.3,268.7
XS GIS Cut Line= 4
2102130.32359182405338.8637804022102342.87148145405529.671962057
2102524.59818739405668.6419669382102650.33507147405722.910739575
#Sta/Elev= 30
       0  2897.9      10 2895.76    20.3 2889.87    36.5 2888.28    45.3 2882.94
    62.2 2879.03    98.2 2865.07   115.6 2859.89   127.2 2853.69   166.7 2851.66
   186.4 2851.73   198.8 2852.95   212.8  2846.4   233.2 2848.64   267.6 2849.41
   287.4 2852.65   374.4  2852.3   460.7 2849.01   474.8 2851.57   498.3 2853.47
   532.6 2853.12   539.8 2856.28   554.5 2870.78   575.5  2889.4   580.3 2892.85
   593.4  2899.1   604.1 2906.75   629.1 2908.94     647 2920.59   651.4 2922.08
#Mann= 3 , 0 , 0
       0      .1       0   166.7    .045       0   186.4      .1       0
#XS Ineff= 2 , 0
                          238.07         2858.71
Permanent Ineff=
       F       F
Bank Sta=166.7,186.4
XS Rating Curve= 0 ,0
Exp/Cntr=0.3,0.1

Type RM Length L Ch R = 1 ,29141   ,386.6,398.9,399.2
XS GIS Cut Line= 4
2101954.16192287405670.1624356962102200.61123312405705.543926612
2102348.23692212405725.0645568672102647.14806971405761.665861622
#Sta/Elev= 30
       0 2899.32     7.2 2898.05    19.8 2889.55    29.7 2887.69    82.8 2868.53
    98.6 2860.92   119.2 2847.57   143.4 2841.43   155.7 2840.34   192.1 2841.81
   208.7 2845.92   231.9 2844.58   248.5 2850.27     275 2848.55   334.5 2848.67
   354.4 2851.55   410.6 2852.27   440.4 2848.69   506.5  2849.1   519.7 2845.49
   532.9 2847.69   542.8 2852.03   559.4 2852.42   569.3 2850.34   579.2 2858.32
   595.7  2877.2   608.9 2887.57   651.9 2909.95     675 2911.77     699 2924.14
#Mann= 3 , 0 , 0
       0      .1       0   143.4    .045       0   192.1      .1       0
#XS Ineff= 2 , 0
                          210.36         2852.19
Permanent Ineff=
       F       F
Bank Sta=143.4,192.1
XS Rating Curve= 0 ,0
Exp/Cntr=0.3,0.1

Type RM Length L Ch R = 1 ,28742   ,472.1,495.7,499.7
XS GIS Cut Line= 3
2101837.03748521405961.7533879432102151.80949345406071.557630286
2102516.60305521406216.743035451
#Sta/Elev= 30
       0 2907.69     9.3 2905.03    33.6 2891.67      44 2888.25    88.3 2853.54
   103.8 2842.94   114.1 2839.53   137.8 2839.63   158.7 2842.48   169.1 2839.49
   200.4 2839.52   214.6 2836.11     249 2838.34   333.4 2837.15     371 2835.05
   383.6  2837.7   383.6 2837.72   388.9 2840.12   413.6 2839.88   424.2 2837.03
   456.8 2837.79   473.6 2841.41   492.2 2841.99   512.2 2847.35   537.2 2858.83
   597.2 2862.12   607.8 2865.75   643.1 2870.54   664.3  2877.2     726 2889.11
#Mann= 4 ,-1 , 0
       0      .1       0   69.13      .1       0   333.4    .045       0
   383.6      .1       0
#XS Ineff= 2 , 0
          191.06 2843.17  400.68         2846.08
Permanent Ineff=
       F       F
Bank Sta=333.4,383.6
XS Rating Curve= 0 ,0
Exp/Cntr=0.3,0.1

Type RM Length L Ch R = 1 ,28246   ,280.1,281.9,283.9
XS GIS Cut Line= 2
2101685.75202662406185.0219702872102093.24727464  406604.7176532
#Sta/Elev= 30
       0 2922.26    41.3 2903.18    49.5  2897.5    61.1 2894.35    75.8 2885.98
    98.6 2866.66     112 2850.54   121.5  2841.4   137.7 2832.13   158.6 2827.35
   168.5  2825.7   188.7 2825.95   196.8 2827.82   215.6    2830   242.1 2827.87
   253.7 2830.02   274.6  2829.1   295.3    2831   327.3 2828.72     341 2831.28
   382.2  2831.8   464.5 2829.73   479.4 2830.86   508.9 2840.53   521.7 2851.64
   540.6 2865.37     553 2877.55   560.5 2883.46   566.9 2885.29     585 2885.59
#Mann= 4 ,-1 , 0
       0      .1       0  106.83      .1       0   158.6    .045       0
   196.8      .1       0
#XS Ineff= 2 , 0
                          377.59         2842.31
Permanent Ineff=
       F       F
Bank Sta=158.6,196.8
XS Rating Curve= 0 ,0
Exp/Cntr=0.3,0.1

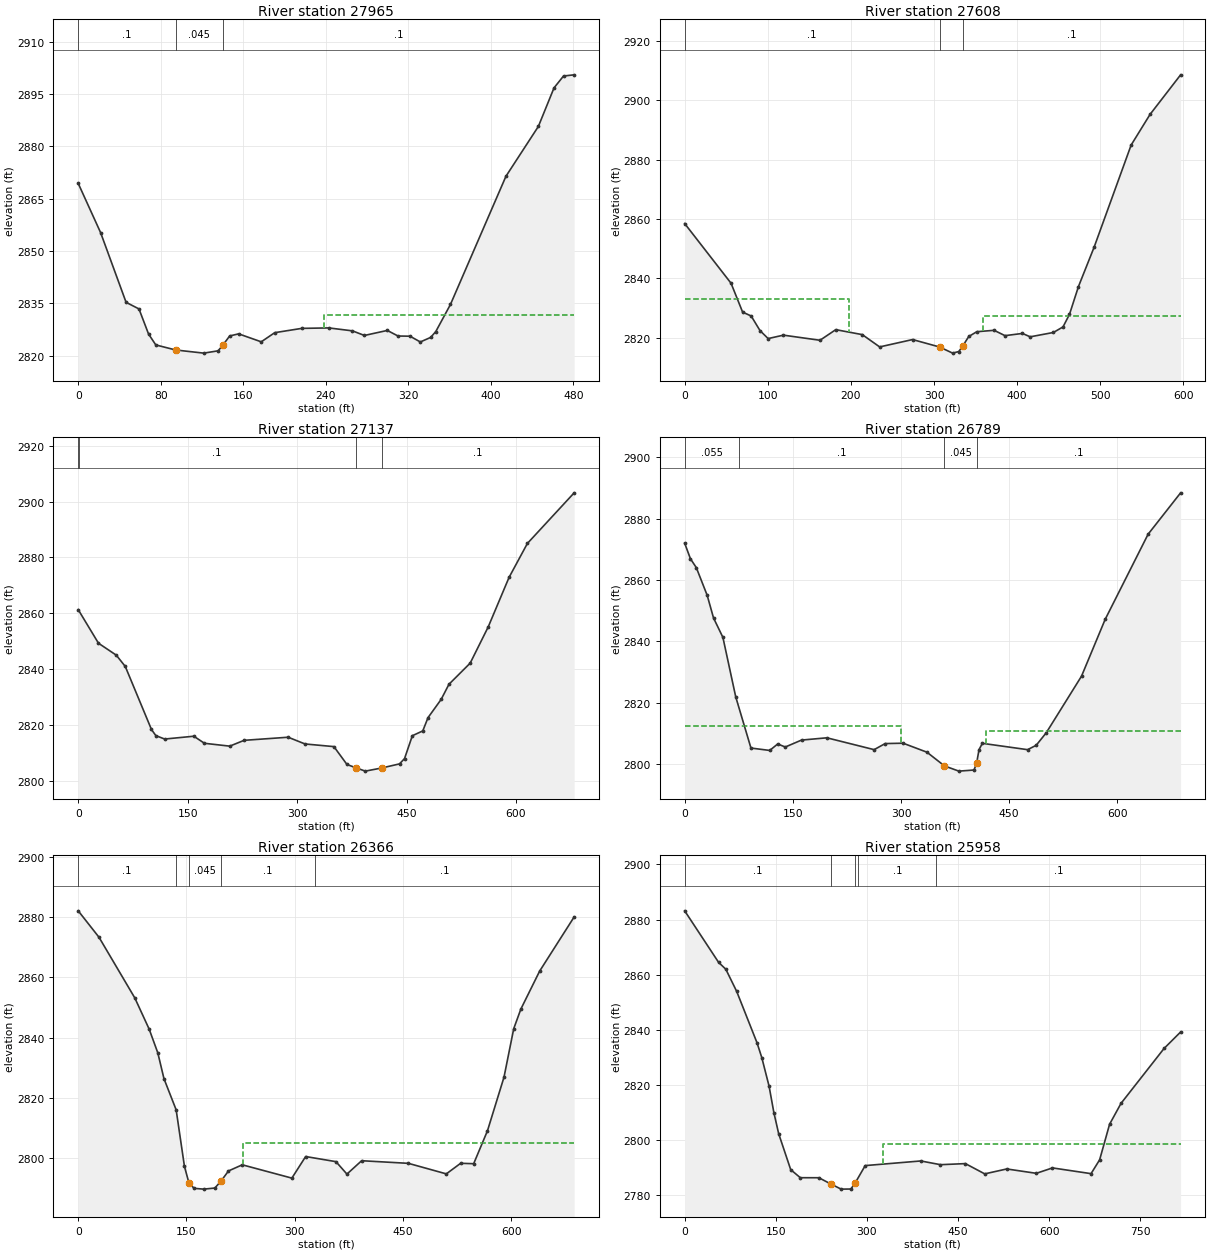
Type RM Length L Ch R = 1 ,27965   ,360.1,356.6,352.1
XS GIS Cut Line= 2
2101561.30706555406447.3318131122101878.51902953406808.465277195
#Sta/Elev= 30
       0  2869.4    21.7  2855.3    46.4 2835.33    58.9 2833.44    68.2 2826.24
    75.2 2823.13    94.4 2821.68   121.7 2820.78   135.6 2821.44   140.3  2823.1
   146.8  2825.7   155.5  2826.3   177.4 2824.02   190.5 2826.64   216.7 2827.87
   242.9    2828   265.8 2827.16   277.4 2825.84   299.6 2827.28     310 2825.68
   321.6 2825.63   331.6 2823.98   341.6 2825.28   346.6 2826.96   360.8 2834.72
   414.6 2871.44     446  2885.7   461.2 2896.76   470.4 2900.15   480.7 2900.49
#Mann= 3 ,-1 , 0
       0      .1       0    94.4    .045       0   140.3      .1       0
#XS Ineff= 2 , 0
                          238.26         2831.68
Permanent Ineff=
       F       F
Bank Sta=94.4,140.3
XS Rating Curve= 0 ,0
Exp/Cntr=0.3,0.1

Type RM Length L Ch R = 1 ,27608   ,473.6,471,461.2
XS GIS Cut Line= 2
2101197.73364571406598.6175997852101636.94995889407002.452750117
#Sta/Elev= 30
       0 2858.48    55.8 2838.38    69.7 2828.67      80 2827.36    90.6 2822.46
   100.4 2819.76   118.8 2820.91   162.8 2819.19   181.8 2822.76   213.7 2821.09
   234.6 2816.95   274.2 2819.43   306.6 2816.93   322.4 2814.86   329.8  2815.4
   334.4 2817.19   341.8 2820.46   351.5 2822.07   372.3 2822.54   385.4 2820.74
   406.4 2821.49   415.7 2820.35   443.6 2821.81   455.2 2823.68     463 2827.92
   473.8 2837.28   492.6  2850.5   537.2 2884.92   559.9 2895.21   596.7 2908.54
#Mann= 3 ,-1 , 0
       0      .1       0   306.6    .045       0   334.4      .1       0
#XS Ineff= 2 , 0
          197.28 2833.17  359.25         2827.29
Permanent Ineff=
       F       F
Bank Sta=306.6,334.4
XS Rating Curve= 0 ,0
Exp/Cntr=0.3,0.1

Type RM Length L Ch R = 1 ,27137   ,338.5,348,356.2
XS GIS Cut Line= 3
2100813.41912562406936.5700078612101105.01007786407074.435217693
2101431.98219296407218.400809035
#Sta/Elev= 30
       0 2861.31    27.8 2849.29    52.2 2845.02    64.5 2840.99   100.4 2818.43
   106.4 2816.24   118.5 2815.01   158.5 2816.02     173 2813.49   207.7 2812.47
   227.4 2814.55   287.8 2815.66   310.9 2813.25   350.5  2812.3   368.4 2805.91
   380.5 2804.74   393.5 2803.53  416.052804.654   440.4 2806.12   447.3 2808.01
     458  2816.2   472.3 2817.92   479.5 2822.67   497.5  2829.2   508.2 2834.61
   537.3 2842.18     562 2855.13   590.6 2872.87   615.7    2885   679.8 2903.11
#Mann= 4 ,-1 , 0
       0    .055       0     .58      .1       0   380.5    .045       0
  416.05      .1       0
Bank Sta=380.5,416.05
XS Rating Curve= 0 ,0
Exp/Cntr=0.3,0.1

Type RM Length L Ch R = 1 ,26789   ,432.1,423.2,417.4
XS GIS Cut Line= 3
2100713.27792171407078.4650652862100962.84796062407368.767962366
2101158.32985312407602.683833122
#Sta/Elev= 30
       0 2872.01       8 2866.94    16.1 2864.07    31.2 2855.02      40 2847.63
      53 2841.29    70.8 2821.88    91.9 2805.18   117.9  2804.4     129 2806.51
   139.5 2805.52     162 2807.78   197.2 2808.52   262.7 2804.66     278 2806.64
   302.9 2806.76     336 2803.82   360.2 2799.35   380.2 2797.65   401.2 2798.01
  404.812800.258   408.2 2804.68   412.8 2806.72   475.5 2804.65   487.4 2806.07
   501.4 2810.17   550.3 2828.64     583 2847.13   642.6 2874.95   687.7 2888.46
#Mann= 4 ,-1 , 0
       0    .055       0    74.7      .1       0   360.2    .045       0
  404.81      .1       0
#XS Ineff= 2 , 0
          299.89 2812.26  417.54          2810.6
Permanent Ineff=
       F       F
Bank Sta=360.2,404.81
XS Rating Curve= 0 ,0
Exp/Cntr=0.3,0.1

Type RM Length L Ch R = 1 ,26366   ,408.5,408,409.2
XS GIS Cut Line= 3
2100479.16323245407540.1836300342100682.28848237407661.017049775
2101069.78836355407891.225578859
#Sta/Elev= 30
       0 2882.15    28.8 2873.36    78.4 2853.18    98.3  2842.8   110.3 2834.89
   118.8 2826.33   135.7 2815.95   147.2 2797.12   153.3 2791.73   160.5 2789.84
   173.9 2789.58   189.3 2789.94   198.2 2792.36   208.2 2795.63   227.3 2797.67
     296 2793.24   315.1 2800.42   357.1 2798.72   372.3 2794.58   392.7 2799.03
   457.4 2798.16     510 2794.65   529.8 2798.17   547.9 2798.04     567 2808.99
   589.9 2826.81   603.4 2842.96   613.3 2849.49   639.3  2862.1   687.1 2880.12
#Mann= 5 ,-1 , 0
       0      .1       0  135.04      .1       0   153.3    .045       0
   198.2      .1       0  327.99      .1       0
#XS Ineff= 2 , 0
                          228.98         2805.03
Permanent Ineff=
       F       F
Bank Sta=153.3,198.2
XS Rating Curve= 0 ,0
Exp/Cntr=0.3,0.1

Type RM Length L Ch R = 1 ,25958   ,379.9,375.7,366.4
XS GIS Cut Line= 3
2100319.78822312407871.4336237012100618.74661469408072.475544453
2100988.53819796408339.142005861
#Sta/Elev= 30
       0 2883.16    55.8 2864.49    67.7 2861.99    85.6 2853.95   119.1  2835.3
   126.9 2829.96   138.9  2819.6   146.8 2810.01   154.7 2802.36   174.5 2789.34
   190.3 2786.42   220.8 2786.41  240.612784.137   257.5 2782.28   273.5 2782.32
  280.672784.538   297.1 2790.81   388.6 2792.49     421 2791.14     462 2791.53
   493.8 2787.81   530.1 2789.59   578.7 2788.01   605.3 2789.97   668.8 2787.89
   682.9  2792.9   699.3  2805.8   718.1 2813.36     789 2833.28   816.2 2839.24
#Mann= 5 ,-1 , 0
       0      .1       0  240.61    .045       0  280.67      .1       0
  285.82      .1       0  413.91      .1       0
#XS Ineff= 2 , 0
                          325.98         2798.54
Permanent Ineff=
       F       F
Bank Sta=240.61,280.67
XS Rating Curve= 0 ,0
Exp/Cntr=0.3,0.1