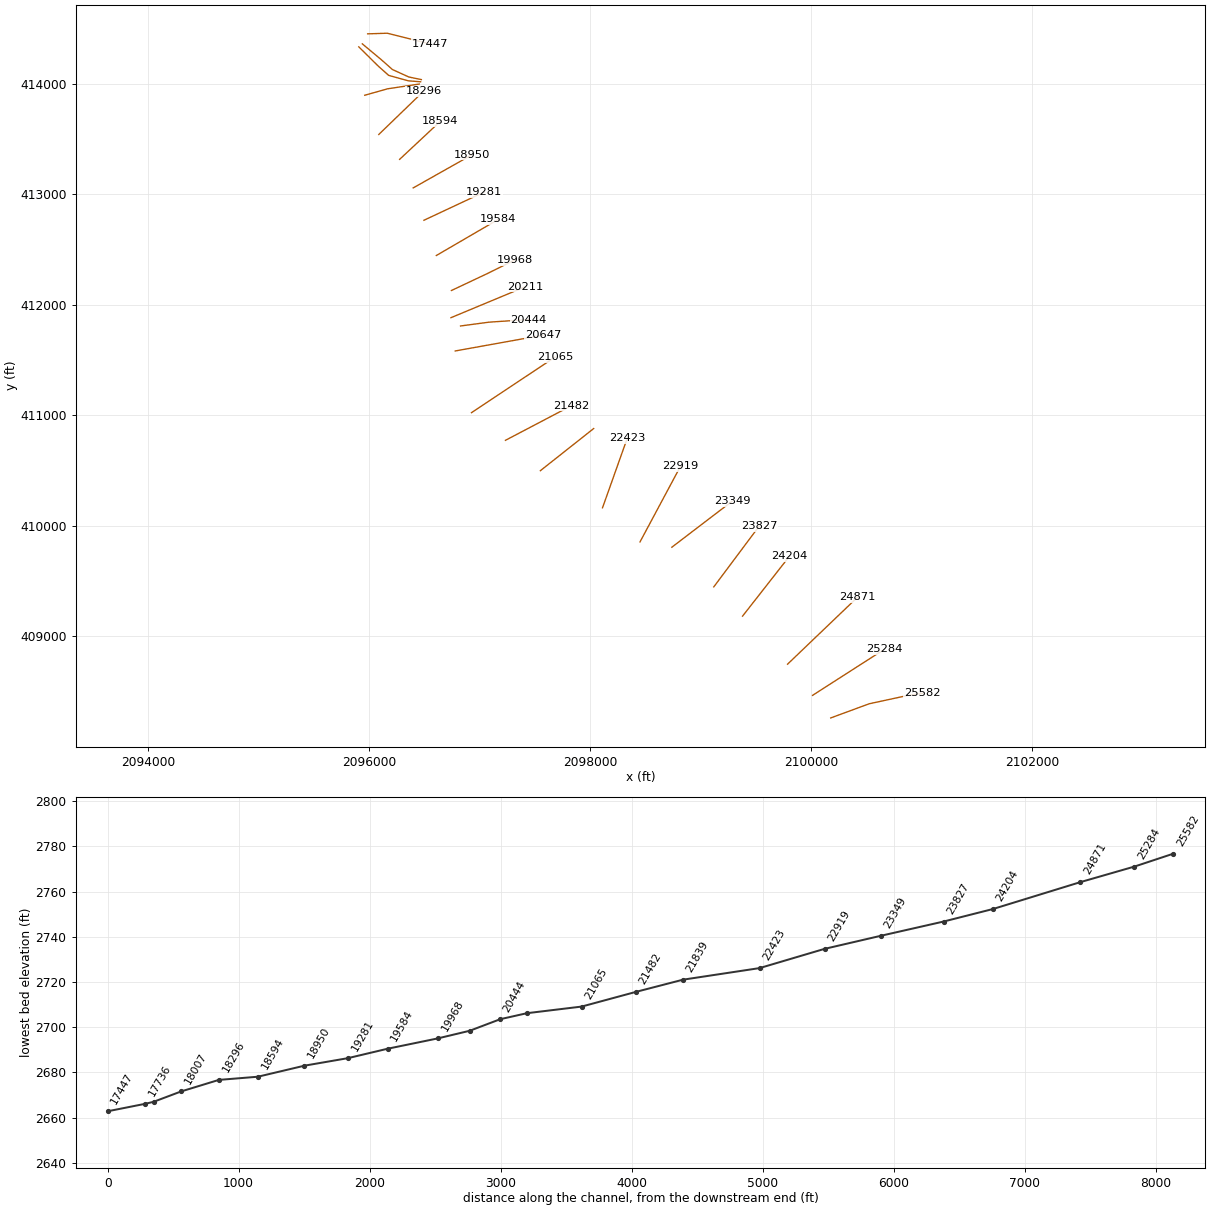
HEC-RAS study LAURELCK4.prj: LAURELCK4

--- LAURELCK4.g01 (geometry) --- (continued)

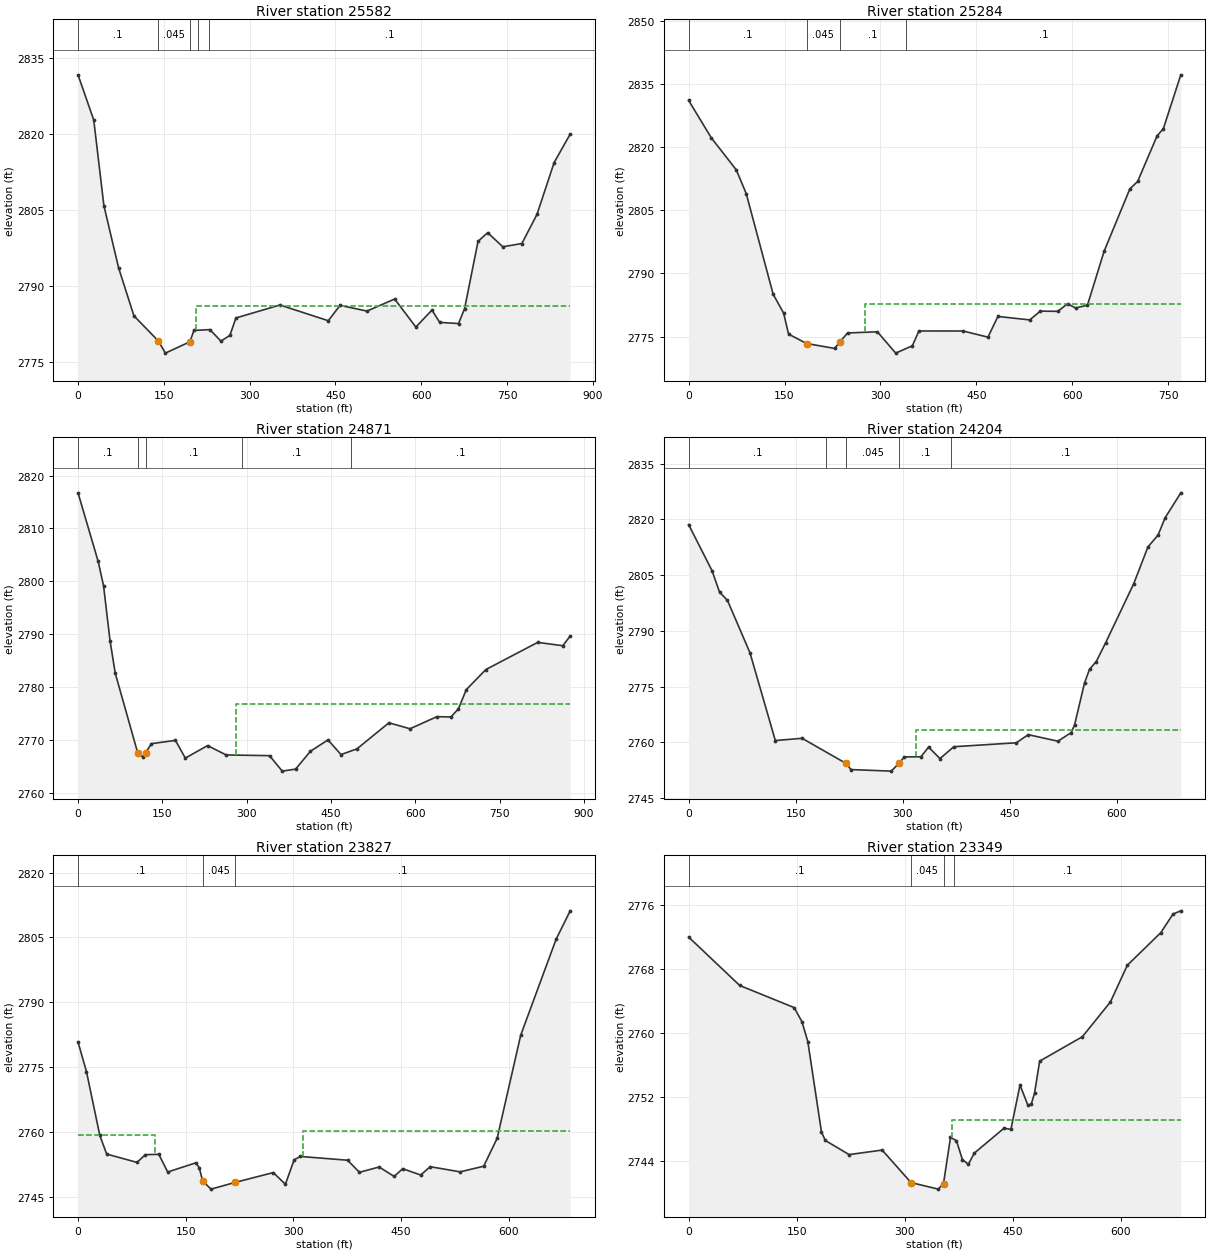
Type RM Length L Ch R = 1 ,25582   ,292.4,297.7,304.2
XS GIS Cut Line= 4
2100176.03818256408261.0171621142100523.95513764408389.142233953
2100866.66344172408463.100419372 2101004.1631667408483.933711037
#Sta/Elev= 30
       0 2831.64    27.5 2822.73    45.2 2805.86    70.9  2793.6    97.7 2784.13
   140.6 2779.15   152.7 2776.77   195.6 2779.01   202.6 2781.24   230.5 2781.41
   249.8 2779.14   265.5 2780.27     276  2783.7   352.9 2786.26   437.5 2783.16
   458.1 2786.19   505.1 2785.06   553.6 2787.44   590.6 2781.91   618.8 2785.27
   632.2 2782.83   665.2  2782.6   675.8 2785.55   699.3 2798.81   716.1 2800.51
   742.7 2797.74   775.9 2798.38   802.4 2804.13   832.3 2814.34   860.4 2819.96
#Mann= 5 ,-1 , 0
       0      .1       0   140.6    .045       0   195.6      .1       0
  209.78      .1       0  228.16      .1       0
#XS Ineff= 2 , 0
                             206         2786.09
Permanent Ineff=
       F       F
Bank Sta=140.6,195.6
XS Rating Curve= 0 ,0
Exp/Cntr=0.3,0.1

Type RM Length L Ch R = 1 ,25284   ,403.9,412.9,421
XS GIS Cut Line= 2
2100011.45485029408465.1837485282100659.37153345408880.808901533
#Sta/Elev= 30
       0 2831.16    35.5 2822.25    74.5 2814.65    90.1 2808.99   132.2 2785.05
   148.5 2780.59   156.3 2775.57   184.5 2773.34   228.3 2772.17  236.582773.723
   248.6 2775.85   295.2 2776.12   323.9 2771.05   349.9  2772.8   360.2 2776.32
   429.2 2776.31   468.2 2774.85   483.7 2779.78   533.5 2778.95     550 2781.04
   577.3 2780.99   592.8 2782.81   605.1 2781.78   623.8 2782.46   649.9 2795.31
   690.1 2810.11   702.3 2811.89   732.7 2822.73   742.5 2824.44   769.8 2837.25
#Mann= 4 ,-1 , 0
       0      .1       0   184.5    .045       0  236.58      .1       0
  340.73      .1       0
#XS Ineff= 2 , 0
                          275.27         2782.66
Permanent Ineff=
       F       F
Bank Sta=184.5,236.58
XS Rating Curve= 0 ,0
Exp/Cntr=0.3,0.1

Type RM Length L Ch R = 1 ,24871   ,644.4,667.5,672.3
XS GIS Cut Line= 2
2099785.41330764408747.4755067832100417.70502204409352.683942035
#Sta/Elev= 30
       0 2816.73    35.8 2803.78    45.4 2799.18    56.9 2788.83    66.2 2782.65
  105.992767.672     115 2766.88  120.312767.658   130.6 2769.35   173.3 2769.97
   190.8 2766.62   230.3 2768.98   263.4 2767.22   340.6 2767.08   363.2 2764.16
   386.9 2764.54   413.3 2767.91   444.5 2770.06   467.7 2767.29     496 2768.36
   552.9 2773.29   590.4 2772.16   638.3 2774.45   663.1 2774.39   676.5 2775.92
   690.5 2779.55   725.2 2783.34   817.5 2788.48   862.1 2787.85   875.3 2789.68
#Mann= 5 ,-1 , 0
       0      .1       0  105.99    .045       0  120.31      .1       0
  291.75      .1       0  485.43      .1       0
#XS Ineff= 2 , 0
                           280.3         2776.78
Permanent Ineff=
       F       F
Bank Sta=105.99,120.31
XS Rating Curve= 0 ,0
Exp/Cntr=0.3,0.1

Type RM Length L Ch R = 1 ,24204   ,372.8,376.7,376.3
XS GIS Cut Line= 2
2099378.12179938409181.8502942032099803.12160555409724.558854446
#Sta/Elev= 30
       0 2818.62    32.7 2806.24    43.3 2800.45    54.4 2798.21    85.9 2784.12
   121.4 2760.49   158.9  2761.1   220.3 2754.35   227.4 2752.68   283.9 2752.26
   295.1 2754.49   302.1 2756.08   325.4 2756.13     336 2758.72     352 2755.64
   371.4 2758.83     459 2759.89   475.6 2762.08   517.1 2760.32   535.8 2762.63
   540.5  2764.7   554.5 2776.02   561.5 2779.69   570.9 2781.77     584  2786.8
   623.4 2802.73   643.3 2812.62   657.4 2815.79   667.3 2820.45   689.3 2827.18
#Mann= 5 ,-1 , 0
       0      .1       0  192.94      .1       0   220.3    .045       0
   295.1      .1       0  367.72      .1       0
#XS Ineff= 2 , 0
                           318.9         2763.27
Permanent Ineff=
       F       F
Bank Sta=220.3,295.1
XS Rating Curve= 0 ,0
Exp/Cntr=0.3,0.1

Type RM Length L Ch R = 1 ,23827   ,484.2,477.8,471.7
XS GIS Cut Line= 2
2099117.70499739409446.4337545342099528.12149939409995.391974196
#Sta/Elev= 30
       0 2780.78    11.8 2773.89    30.3 2759.18    39.9 2754.83    82.1 2752.91
    93.8 2754.69   112.5 2754.78   124.9 2750.68   164.1 2752.81   168.8 2751.69
   173.5 2748.61   185.2 2746.72  218.782748.275   271.9 2750.55   288.8 2747.85
     301 2753.52   309.7 2754.28   375.4 2753.41   391.9 2750.61   419.3 2751.84
   440.3 2749.66   452.1 2751.45   477.2 2749.99   490.5 2751.91   532.1 2750.72
   564.9 2752.02   583.7  2758.5   616.5 2782.36   665.8 2804.57   685.4 2811.14
#Mann= 3 ,-1 , 0
       0      .1       0   173.5    .045       0  218.78      .1       0
#XS Ineff= 2 , 0
          107.75  2759.2  312.96          2760.1
Permanent Ineff=
       F       F
Bank Sta=173.5,218.78
XS Rating Curve= 0 ,0
Exp/Cntr=0.3,0.1

Type RM Length L Ch R = 1 ,23349   ,420.6,430.6,439.4
XS GIS Cut Line= 3
 2098738.5516631409805.2981104292099163.53823903410129.767033532
2099282.28832963410219.350515783
#Sta/Elev= 30
       0 2772.04    70.9 2765.97   146.6 2763.19   157.4 2761.41   165.5 2758.93
   184.4 2747.61   189.8 2746.53   222.8 2744.76   268.7 2745.33   308.8 2741.25
   346.6 2740.43   353.9 2741.13   363.6 2746.91   371.9 2746.51   380.1 2744.14
   388.4 2743.54   396.6 2744.94   437.9 2748.07   447.5 2747.92   460.1 2753.48
   470.9    2751   475.6 2751.05   480.3 2752.46   487.4 2756.48   546.7 2759.54
   585.7 2763.91   609.1  2768.5   655.7  2772.6   672.6 2774.93   683.4 2775.33
#Mann= 4 ,-1 , 0
       0      .1       0   308.8    .045       0   353.9      .1       0
  368.14      .1       0
#XS Ineff= 2 , 0
                          365.87         2749.14
Permanent Ineff=
       F       F
Bank Sta=308.8,353.9
XS Rating Curve= 0 ,0
Exp/Cntr=0.3,0.1

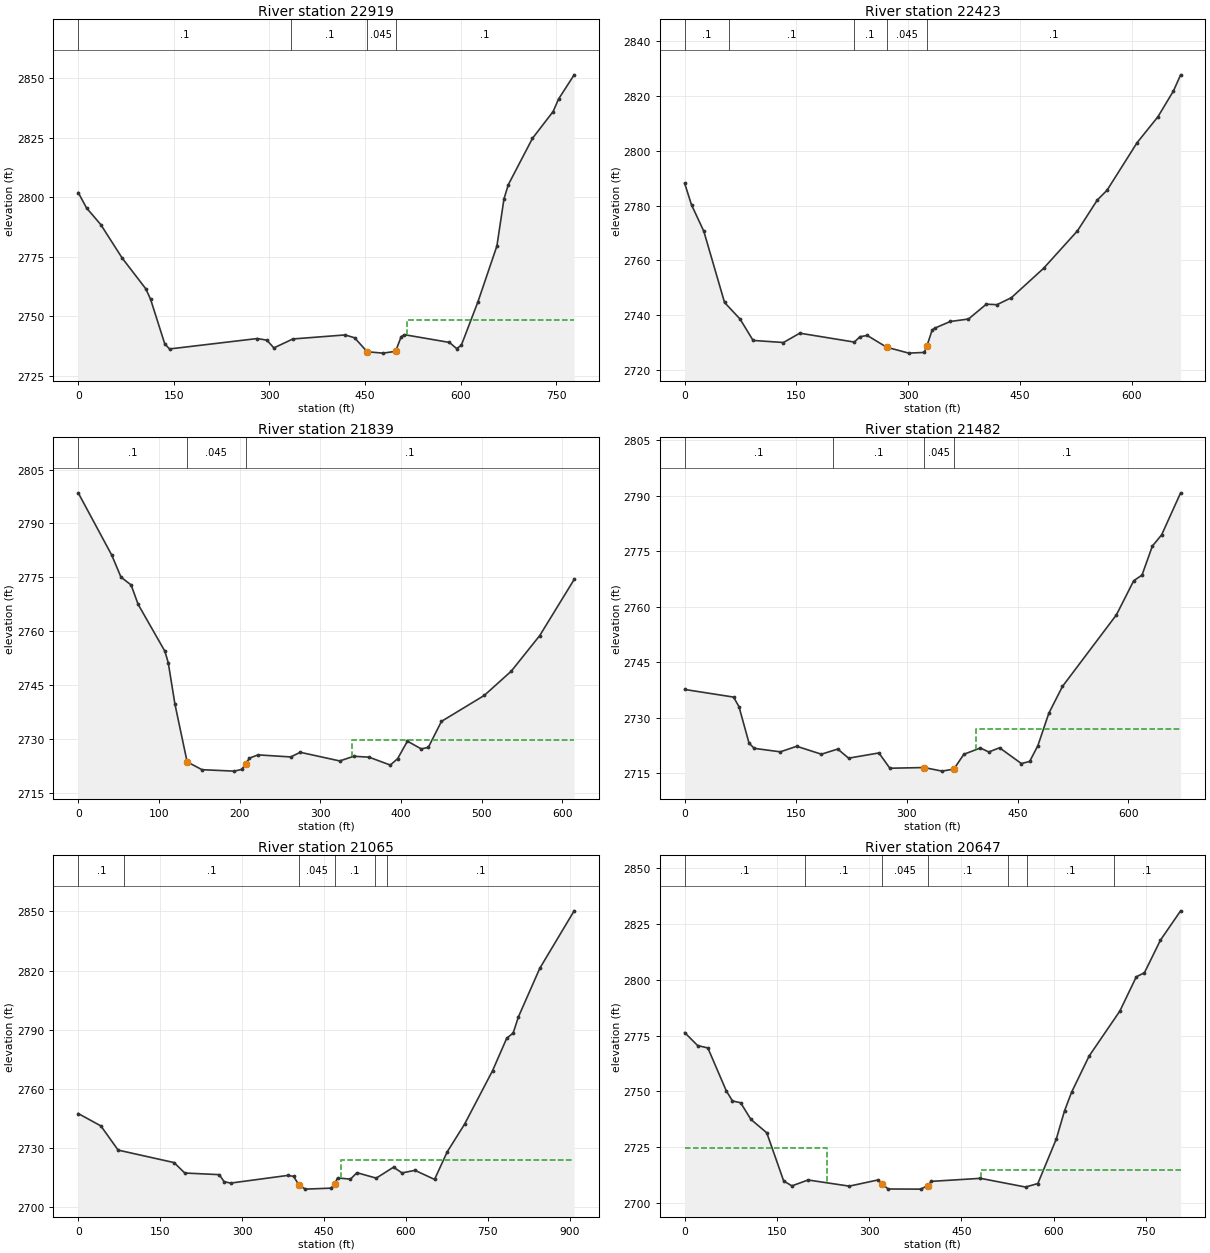
Type RM Length L Ch R = 1 ,22919   ,491.8,495.9,498.6
XS GIS Cut Line= 2
2098450.42085011409853.2190913312098817.70494121410539.142199025
#Sta/Elev= 30
       0 2801.98    13.1  2795.5    35.4 2788.53    68.9 2774.53   106.1 2761.58
   113.5 2757.25   135.8 2738.51   143.3 2736.38     281 2740.75   295.9 2740.07
     307 2736.82   336.8 2740.57   418.7 2742.26   433.6 2741.07   453.4  2735.2
   478.2 2734.63   497.9 2735.38   506.7  2741.5   511.7 2742.37   582.4 2739.12
   593.6 2736.56     601 2737.87   627.1 2756.12   656.9 2779.56     668 2799.31
   674.8 2805.27   712.7  2824.7   745.1 2835.94   753.6 2841.16   778.1 2851.33
#Mann= 4 ,-1 , 0
       0      .1       0  334.41      .1       0   453.4    .045       0
   497.9      .1       0
#XS Ineff= 2 , 0
                          516.47         2748.51
Permanent Ineff=
       F       F
Bank Sta=453.4,497.9
XS Rating Curve= 0 ,0
Exp/Cntr=0.3,0.1

Type RM Length L Ch R = 1 ,22423   ,608.3,584.1,567.4
XS GIS Cut Line= 2
2098111.45504138410162.0586356222098334.37159029 410789.14202711
#Sta/Elev= 30
       0 2788.15     9.2 2780.28    25.7 2770.64    53.5 2744.63    74.4 2738.54
    91.8 2730.76   132.5    2730   154.5 2733.41   227.6 2730.16   235.3 2732.13
     245 2732.58   270.9  2728.3   300.7 2726.12   321.6 2726.38   324.9 2728.64
   332.1 2734.56   335.5 2735.24   356.4 2737.68   380.8 2738.58   404.8 2744.01
   419.1 2743.83   438.4 2746.38   481.6 2757.11   527.1 2770.82   553.8 2782.11
   566.7 2785.62   607.1 2803.03     635 2812.48   655.9 2821.94   665.5 2827.82
#Mann= 5 ,-1 , 0
       0      .1       0   59.17      .1       0   227.1      .1       0
   270.9    .045       0   324.9      .1       0
Bank Sta=270.9,324.9
XS Rating Curve= 0 ,0
Exp/Cntr=0.3,0.1

Type RM Length L Ch R = 1 ,21839   ,368,357.2,352.1
XS GIS Cut Line= 2
2097548.95485404410497.4752876162098031.24654037 410878.72550936
#Sta/Elev= 30
       0 2798.54    41.6 2781.17      53 2775.06    65.6 2772.86    74.3 2767.46
   107.4 2754.42   111.6 2751.23   119.9 2739.67     135  2723.6   153.4  2721.4
   193.4    2721   202.8 2721.48   207.4    2723   212.3 2724.61   222.9 2725.53
   263.5 2724.95   275.2 2726.25   324.2 2723.84   341.6 2725.14   360.5 2724.89
   386.9 2722.69     396 2724.48   408.1 2729.35   425.2  2727.2     434 2727.61
   450.3 2734.86   503.3 2742.08   536.8 2748.84   572.1 2758.76   614.8  2774.4
#Mann= 3 ,-1 , 0
       0      .1       0     135    .045       0   207.4      .1       0
#XS Ineff= 2 , 0
                          339.14         2729.54
Permanent Ineff=
       F       F
Bank Sta=135,207.4
XS Rating Curve= 0 ,0
Exp/Cntr=0.3,0.1

Type RM Length L Ch R = 1 ,21482   ,415.8,416.3,418.2
XS GIS Cut Line= 2
2097233.32982913410772.4753937872097827.07995397 411083.93376036
#Sta/Elev= 30
       0 2737.68    66.1 2735.62    73.4 2733.04      87  2723.2      94 2721.78
   129.3 2720.84   151.5 2722.34   184.8  2720.2     207 2721.59   221.6 2719.13
   262.6 2720.54   277.4 2716.41  323.862716.599     348 2715.63  363.942716.188
   377.4 2720.17   399.7 2721.88   411.2  2720.8   425.7 2721.94   455.2 2717.68
   466.4 2718.24   477.5 2722.51   492.3 2731.25   510.7 2738.48   583.7 2757.83
   607.1 2767.04   618.3 2768.56   632.3 2776.39   644.9 2779.45   670.5 2790.77
#Mann= 4 ,-1 , 0
       0      .1       0     200      .1       0  323.86    .045       0
  363.94      .1       0
#XS Ineff= 2 , 0
                          394.17         2727.01
Permanent Ineff=
       F       F
Bank Sta=323.86,363.94
XS Rating Curve= 0 ,0
Exp/Cntr=0.3,0.1

Type RM Length L Ch R = 1 ,21065   ,435.3,418.7,407
XS GIS Cut Line= 2
2096926.03844896411022.4755499512097682.28824881411525.600527942
#Sta/Elev= 30
       0 2747.46    41.5 2741.17    73.1  2728.9   175.5 2722.57   195.2 2717.27
   258.3 2716.45   267.2 2712.89   279.1 2712.16   384.4 2716.08   394.4 2715.55
   404.1 2711.32   415.9  2709.1   463.2  2709.6  469.662711.742     475 2714.79
   498.6 2714.16   510.5 2717.43   545.8 2714.68   577.5 2720.23   593.1 2717.32
   616.8 2718.63   652.6 2714.03   675.9 2728.05   707.5 2742.01   758.8 2769.14
   784.8 2785.65   796.6 2788.29   806.2 2796.47   845.4 2821.15   908.3 2850.28
#Mann= 6 ,-1 , 0
       0      .1       0   84.51      .1       0   404.1    .045       0
  469.66      .1       0  543.26      .1       0  566.04      .1       0
#XS Ineff= 2 , 0
                          482.17         2724.12
Permanent Ineff=
       F       F
Bank Sta=404.1,469.66
XS Rating Curve= 0 ,0
Exp/Cntr=0.3,0.1

Type RM Length L Ch R = 1 ,20647   ,212.4,203,198.7
XS GIS Cut Line= 2
2096779.16341463411580.8087508682097572.91346756411723.517126858
#Sta/Elev= 30
       0 2776.36      21 2770.56    37.7 2769.47    67.7 2750.22    77.7 2745.72
      91 2744.88   107.7 2737.43   133.5 2731.42     161 2709.81   174.4 2707.62
   200.7 2710.26   267.7  2707.5   314.4 2710.28     321 2708.46     331 2706.22
   383.6 2706.16   395.8 2707.78     401 2709.64     481    2711   554.3  2707.1
   574.3 2708.66   604.4  2728.7   617.7 2741.26   629.1 2749.57   657.7 2765.84
   707.7 2786.03   734.4 2801.36   747.7 2803.22   773.7 2817.82   806.5 2830.96
#Mann= 7 ,-1 , 0
       0      .1       0  195.59      .1       0     321    .045       0
   395.8      .1       0  525.66      .1       0  556.88      .1       0
   697.6      .1       0
#XS Ineff= 2 , 0
          231.47 2724.45  482.17         2714.77
Permanent Ineff=
       F       F
Bank Sta=321,395.8
XS Rating Curve= 0 ,0
Exp/Cntr=0.3,0.1

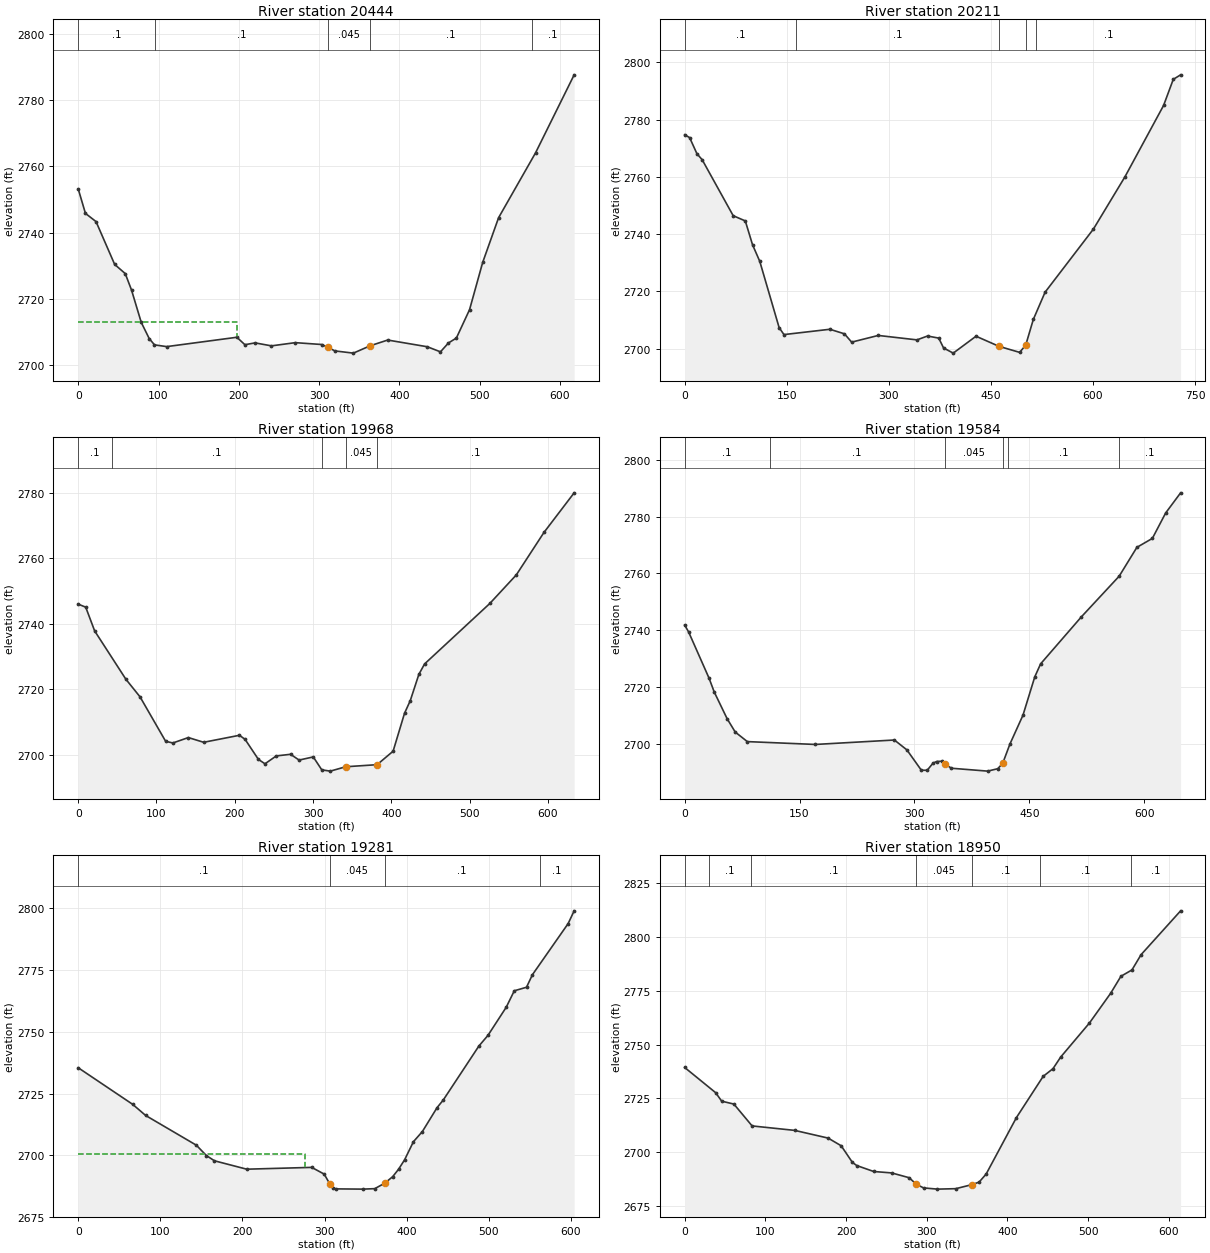
Type RM Length L Ch R = 1 ,20444   ,222.3,232.4,232.4
XS GIS Cut Line= 3
2096827.07998547411806.8502935322097084.37179372411841.225552872
2097441.66340196411865.183838278
#Sta/Elev= 30
       0 2753.21       9  2745.8    22.2 2743.31    45.4 2730.36    58.6 2727.57
    66.4  2722.6    78.5 2712.82    88.4 2707.93      95 2706.01   110.2 2705.48
   197.6 2708.31   207.6 2706.06   220.3 2706.61   240.7 2705.71   270.4 2706.68
   303.3 2706.12  311.162705.246   319.7 2704.18   342.7 2703.51   363.9 2705.76
   385.5 2707.47   434.8 2705.44   451.2  2703.9   461.1 2706.58     471 2708.07
   487.4 2716.65   503.8 2730.98   523.6  2744.5   569.6 2764.11   617.7 2787.73
#Mann= 5 ,-1 , 0
       0      .1       0   96.23      .1       0  311.16    .045       0
   363.9      .1       0  564.81      .1       0
#XS Ineff= 2 , 0
          197.28 2713.07
Permanent Ineff=
       F       F
Bank Sta=311.16,363.9
XS Rating Curve= 0 ,0
Exp/Cntr=0.3,0.1

Type RM Length L Ch R = 1 ,20211   ,242.2,243.6,244.4
XS GIS Cut Line= 2
2096740.62149695411881.850471616 2097413.5384582412162.058900699
#Sta/Elev= 30
       0 2774.74     7.3 2773.73      18  2768.1    25.7 2766.01    71.3 2746.44
    89.1 2744.61    99.7  2736.3   110.4 2730.46   138.8 2707.33   145.9 2704.88
   213.4 2706.74   234.8 2705.15   245.4 2702.24   284.5 2704.58   341.4 2703.03
   356.9 2704.38   373.4 2703.65   380.5  2700.2   394.7  2698.4   428.2 2704.31
   462.1 2700.76   492.4 2698.66   501.3 2701.25   512.4 2710.17   529.7  2719.7
   600.8 2741.79     647    2760   703.9 2784.99   718.1  2794.1   728.9 2795.68
#Mann= 5 ,-1 , 0
       0      .1       0  164.24      .1       0   462.1    .045       0
   501.3      .1       0  516.92      .1       0
Bank Sta=462.1,501.3
XS Rating Curve= 0 ,0
Exp/Cntr=0.3,0.1

Type RM Length L Ch R = 1 ,19968   ,375.2,383.7,385.3
XS GIS Cut Line= 3
2096744.78848338412127.6836413592097068.42202246412280.282089442
2097315.62165928 412402.68374753
#Sta/Elev= 30
       0 2746.03     9.6  2745.1      21 2737.85    60.9 2723.09      79  2717.7
   111.7 2704.13   120.9 2703.62   140.7 2705.27   160.3 2703.83     206 2705.97
   213.2 2704.72   230.2 2698.61   238.6 2697.26   253.1 2699.67   271.3 2700.16
   282.2  2698.4   300.3 2699.36   311.2  2695.4   322.1 2695.02  341.732696.355
  381.86 2696.99   402.3 2701.11   416.9  2712.7   424.2 2716.53   435.2 2724.57
   442.5 2727.76   525.9 2746.24   559.7 2754.96     595 2767.92   633.6 2780.03
#Mann= 5 ,-1 , 0
       0      .1       0   42.82      .1       0  310.89      .1       0
  341.73    .045       0  381.86      .1       0
Bank Sta=341.73,381.86
XS Rating Curve= 0 ,0
Exp/Cntr=0.3,0.1

Type RM Length L Ch R = 1 ,19584   ,306.7,303,300.1
XS GIS Cut Line= 2
2096608.33009487412444.3503308592097167.70496038412770.392001614
#Sta/Elev= 30
       0 2741.83     5.1 2739.45    31.8 2723.17    38.6 2718.28    55.4  2708.9
      66 2704.19    81.8 2700.83   170.6 2699.83   273.8 2701.39   290.1 2697.92
     309 2690.76   316.6 2690.74   324.2 2693.23   328.9 2693.82   335.6 2693.93
   339.4 2693.11   348.1 2691.46   395.6 2690.44   408.7 2691.29   415.2 2693.17
   424.7 2700.01   441.7 2710.14   457.1 2723.63   464.7 2728.19   517.9 2744.73
   567.3 2759.06   590.4  2769.2   610.6 2772.35     628 2781.31   647.5 2788.39
#Mann= 6 ,-1 , 0
       0      .1       0  111.12      .1       0   339.4    .045       0
   415.2      .1       0  422.28      .1       0  566.51      .1       0
Bank Sta=339.4,415.2
XS Rating Curve= 0 ,0
Exp/Cntr=0.3,0.1

Type RM Length L Ch R = 1 ,19281   ,328.4,331,333.8
XS GIS Cut Line= 2
2096495.82999179412763.1003495312097042.70488229413019.350493193
#Sta/Elev= 30
       0 2735.45    66.3 2720.63    82.1 2716.12   143.9 2704.06     156 2699.89
   165.9 2697.75   205.2 2694.35   284.3 2695.08   299.5 2692.36   306.5  2688.3
   310.4 2686.65     314 2686.37   346.6 2686.27   361.1 2686.46   373.1 2688.65
   382.9  2691.3   390.1 2694.33   397.4 2698.13   408.2 2705.49   419.1 2709.61
     437  2719.3   444.5 2722.37   487.9 2744.25     499 2748.59   521.2 2759.97
     531 2766.63   545.9 2768.07   553.1 2773.15   596.6 2793.87   603.9 2799.03
#Mann= 4 ,-1 , 0
       0      .1       0   306.5    .045       0   373.1      .1       0
  561.83      .1       0
#XS Ineff= 2 , 0
          276.12  2700.5
Permanent Ineff=
       F       F
Bank Sta=306.5,373.1
XS Rating Curve= 0 ,0
Exp/Cntr=0.3,0.1

Type RM Length L Ch R = 1 ,18950   ,347.9,355.7,361.8
XS GIS Cut Line= 2
2096398.95485747 413055.808753612096934.37176561413357.892138943
#Sta/Elev= 30
       0 2739.39    38.4 2727.69    45.9 2723.75      61 2722.41    83.6 2712.27
   136.4  2710.2   177.8 2706.63     194 2703.07   207.9 2695.36   213.3 2693.89
   234.3 2691.13   256.6 2690.47   278.3 2688.24     287 2685.26   296.1 2683.52
   313.4 2682.95   336.1 2683.16   356.2 2685.05     365  2686.2   373.7 2689.94
   411.3 2716.17   444.4 2735.26   456.6 2738.84   466.1 2744.21   501.8 2760.03
   528.1 2773.83   540.8 2781.69   554.5 2784.65   565.8 2791.73   614.8 2812.06
#Mann= 7 ,-1 , 0
       0      .1       0   29.85      .1       0   81.69      .1       0
     287    .045       0   356.2      .1       0  440.72      .1       0
  553.78      .1       0
Bank Sta=287,356.2
XS Rating Curve= 0 ,0
Exp/Cntr=0.3,0.1

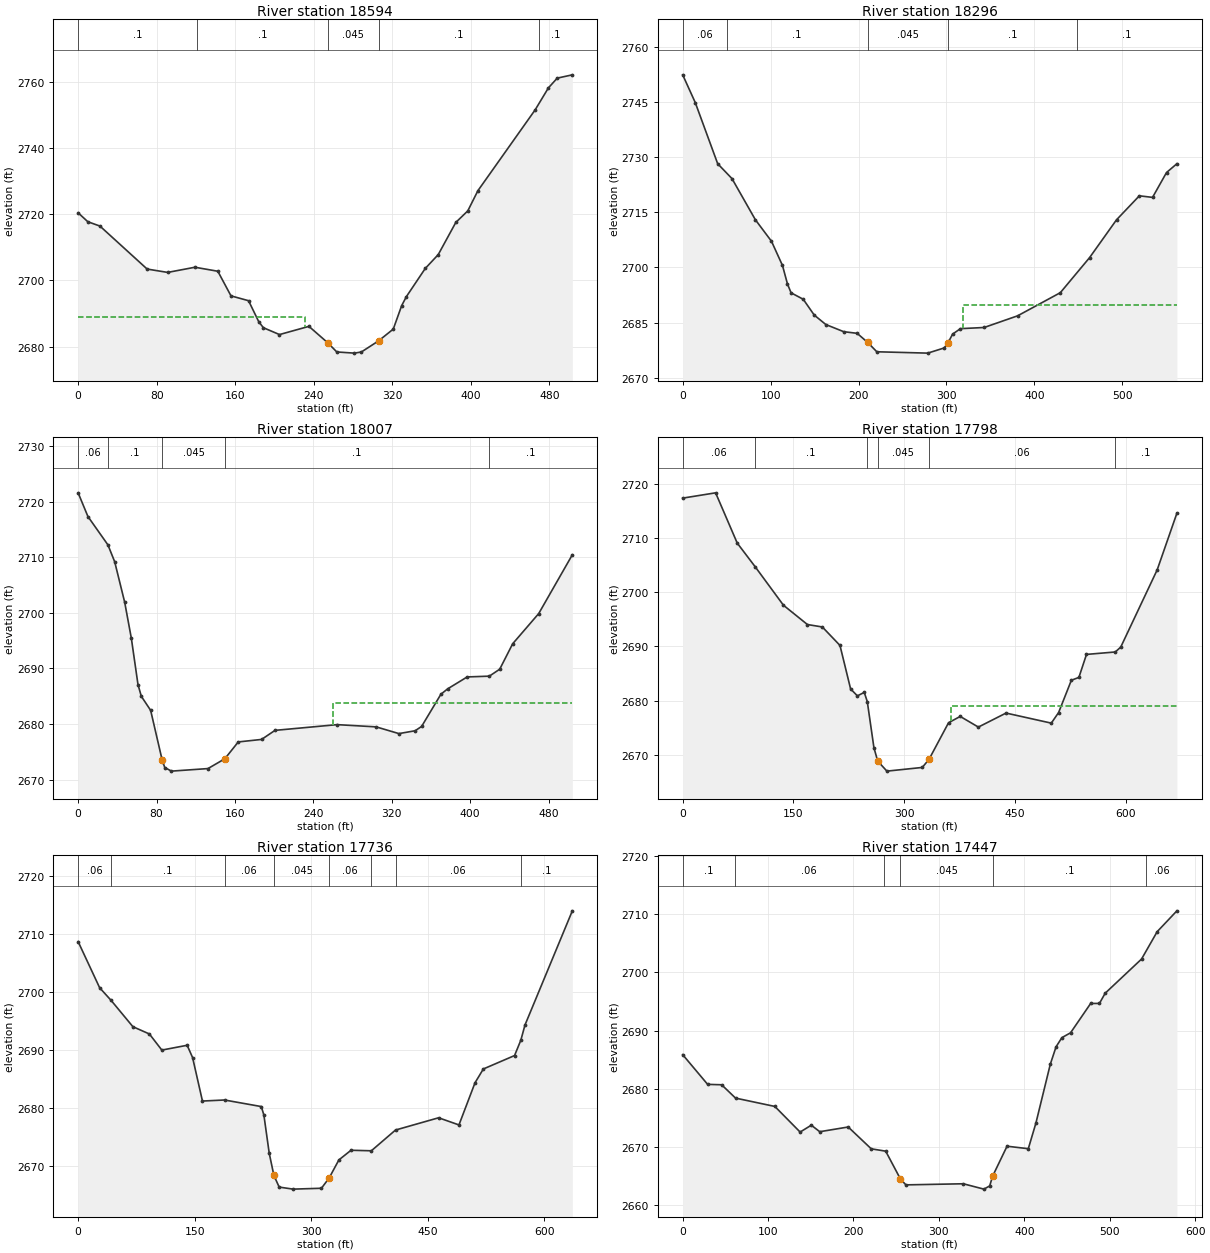
Type RM Length L Ch R = 1 ,18594   ,298.7,298.2,298.8
XS GIS Cut Line= 2
2096276.03843662413314.1422264432096643.74669072 413657.89219512
#Sta/Elev= 30
       0 2720.41     9.9 2717.71    22.2 2716.41    70.3 2703.43    91.2 2702.42
     119 2703.98   142.3 2702.77   155.7 2695.34   173.6 2693.88     184 2687.53
   188.7 2685.73   205.1 2683.66   235.1 2686.14   254.5 2681.12   263.5 2678.41
   281.4 2678.06   288.5  2678.4  305.982681.749     321 2685.31   329.6 2692.42
   334.4 2695.13   353.6 2703.62   366.8 2707.79   384.7  2717.5   396.9 2720.99
   407.2 2727.08   465.6 2751.51     479  2758.1     488 2761.05   503.4 2762.05
#Mann= 5 ,-1 , 0
       0      .1       0  120.83      .1       0   254.5    .045       0
  305.98      .1       0  469.05      .1       0
#XS Ineff= 2 , 0
          231.58 2688.94
Permanent Ineff=
       F       F
Bank Sta=254.5,305.98
XS Rating Curve= 0 ,0
Exp/Cntr=0.3,0.1

Type RM Length L Ch R = 1 ,18296   ,305.9,288.6,275.1
XS GIS Cut Line= 2
2096087.49681896413539.1421045362096491.66333345413929.766979456
#Sta/Elev= 30
       0 2752.54    14.3 2744.97    39.8  2728.3    56.1 2724.23    82.7 2713.01
     101 2707.15   113.5 2700.55   119.2 2695.48   123.3 2693.09   137.1 2691.34
   149.6 2687.03   162.8 2684.45   183.1  2682.5   198.4 2682.05   210.5 2679.55
   220.8 2677.02   278.7 2676.65   297.4 2678.06   301.7 2679.43     307 2681.84
   315.9 2683.32   342.8 2683.64   380.9 2686.82   429.5 2693.13   462.8  2702.7
   493.4    2713   519.4 2719.55   534.4 2719.12   550.3  2725.9   562.1  2728.3
#Mann= 5 ,-1 , 0
       0     .06       0      50      .1       0   210.5    .045       0
   301.7      .1       0  448.63      .1       0
#XS Ineff= 2 , 0
                          318.85         2689.77
Permanent Ineff=
       F       F
Bank Sta=210.5,301.7
XS Rating Curve= 0 ,0
Exp/Cntr=0.3,0.1

Type RM Length L Ch R = 1 ,18007   ,245.6,209.3,179.5
XS GIS Cut Line= 3
2095960.20835963413893.9619329422096167.15282762413952.295149609
2096453.26380396413995.350837782
#Sta/Elev= 30
       0 2721.58      10 2717.32    30.4 2712.22    37.3 2709.19    47.5 2701.91
    54.3 2695.43    61.1 2687.08    64.5 2684.98      74 2682.46    85.7 2673.56
    88.4 2672.18    95.2 2671.53   132.5 2671.99   149.7 2673.75   163.4 2676.78
   187.2 2677.23   200.9 2678.86   264.3 2679.89   304.1 2679.49   327.3 2678.28
   343.9 2678.79   350.5 2679.57   370.2 2685.36   377.1 2686.33     397 2688.47
   419.6 2688.61   430.2 2689.86   443.4 2694.43     470 2699.87   504.3 2710.44
#Mann= 5 ,-1 , 0
       0     .06       0    30.4      .1       0    85.7    .045       0
   149.7      .1       0   419.6      .1       0
#XS Ineff= 2 , 0
                           260.1         2683.79
Permanent Ineff=
       F       F
Bank Sta=85.7,149.7
XS Rating Curve= 0 ,0
Exp/Cntr=0.5,0.3

Type RM Length L Ch R = 1 ,17798   ,62.1,61.9,62.1
XS GIS Cut Line= 5
2095906.56246954414331.8091543612096081.04177937414159.066061527
2096176.52780887414073.9966778612096354.47922462414024.517446116
2096465.59022287414015.837017283
#Sta/Elev= 30
       0 2717.41    44.6 2718.39    73.9  2709.1    98.2 2704.73   136.5 2697.62
     169 2694.05   189.2  2693.6   213.1 2690.19   227.5 2682.15   236.7 2680.87
     246 2681.51   250.1 2679.82   259.1 2671.29   264.2 2668.82   276.7 2666.96
   324.6 2667.64   333.8 2669.15   360.2  2675.9     376 2677.07   400.6  2675.1
   438.1 2677.69   499.4 2675.83   509.3 2677.78   526.6 2683.75   536.8 2684.28
   547.1 2688.53   586.1 2688.98   593.5 2689.88   642.9 2704.16   669.6 2714.63
#Mann= 6 ,-1 , 0
       0     .06       0    98.2      .1       0   250.1     .06       0
   264.2    .045       0   333.8     .06       0   586.1      .1       0
#XS Ineff= 2 , 0
           234.2    2679   363.8            2679
Permanent Ineff=
       F       F
Bank Sta=264.2,333.8
XS Rating Curve= 0 ,0
Exp/Cntr=0.5,0.3

Type RM Length L Ch R = 1 ,17736   ,265.5,288.7,307.9
XS GIS Cut Line= 5
2095938.68051553 414358.718877452096110.55549988414215.489505112
2096210.38207188414126.9480155262096358.81943905414059.239817619
 2096472.5347628414035.802200451
#Sta/Elev= 30
       0  2708.7    27.7 2700.76    42.5 2698.58    70.5 2694.06    91.8  2692.8
   107.8 2690.03   140.4 2690.86   147.4 2688.74   160.1 2681.26   188.5 2681.44
   235.9 2680.31   239.2 2678.85   246.1 2672.26   252.1 2668.45   258.9 2666.45
   276.8  2666.1   313.3 2666.25   323.2 2668.01   335.8 2671.13   351.4 2672.79
   377.6  2672.7   408.7 2676.27   464.2 2678.38   490.4 2677.15   511.1 2684.41
   521.8 2686.78     562 2689.09   570.1 2691.74   575.4 2694.34   636.4    2714
#Mann= 8 ,-1 , 0
       0     .06       0    42.5      .1       0   188.5     .06       0
   252.1    .045       0   323.2     .06       0   377.6      .1       0
   408.7     .06       0   570.1      .1       0
Bank Sta=252.1,323.2
XS Rating Curve= 0 ,0
Exp/Cntr=0.5,0.3

Type RM Length L Ch R = 1 ,17447   ,270.6,290.2,313
XS GIS Cut Line= 3
2095986.59708637 414449.517580362096164.37494603414455.073015451
2096553.26393205414357.850768954
#Sta/Elev= 30
       0 2685.86    29.2 2680.76    45.6 2680.69    61.9  2678.4   107.9 2676.97
   137.5 2672.57   150.6 2673.75   160.5 2672.63   193.8 2673.44   220.8 2669.69
   237.7 2669.29  255.012664.498   261.4  2663.5   328.6 2663.69   352.7 2662.77
   359.5 2663.32   362.8 2664.96   379.8 2670.14   404.7 2669.71   413.6 2674.11
   430.5 2684.24   437.2 2687.21     444 2688.78   454.2 2689.62   477.7 2694.65
     488 2694.66   494.7 2696.41   537.3 2702.28   555.6 2706.98   578.7 2710.56
#Mann= 6 ,-1 , 0
       0      .1       0   61.15     .06       0  235.26      .1       0
  255.01    .045       0   362.8      .1       0  542.55     .06       0
Bank Sta=255.01,362.8
XS Rating Curve= 0 ,0
Exp/Cntr=0.3,0.1