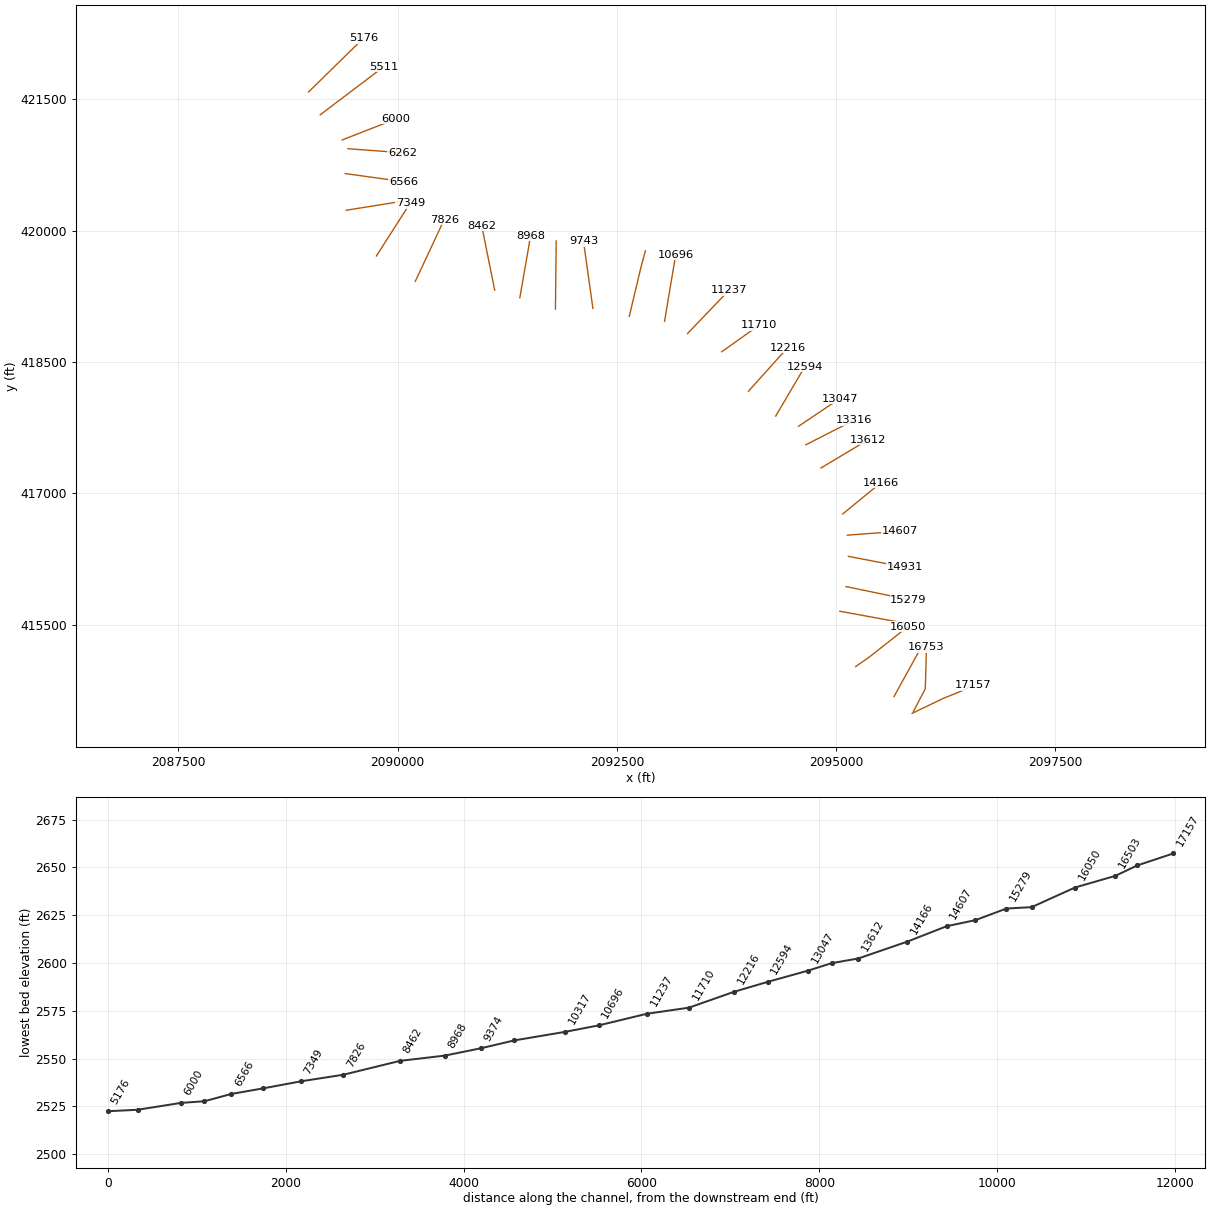
HEC-RAS study LAURELCK4.prj: LAURELCK4

--- LAURELCK4.g01 (geometry) --- (continued)

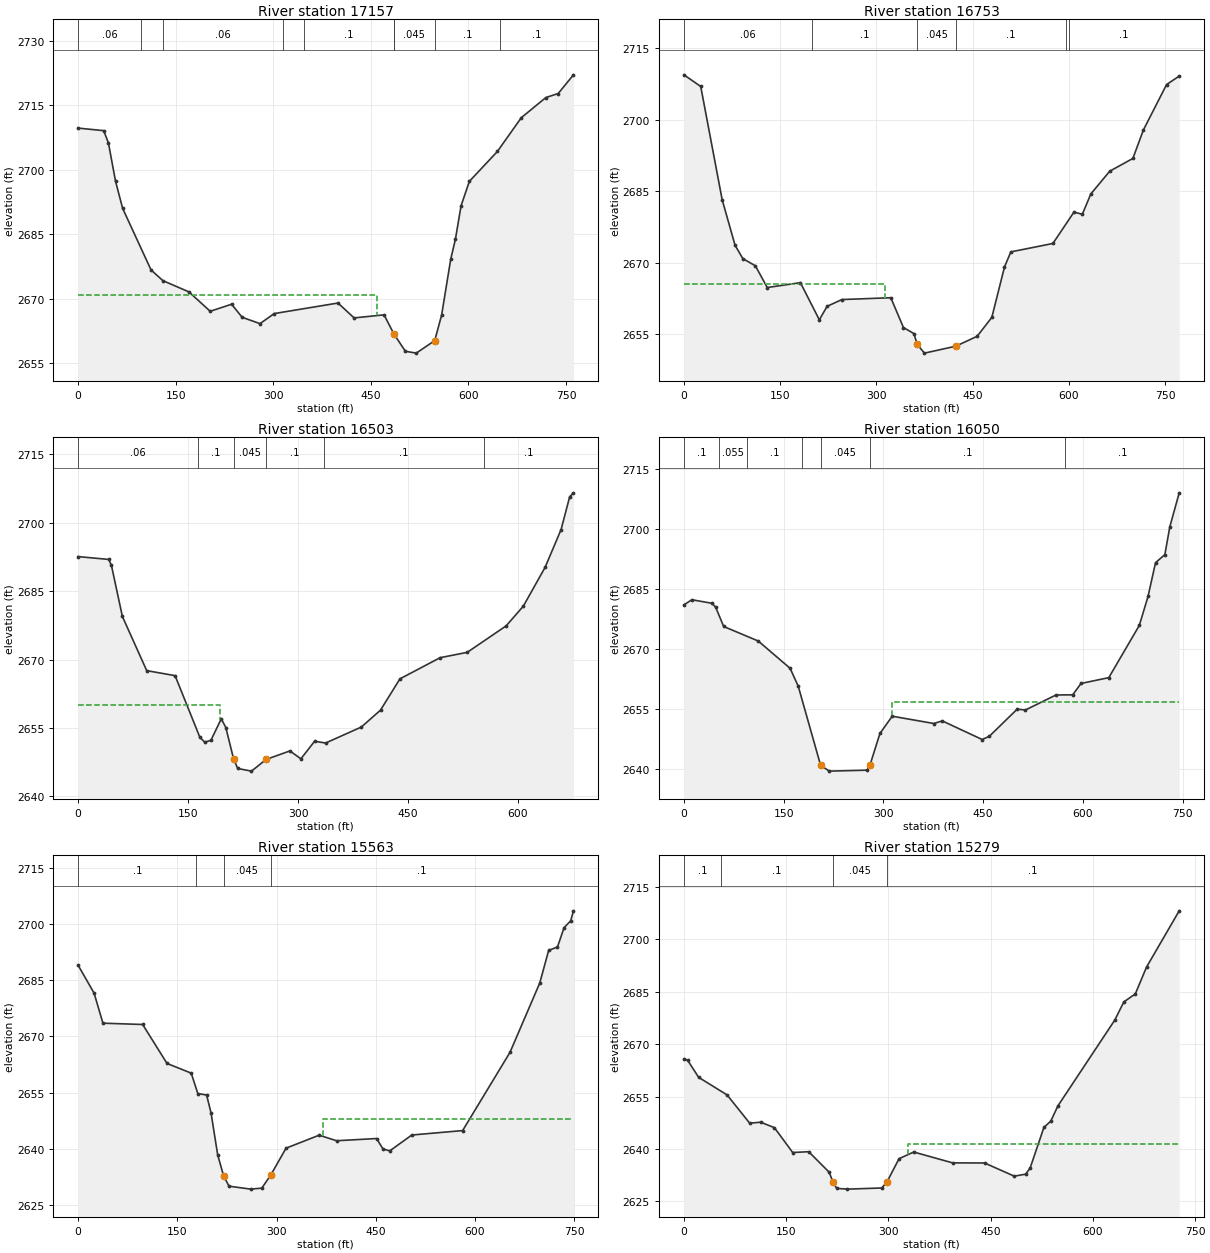
Type RM Length L Ch R = 1 ,17157   ,372.6,404.3,442
XS GIS Cut Line= 4
2095865.62160653414491.2255021932096215.62156272414659.975492775
2096436.45511055414749.5586469472096556.24653763 414811.01718545
#Sta/Elev= 30
       0 2709.65    39.2 2709.06    46.5  2706.2    57.4 2697.32    68.3    2691
     112 2676.67   130.2 2674.18   170.3 2671.56     203 2667.05   235.9 2668.69
   252.1 2665.65   279.6 2664.18   301.4 2666.52   399.5 2668.97   424.2 2665.51
   470.3 2666.22   485.5 2661.75   503.1 2657.75   519.8 2657.32   548.2 2660.23
   558.8 2666.18   572.9 2679.26     580  2683.8   588.7  2691.6   601.5 2697.28
   644.5 2704.21   681.3 2712.07   719.1 2716.76     738 2717.69   761.5 2722.04
#Mann= 9 ,-1 , 0
       0     .06       0   96.98      .1       0  129.77     .06       0
  315.45      .1       0  347.88      .1       0  485.08      .1       0
   485.5    .045       0   548.2      .1       0  648.48      .1       0
#XS Ineff= 2 , 0
          459.54  2670.8
Permanent Ineff=
       F       F
Bank Sta=485.5,548.2
XS Rating Curve= 0 ,0
Exp/Cntr=0.3,0.1

Type RM Length L Ch R = 1 ,16753   ,260.4,249.9,238.7
XS GIS Cut Line= 3
2095879.16324612414509.9754647022096015.62163463414772.475595862
 2096029.1632742415248.516966611
#Sta/Elev= 30
       0 2709.41    26.2 2706.97    59.6 2683.24    79.7 2673.69    91.8  2670.9
   111.4 2669.38   129.9 2664.83   181.6 2665.85   211.1 2658.06   223.2 2660.89
   246.3 2662.31   322.5 2662.69   342.2 2656.45   358.6 2655.17   363.7 2652.89
     375 2651.08     424 2652.54     457  2654.6     480 2658.57   499.7 2669.12
   509.6  2672.3   575.2 2674.06     608 2680.63   621.1 2680.19   634.3 2684.44
   663.8 2689.21   699.9 2691.89   716.3 2697.86   752.4 2707.37   772.1 2709.15
#Mann= 6 ,-1 , 0
       0     .06       0  199.92      .1       0   363.7    .045       0
     424      .1       0  596.05      .1       0  600.67      .1       0
#XS Ineff= 2 , 0
           314.2  2665.6
Permanent Ineff=
       F       F
Bank Sta=363.7,424
XS Rating Curve= 0 ,0
Exp/Cntr=0.3,0.1

Type RM Length L Ch R = 1 ,16503   ,464.5,452.6,439.8
XS GIS Cut Line= 2
2095659.37169096414683.933778197 2095985.4133617415275.600573868
#Sta/Elev= 30
       0 2692.59    41.6 2691.97    45.3  2690.7    60.3 2679.46    93.5 2667.59
   132.2 2666.49     166 2652.97   172.7 2651.91     181  2652.3   195.2 2657.03
   201.4 2655.12   211.9  2648.3   217.6 2646.14   236.4 2645.56  256.352648.119
   288.8 2649.99   303.8 2648.26   322.5 2652.11   337.5 2651.72   386.2 2655.22
   412.4 2658.93   438.9 2665.79   493.7 2670.43   530.7  2671.6   583.8 2677.41
   607.2 2681.72   636.9 2690.23   658.7 2698.51   670.4 2705.69   675.6 2706.57
#Mann= 6 ,-1 , 0
       0     .06       0   163.7      .1       0   211.9    .045       0
  256.35      .1       0  334.73      .1       0  553.49      .1       0
#XS Ineff= 2 , 0
          194.11 2660.14
Permanent Ineff=
       F       F
Bank Sta=211.9,256.35
XS Rating Curve= 0 ,0
Exp/Cntr=0.3,0.1

Type RM Length L Ch R = 1 ,16050   ,514.9,487.1,453.3
XS GIS Cut Line= 3
 2095221.8715817415025.6004177032095368.74661604 415127.68387495
2095813.53837737415477.683831111
#Sta/Elev= 30
       0    2681    11.9 2682.28    42.3 2681.39    47.8 2680.38    59.8  2675.6
   111.8 2671.97   159.7 2665.16   171.9 2660.71   205.6 2640.93   218.7 2639.49
   275.7 2639.73   279.9 2641.05   294.8 2648.89   313.3  2653.2   375.9 2651.38
   388.5 2652.03   448.6 2647.38   459.4  2648.2   501.2 2654.96   513.7 2654.76
   559.6  2658.5   584.7 2658.54   597.3 2661.38     639 2662.83   684.9 2675.87
     698 2683.09   709.3 2691.54   723.3 2693.53   730.8  2700.5   744.9 2708.97
#Mann= 7 ,-1 , 0
       0      .1       0   53.35    .055       0    95.1      .1       0
  178.25      .1       0   205.6    .045       0   279.9      .1       0
  573.67      .1       0
#XS Ineff= 2 , 0
                           313.3         2656.73
Permanent Ineff=
       F       F
Bank Sta=205.6,279.9
XS Rating Curve= 0 ,0
Exp/Cntr=0.3,0.1

Type RM Length L Ch R = 1 ,15563   ,284.9,284.1,283.7
XS GIS Cut Line= 2
2095040.62161613415656.8504675332095777.08011696415521.433743611
#Sta/Elev= 30
       0 2688.97    24.1 2681.54    37.4 2673.53    97.5 2673.18   134.3 2662.78
   170.9 2660.19   180.9 2654.74   194.2 2654.34   200.9 2649.53   210.9 2638.38
   219.8  2632.8     228 2630.01   260.7 2629.22   277.6 2629.49   290.9 2632.91
   314.3 2640.16   364.3 2643.62   390.7 2642.14   451.1 2642.73   460.9 2639.93
   471.1 2639.44   504.4 2643.67   581.2 2644.85   652.8 2665.73   697.9 2684.28
   711.3 2692.97   724.6 2693.86   734.6 2699.04   744.6 2700.87   748.8 2703.53
#Mann= 4 ,-1 , 0
       0      .1       0  178.71      .1       0   219.8    .045       0
   290.9      .1       0
#XS Ineff= 2 , 0
                          370.35         2648.04
Permanent Ineff=
       F       F
Bank Sta=219.8,290.9
XS Rating Curve= 0 ,0
Exp/Cntr=0.3,0.1

Type RM Length L Ch R = 1 ,15279   ,348.1,348.4,348.9
XS GIS Cut Line= 2
2095111.45513588415938.1005612022095822.91335863415790.183862284
#Sta/Elev= 30
       0 2665.78     5.5 2665.39    21.6 2660.51    63.3 2655.48    96.5 2647.38
   112.7 2647.66   132.8 2646.09   159.6 2638.98   183.1 2639.21   213.1 2633.34
   218.6 2630.55   224.2  2628.7     240 2628.49   290.3 2628.82   298.1 2630.63
   315.7 2637.22   337.2 2639.12   394.2 2636.01   441.1 2635.98   484.6 2632.21
   501.6 2632.78   508.1 2634.61   528.2 2646.17   538.3 2647.97   548.7 2652.33
   632.1 2676.89   645.5 2682.12   662.3 2684.41   678.8 2692.11   726.7 2708.21
#Mann= 4 ,-1 , 0
       0      .1       0   54.52      .1       0   218.6    .045       0
   298.1      .1       0
#XS Ineff= 2 , 0
                          328.69         2641.48
Permanent Ineff=
       F       F
Bank Sta=218.6,298.1
XS Rating Curve= 0 ,0
Exp/Cntr=0.3,0.1

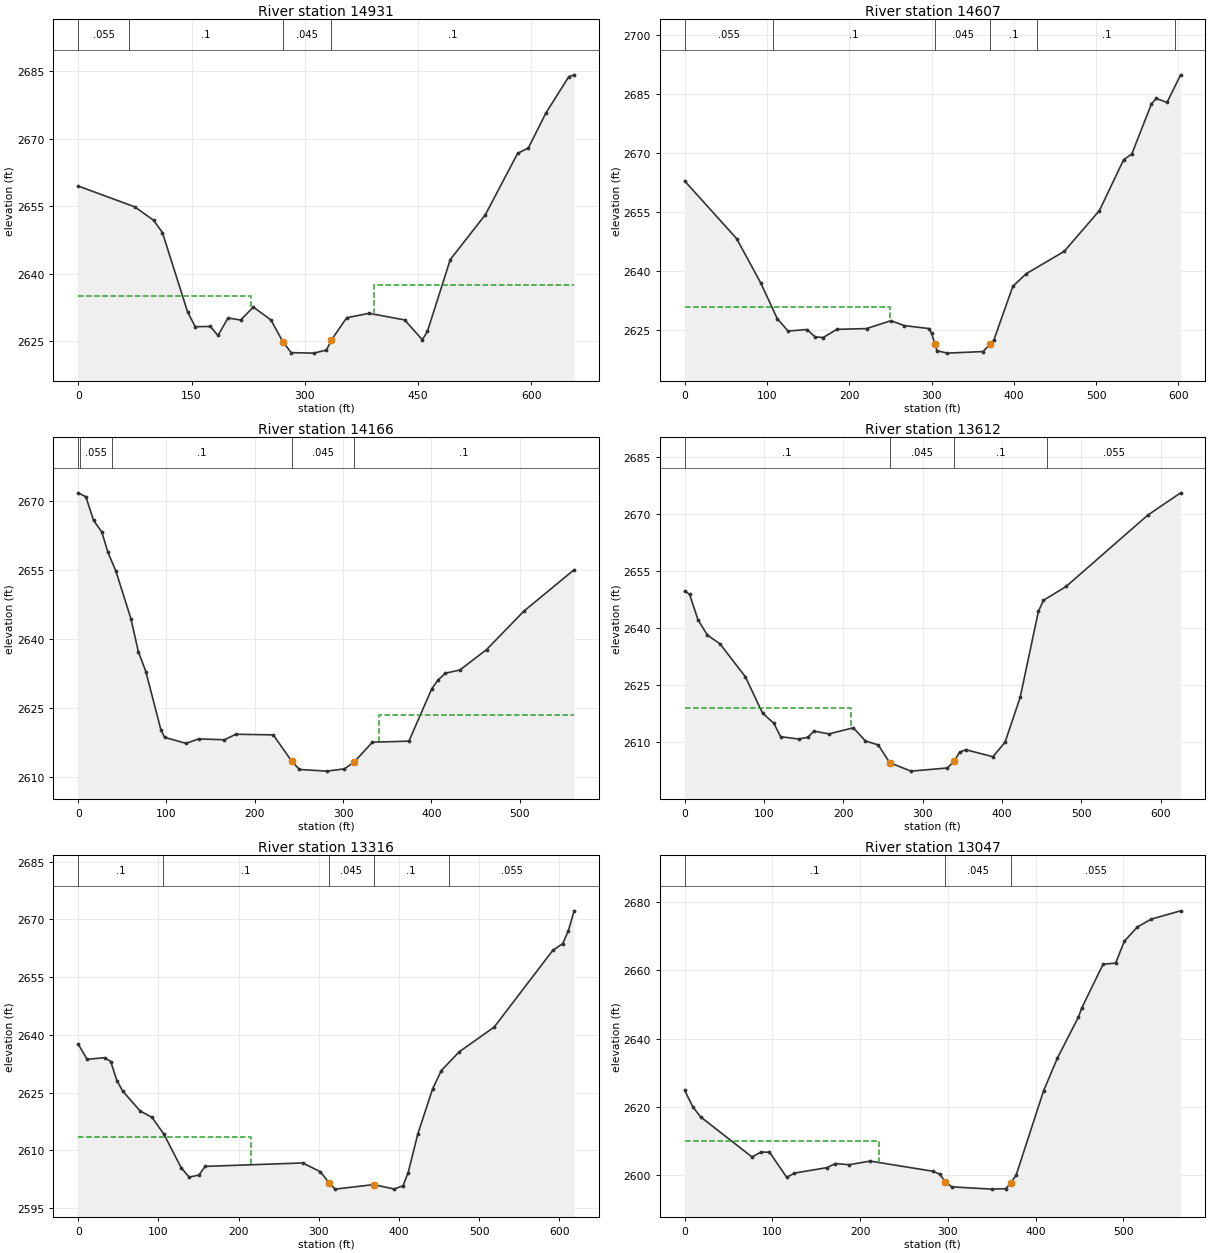
Type RM Length L Ch R = 1 ,14931   ,316.7,323.7,334.2
XS GIS Cut Line= 2
2095138.53841504 416282.892194452095783.33010447416158.933780953
#Sta/Elev= 30
       0 2659.47    74.7 2654.87    99.9 2651.87   111.5 2649.15   144.9 2631.51
   154.9 2628.29     175 2628.33     185 2626.33   198.4 2630.22   215.1 2629.75
   231.8 2632.64   255.2 2629.77   270.8 2624.99   281.9 2622.53     312 2622.42
   328.7 2623.11   335.3 2625.33   335.3 2625.36   355.4 2630.26   385.1 2631.25
   432.2 2629.78   455.6 2625.38   462.3 2627.23   492.6 2643.17   539.1 2653.13
   581.8 2666.72   595.9  2667.9   619.3 2675.69   649.4  2683.7   656.6 2684.13
#Mann= 4 ,-1 , 0
       0    .055       0   67.14      .1       0   270.8    .045       0
   335.3      .1       0
#XS Ineff= 2 , 0
          228.98 2635.13   391.4          2637.5
Permanent Ineff=
       F       F
Bank Sta=270.8,335.3
XS Rating Curve= 0 ,0
Exp/Cntr=0.3,0.1

Type RM Length L Ch R = 1 ,14607   ,420.7,441,462.6
XS GIS Cut Line= 2
2095126.03844005416524.5587058662095727.07988888416569.350282952
#Sta/Elev= 30
       0 2662.93    63.1 2648.32    92.6 2636.99   112.5    2628   125.6 2624.86
   148.7 2625.24   158.5 2623.36   168.4 2623.21   184.8 2625.28     221 2625.48
   250.6 2627.47   267.1 2626.22   296.7 2625.49     300 2624.28   303.9 2621.65
   306.6 2619.87   319.2 2619.25   362.5 2619.65   371.3 2621.52   375.7 2622.55
   398.8 2636.21   415.1 2639.41   461.2 2645.06     504 2655.42   533.5 2668.35
   543.4 2669.77   567.2 2682.47   573.1 2683.86   586.2 2682.87   602.7 2689.86
#Mann= 6 ,-1 , 0
       0    .055       0  107.59      .1       0   303.9    .045       0
   371.3      .1       0  428.77      .1       0  596.38      .1       0
#XS Ineff= 2 , 0
          249.18 2631.01
Permanent Ineff=
       F       F
Bank Sta=303.9,371.3
XS Rating Curve= 0 ,0
Exp/Cntr=0.3,0.1

Type RM Length L Ch R = 1 ,14166   ,557.9,554.1,549.7
XS GIS Cut Line= 2
 2095073.9548828416766.2255453622095508.32999828417122.475489035
#Sta/Elev= 30
       0 2671.73     8.7 2670.86    17.4 2665.74    26.7 2663.23    33.7 2658.77
    42.7 2654.69    59.7 2644.37    68.1 2637.21    76.6 2632.86    93.6 2620.24
    97.8 2618.55   122.3 2617.23   136.3 2618.21   165.7 2618.02   178.5 2619.22
   220.9 2619.09   242.1 2613.31   250.6 2611.56   281.5  2611.2   301.5 2611.69
   312.6 2613.18   333.3  2617.5   374.6 2617.72   400.5 2629.11   407.6 2631.02
     416  2632.5   432.4  2633.2   462.6 2637.64   504.6 2645.95   561.8 2655.01
#Mann= 5 ,-1 , 0
       0      .1       0    2.05    .055       0   38.49      .1       0
   242.1    .045       0   312.6      .1       0
#XS Ineff= 2 , 0
                          341.26         2623.37
Permanent Ineff=
       F       F
Bank Sta=242.1,312.6
XS Rating Curve= 0 ,0
Exp/Cntr=0.3,0.1

Type RM Length L Ch R = 1 ,13612   ,297.4,295.7,291.3
XS GIS Cut Line= 2
2094826.03838387417291.2254796182095362.49662855417612.058827445
#Sta/Elev= 30
       0  2649.8     6.2 2648.88    16.8 2642.19    28.7 2638.13    44.4 2635.89
    76.6 2627.16    98.1 2617.64   112.5 2614.91   120.9 2611.42   143.6  2610.8
   155.3 2611.27   162.9 2612.89   181.8 2612.15   212.6 2613.76   227.9 2610.29
     244 2609.24   258.4 2604.57   285.3 2602.35   331.1 2603.18   339.7 2604.97
   346.4 2607.27   354.1    2608   388.5 2606.15   403.8 2609.96   422.9 2621.79
   445.8 2644.38   452.2 2647.31   480.9 2650.98   583.5 2669.71   625.1 2675.61
#Mann= 4 ,-1 , 0
       0      .1       0   258.4    .045       0   339.7      .1       0
  456.07    .055       0
#XS Ineff= 2 , 0
          209.17 2618.99
Permanent Ineff=
       F       F
Bank Sta=258.4,339.7
XS Rating Curve= 0 ,0
Exp/Cntr=0.3,0.1

Type RM Length L Ch R = 1 ,13316   ,262.6,269.2,273
XS GIS Cut Line= 2
2094654.16339955417555.8089399492095205.20494837417837.059033617
#Sta/Elev= 30
       0 2637.63    11.1 2633.68    33.2  2634.1    40.6  2633.1    48.2 2628.16
    55.5 2625.42    77.4 2620.23    92.1 2618.59   106.9 2614.23   128.7 2605.42
   138.4 2603.06   150.6 2603.62   158.4 2605.86     280 2606.75   302.1 2604.47
   313.1 2601.54   320.5 2599.95   368.4 2601.12   394.2 2599.98   405.2 2600.83
   411.6 2604.23   423.6 2614.24   442.1 2625.99     453 2630.76   475.2  2635.6
   518.9 2642.04     592 2661.97   604.4 2663.73   611.4 2667.03   618.7 2672.25
#Mann= 5 ,-1 , 0
       0      .1       0  105.15      .1       0   313.1    .045       0
   368.4      .1       0  462.23    .055       0
#XS Ineff= 2 , 0
           215.9 2613.52
Permanent Ineff=
       F       F
Bank Sta=313.1,368.4
XS Rating Curve= 0 ,0
Exp/Cntr=0.3,0.1

Type RM Length L Ch R = 1 ,13047   ,422.9,453.3,462.1
XS GIS Cut Line= 2
2094570.82990479417767.2671784462095039.57995155418082.892203361
#Sta/Elev= 30
       0 2624.88     9.5 2620.01    18.2 2617.13    76.8  2605.4    86.8 2606.83
    96.6 2606.81   116.3 2599.45   125.1 2600.68   162.4  2602.3   171.7 2603.47
   187.5 2603.14   211.3  2604.2   282.5 2601.24   290.4  2600.4   297.1 2598.11
   304.2 2596.66   349.7 2595.99   365.9 2596.12   371.8 2597.87   377.7 2600.09
     409 2624.82   424.8 2634.41   448.6 2646.32   452.5 2649.06   476.8 2661.86
     491 2662.15     501 2668.58   515.8 2672.74   531.6 2675.04   565.1 2677.47
#Mann= 3 ,-1 , 0
       0      .1       0   297.1    .045       0   371.8    .055       0
#XS Ineff= 2 , 0
          221.73 2610.03
Permanent Ineff=
       F       F
Bank Sta=297.1,371.8
XS Rating Curve= 0 ,0
Exp/Cntr=0.3,0.1

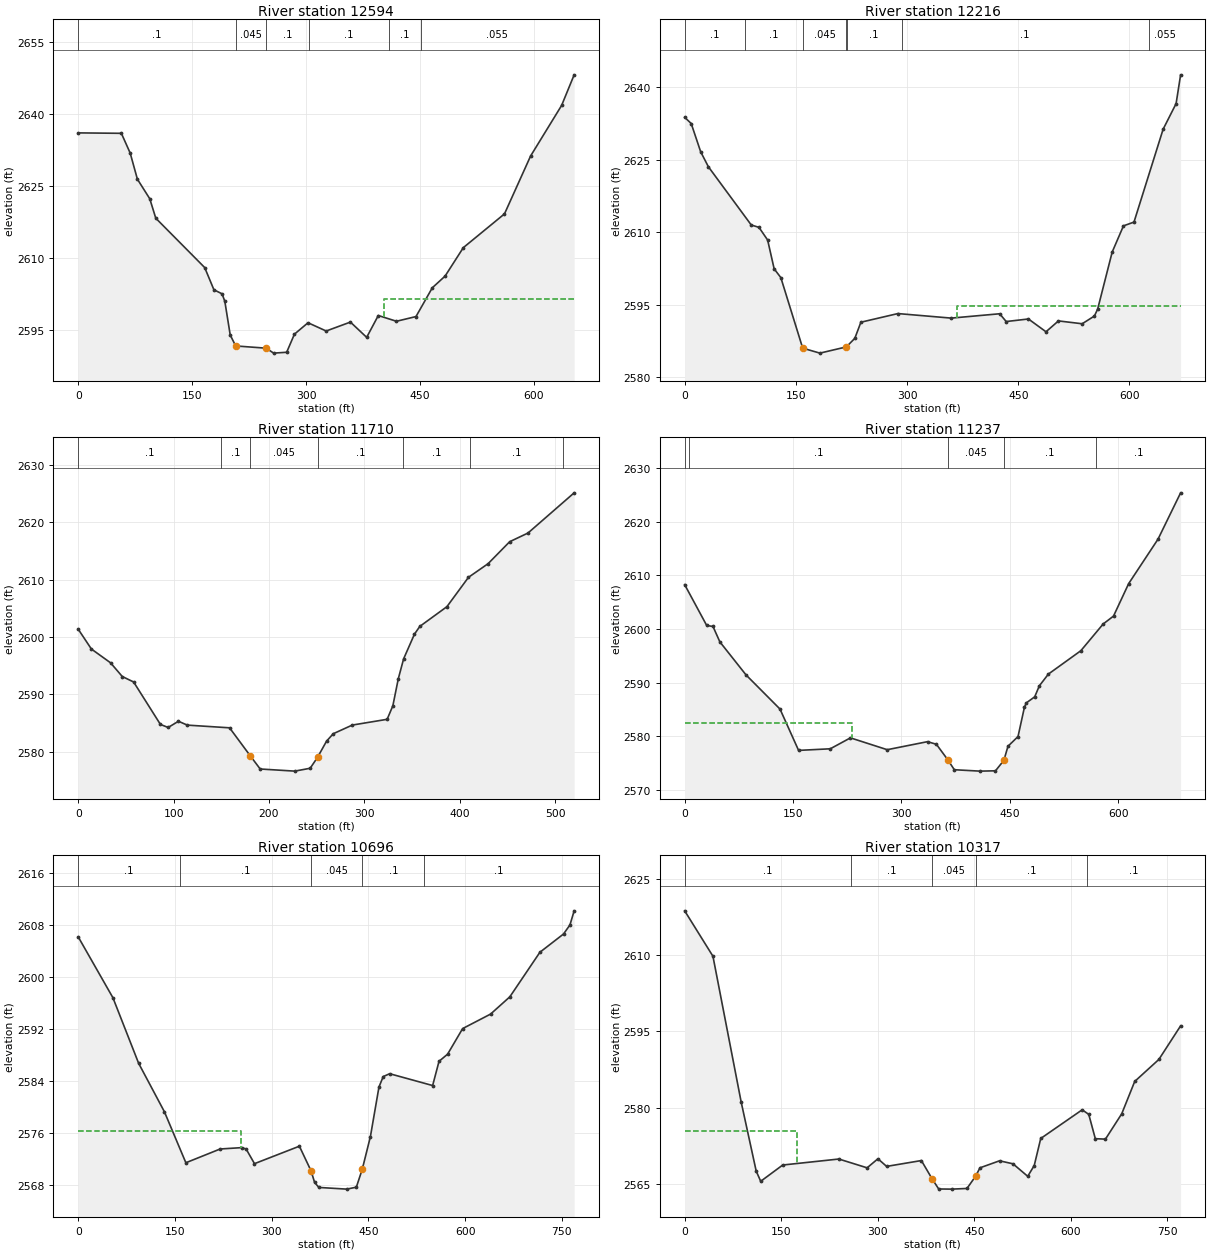
Type RM Length L Ch R = 1 ,12594   ,382.3,377.6,373.1
XS GIS Cut Line= 2
2094310.41343087417883.9339398592094641.66342455418446.433799118
#Sta/Elev= 30
       0 2636.02    56.8 2635.93    68.4 2631.82    77.9 2626.37    94.2 2622.29
   102.1 2618.24   166.5 2607.95   178.6 2603.33   189.4 2602.47     193  2600.9
   200.1 2593.89  207.272591.617  247.51 2591.15   257.2 2590.12   274.4  2590.3
   284.6 2594.07   302.5 2596.45   326.4 2594.73   358.3 2596.59   379.7 2593.41
     395 2597.96   418.9 2596.76   444.6 2597.74   466.1 2603.74   482.9 2606.17
   506.9  2612.1   561.1 2619.14   595.5 2631.21   636.3 2641.74   652.8 2648.12
#Mann= 6 ,-1 , 0
       0      .1       0  207.27    .045       0  247.51      .1       0
  303.84      .1       0  408.74      .1       0  450.67    .055       0
#XS Ineff= 2 , 0
                          402.09         2601.31
Permanent Ineff=
       F       F
Bank Sta=207.27,247.51
XS Rating Curve= 0 ,0
Exp/Cntr=0.3,0.1

Type RM Length L Ch R = 1 ,12216   ,513,506.3,501.5
XS GIS Cut Line= 2
2093999.99672887 418167.267034622094446.87181938418665.183689699
#Sta/Elev= 30
       0 2633.76     8.8 2632.48    21.6 2626.62      32 2623.52    89.8 2611.47
   100.2 2610.98   111.9 2608.36   120.7 2602.39   129.7 2600.58   159.2 2585.97
   182.4 2584.94   218.1 2586.23   229.5    2588   237.7 2591.34   287.6 2593.13
   359.6 2592.19   424.9 2593.09   433.7 2591.48   463.7 2592.01   487.4 2589.36
   504.2 2591.61   536.2 2591.02   552.7 2592.62   557.1 2594.06   576.7 2605.87
   591.9 2611.29   606.1 2612.07   645.4  2631.3   662.9  2636.6     669 2642.56
#Mann= 7 ,-1 , 0
       0      .1       0   81.33      .1       0   159.2    .045       0
   218.1      .1       0   218.5      .1       0  292.68      .1       0
  626.08    .055       0
#XS Ineff= 2 , 0
                          368.02          2594.6
Permanent Ineff=
       F       F
Bank Sta=159.2,218.1
XS Rating Curve= 0 ,0
Exp/Cntr=0.3,0.1

Type RM Length L Ch R = 1 ,11710   ,465.2,472.9,479.7
XS GIS Cut Line= 2
2093694.78834981418617.2671188712094118.74681947418918.308839619
#Sta/Elev= 30
       0 2601.36    13.8 2597.91    33.9 2595.51    46.2 2593.12    58.1 2592.17
    86.2 2584.78    94.3 2584.25   105.1 2585.33   114.4 2584.66   158.7 2584.19
   180.3 2579.34   190.8 2577.02   227.1 2576.65   243.2 2577.15   250.9 2579.04
   260.4 2581.87   267.4 2583.16   287.4 2584.67   323.9 2585.67   329.9 2588.02
   335.6 2592.72   341.2  2596.2   352.6 2600.51   358.2 2601.85   386.6 2605.28
   409.2 2610.39   429.8 2612.77   452.4 2616.59   471.6  2618.1     520  2625.1
#Mann= 7 ,-1 , 0
       0      .1       0  149.62      .1       0   180.3    .045       0
   250.9      .1       0  340.81      .1       0  411.04      .1       0
  507.82      .1       0
Bank Sta=180.3,250.9
XS Rating Curve= 0 ,0
Exp/Cntr=0.3,0.1

Type RM Length L Ch R = 1 ,11237   ,516.6,541.2,563.7
XS GIS Cut Line= 2
2093305.20513946418825.6003636122093780.20484564419321.433689535
#Sta/Elev= 30
       0 2608.27    30.5 2600.65    39.2 2600.46    48.7 2597.59      85 2591.41
     132 2585.04   157.7 2577.33   201.6 2577.63   229.5 2579.67   280.4 2577.46
   336.2 2578.96   348.5 2578.47   364.1 2575.61   373.3 2573.72   408.7 2573.46
   430.3 2573.52   441.9 2575.47   447.6  2578.1   461.5 2579.92   470.4 2585.41
   473.1 2586.21   484.6 2587.33     491 2589.38   503.5 2591.57   548.5 2595.94
   579.4 2600.93   593.7  2602.4   614.7 2608.47   655.3 2616.76   686.6 2625.41
#Mann= 5 ,-1 , 0
       0      .1       0    6.54      .1       0   364.1    .045       0
   441.9      .1       0   569.3      .1       0
#XS Ineff= 2 , 0
          231.35 2582.36
Permanent Ineff=
       F       F
Bank Sta=364.1,441.9
XS Rating Curve= 0 ,0
Exp/Cntr=0.3,0.1

Type RM Length L Ch R = 1 ,10696   ,380.2,378.4,375.4
XS GIS Cut Line= 2
 2093042.7050083418965.1837458612093169.78841555419723.517202944
#Sta/Elev= 30
       0 2606.22    53.8 2596.85    93.7 2586.75   133.6  2579.3   166.9 2571.44
   220.1 2573.56   253.4 2573.77   260.3 2573.56   273.3  2571.3   342.9 2573.99
     361 2570.19   366.5 2568.41   373.1 2567.64   416.4 2567.38   431.2 2567.68
   440.4 2570.44     453 2575.46   466.3 2583.11   472.9 2584.71   482.9 2585.15
   549.5 2583.33   559.4 2587.06   572.7 2588.16     596  2592.1   639.3 2594.33
   669.2 2596.99   715.8 2603.85   752.4 2606.66   762.4 2608.06   768.9 2610.23
#Mann= 5 ,-1 , 0
       0      .1       0   157.4      .1       0     361    .045       0
   440.4      .1       0  536.54      .1       0
#XS Ineff= 2 , 0
          252.18 2576.36
Permanent Ineff=
       F       F
Bank Sta=361,440.4
XS Rating Curve= 0 ,0
Exp/Cntr=0.3,0.1

Type RM Length L Ch R = 1 ,10317   ,558.7,574.1,586
XS GIS Cut Line= 3
2092640.62149489419021.4336333722092777.07988337 419595.39213112
 2092824.9967823419769.350444615
#Sta/Elev= 30
       0 2618.73    43.9  2609.8    87.8  2581.1   111.1 2567.55   118.1 2565.54
   152.3 2568.74   239.5 2569.92   283.4 2568.19   300.2 2569.97   313.7 2568.47
   367.7 2569.62   384.5 2565.99   394.6 2564.03   414.9    2564   438.5 2564.13
     452 2566.55   458.7 2568.19   489.1 2569.57     510 2568.98   532.9 2566.52
     543 2568.64   553.1 2573.96   617.5  2579.6   627.7  2578.7   637.9 2573.92
   653.6 2573.83   678.9 2578.81   699.1 2585.18   736.6  2589.5   770.4 2596.11
#Mann= 5 ,-1 , 0
       0      .1       0  258.91      .1       0   384.5    .045       0
     452      .1       0  625.67      .1       0
#XS Ineff= 2 , 0
          175.21 2575.45
Permanent Ineff=
       F       F
Bank Sta=384.5,452
XS Rating Curve= 0 ,0
Exp/Cntr=0.3,0.1

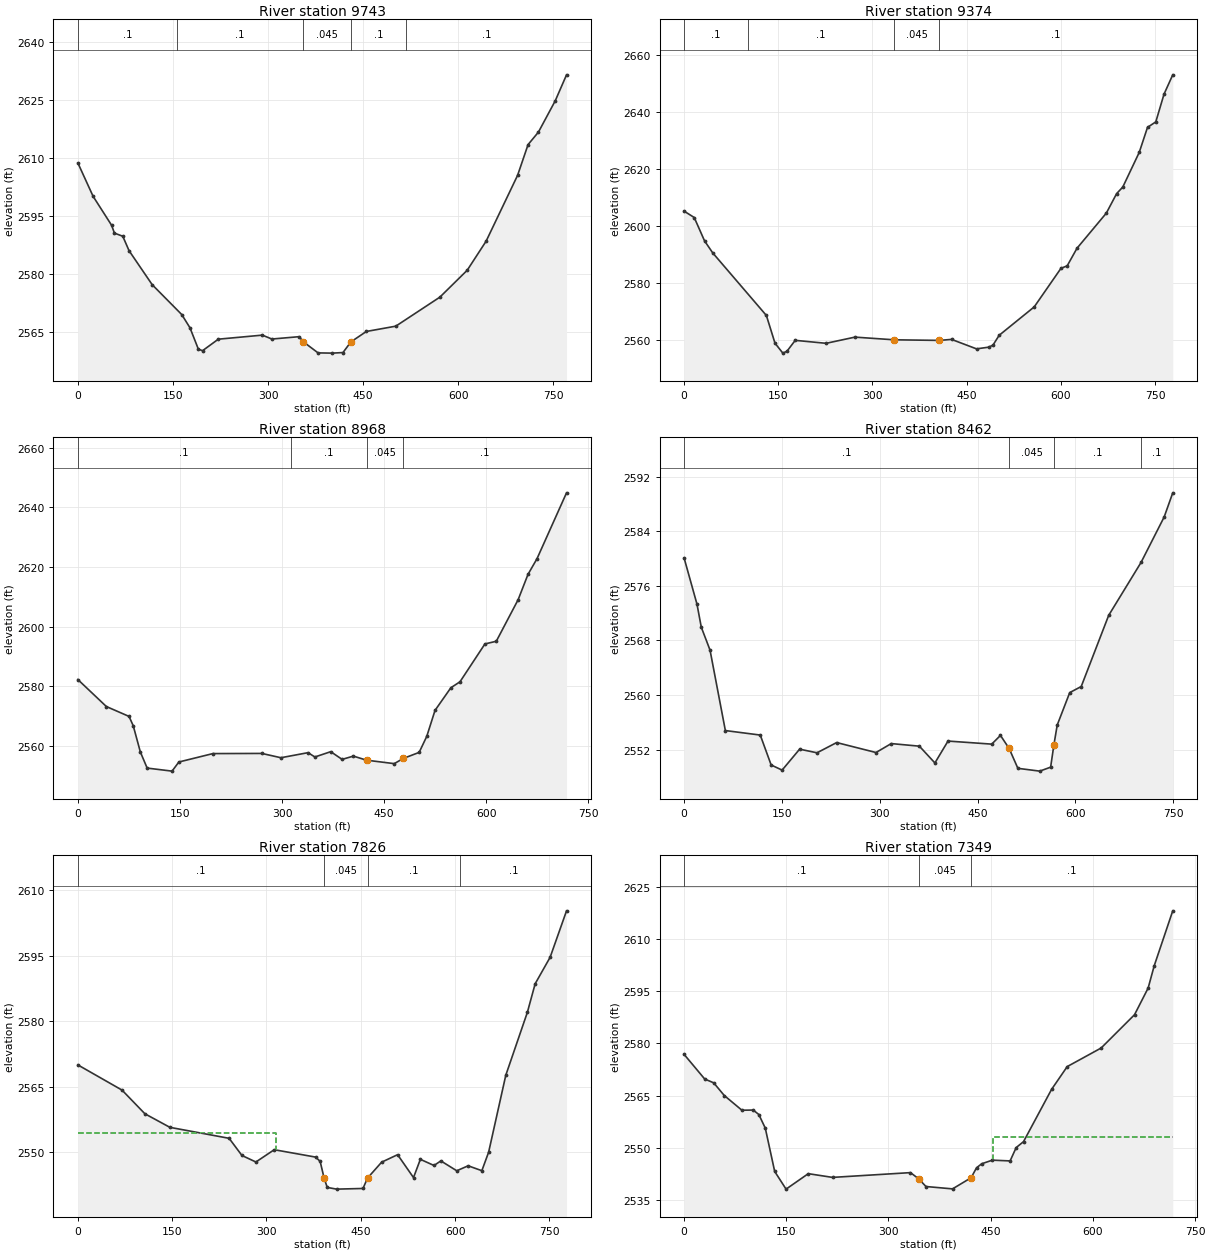
Type RM Length L Ch R = 1 ,9743    ,375.6,369.5,364.6
XS GIS Cut Line= 2
2092226.03833455419112.0587801932092118.74655437419875.600560203
#Sta/Elev= 30
       0 2608.75    24.1 2600.09    53.2 2592.62    57.7 2590.58    70.9 2589.76
    80.8 2586.02   117.3 2577.22   163.9 2569.49   176.9 2566.06   190.2  2560.5
   196.8 2560.14   221.6 2563.11   291.1 2564.16   306.1 2563.15   349.2 2563.76
   355.8 2562.43     379 2559.56   401.7  2559.5   418.3 2559.65   430.8 2562.41
   455.2 2565.11   501.6 2566.48   571.2    2574   614.3 2580.96   644.1 2588.48
   693.8 2605.54   710.3 2613.49   726.7 2616.74   753.2 2624.84     771 2631.56
#Mann= 5 ,-1 , 0
       0      .1       0  155.93      .1       0   355.8    .045       0
   430.8      .1       0  517.72      .1       0
Bank Sta=355.8,430.8
XS Rating Curve= 0 ,0
Exp/Cntr=0.3,0.1

Type RM Length L Ch R = 1 ,9374    ,417.7,405.7,396.8
XS GIS Cut Line= 2
2091798.95487112419103.725463524 2091807.2881878419881.850547701
#Sta/Elev= 30
       0 2605.33    16.2 2603.08    32.6 2594.88    45.7 2590.64   131.1 2568.67
   144.8 2558.94   157.3 2555.45   163.9 2556.12     177 2559.94   226.2  2558.9
   272.1 2561.07   334.5 2560.13   406.5 2559.92     426 2560.27   465.7 2556.95
   485.4 2557.55     492 2558.29   501.8 2561.72   557.6 2571.69   600.2 2585.24
   610.1 2586.11   625.7 2592.28   672.4 2604.62   688.8 2611.46   698.7 2613.81
   724.9    2626     738 2634.75   751.2 2636.67   764.3 2646.41   778.2  2653.2
#Mann= 4 ,-1 , 0
       0      .1       0  102.27      .1       0   334.5    .045       0
   406.5      .1       0
Bank Sta=334.5,406.5
XS Rating Curve= 0 ,0
Exp/Cntr=0.3,0.1

Type RM Length L Ch R = 1 ,8968    ,490.6,506.3,518.9
XS GIS Cut Line= 2
2091392.70502746419232.8921999482091515.62177637419940.183764368
#Sta/Elev= 30
       0  2582.3    41.9 2573.25    75.2 2569.94    81.4 2566.79    91.8 2558.03
   101.8 2552.62   138.4  2551.6   148.4 2554.66   198.4 2557.48   270.3 2557.53
   298.3 2556.09   338.2 2557.79   348.2 2556.34   371.5 2558.12   388.2 2555.54
   404.8 2556.63  424.072555.271   464.8 2554.11   478.1 2555.85   501.4 2557.88
   512.6 2563.27   524.7 2571.96     548 2579.55   561.4 2581.55     598 2594.23
   614.7 2595.13   646.8 2609.06   661.3 2617.55   674.6 2622.84   717.9 2644.88
#Mann= 4 ,-1 , 0
       0      .1       0  312.48      .1       0  424.07    .045       0
   478.1      .1       0
Bank Sta=424.07,478.1
XS Rating Curve= 0 ,0
Exp/Cntr=0.3,0.1

Type RM Length L Ch R = 1 ,8462    ,654,635.9,609.9
XS GIS Cut Line= 2
2091106.24661088419320.3920249492090958.32991195420054.767196611
#Sta/Elev= 30
       0 2580.11    19.8 2573.32    26.4 2569.94    39.8 2566.58    63.3 2554.78
   116.8 2554.12   133.5 2549.73   150.3 2548.98   177.1 2552.05   203.8 2551.52
   233.9 2553.02   294.2 2551.56   317.6 2552.87   360.7 2552.49   384.5 2550.03
   404.6 2553.24   471.6 2552.79     485 2554.07   498.3 2552.15   511.7 2549.24
   545.2 2548.83   561.9 2549.41   566.8 2552.61     572 2555.59   591.2 2560.35
   608.8 2561.24   650.9 2571.68   700.5 2579.44     736 2586.12   749.1 2589.65
#Mann= 4 ,-1 , 0
       0      .1       0   498.3    .045       0   566.8      .1       0
  700.18      .1       0
Bank Sta=498.3,566.8
XS Rating Curve= 0 ,0
Exp/Cntr=0.3,0.1

Type RM Length L Ch R = 1 ,7826    ,480.9,476.8,471.5
XS GIS Cut Line= 2
2090201.03844753419420.3921530252090530.20511204420124.558723703
#Sta/Elev= 30
       0 2570.02    70.3 2564.25   106.6 2558.84   146.4 2555.73   240.6 2553.22
     261 2549.29   283.2  2547.8   312.4 2550.61   378.2 2548.92   385.4 2547.94
   391.8 2544.05   396.7 2541.98   411.5 2541.59   453.5 2541.74   460.9 2544.14
   483.2 2547.76   508.6 2549.47   533.9 2544.23   544.8 2548.41   566.5    2547
   577.4 2548.05   602.7 2545.79   620.8 2546.93   642.6 2545.81   653.4 2550.05
   680.7 2567.66     715 2582.05   727.4 2588.59   751.2 2594.65   777.3 2605.28
#Mann= 4 ,-1 , 0
       0      .1       0   391.8    .045       0   460.9      .1       0
  608.63      .1       0
#XS Ineff= 2 , 0
          315.11 2554.51
Permanent Ineff=
       F       F
Bank Sta=391.8,460.9
XS Rating Curve= 0 ,0
Exp/Cntr=0.3,0.1

Type RM Length L Ch R = 1 ,7349    ,457.2,431,404.4
XS GIS Cut Line= 2
2089757.28835079419709.9755633622090143.74656737 420314.14200595
#Sta/Elev= 30
       0 2576.85    30.3 2569.76    43.5 2568.67      59 2565.03    84.9  2560.8
   101.5 2560.85   109.7 2559.57   119.2 2555.66     133 2543.22   149.7 2538.14
   182.3 2542.58   217.9 2541.51   332.3 2542.88   344.5 2541.07     355 2538.89
     394 2538.21   421.2  2541.4   429.3 2544.28   436.8 2545.42   452.4 2546.46
   478.5 2546.24   487.4 2550.07   498.2 2551.78   539.3 2566.77   562.3 2573.33
   612.1 2578.67   661.1 2588.23   681.1  2595.9     690 2602.29   717.2 2618.07
#Mann= 3 ,-1 , 0
       0      .1       0   344.5    .045       0   421.2      .1       0
#XS Ineff= 2 , 0
                           454.1         2553.04
Permanent Ineff=
       F       F
Bank Sta=344.5,421.2
XS Rating Curve= 0 ,0
Exp/Cntr=0.3,0.1

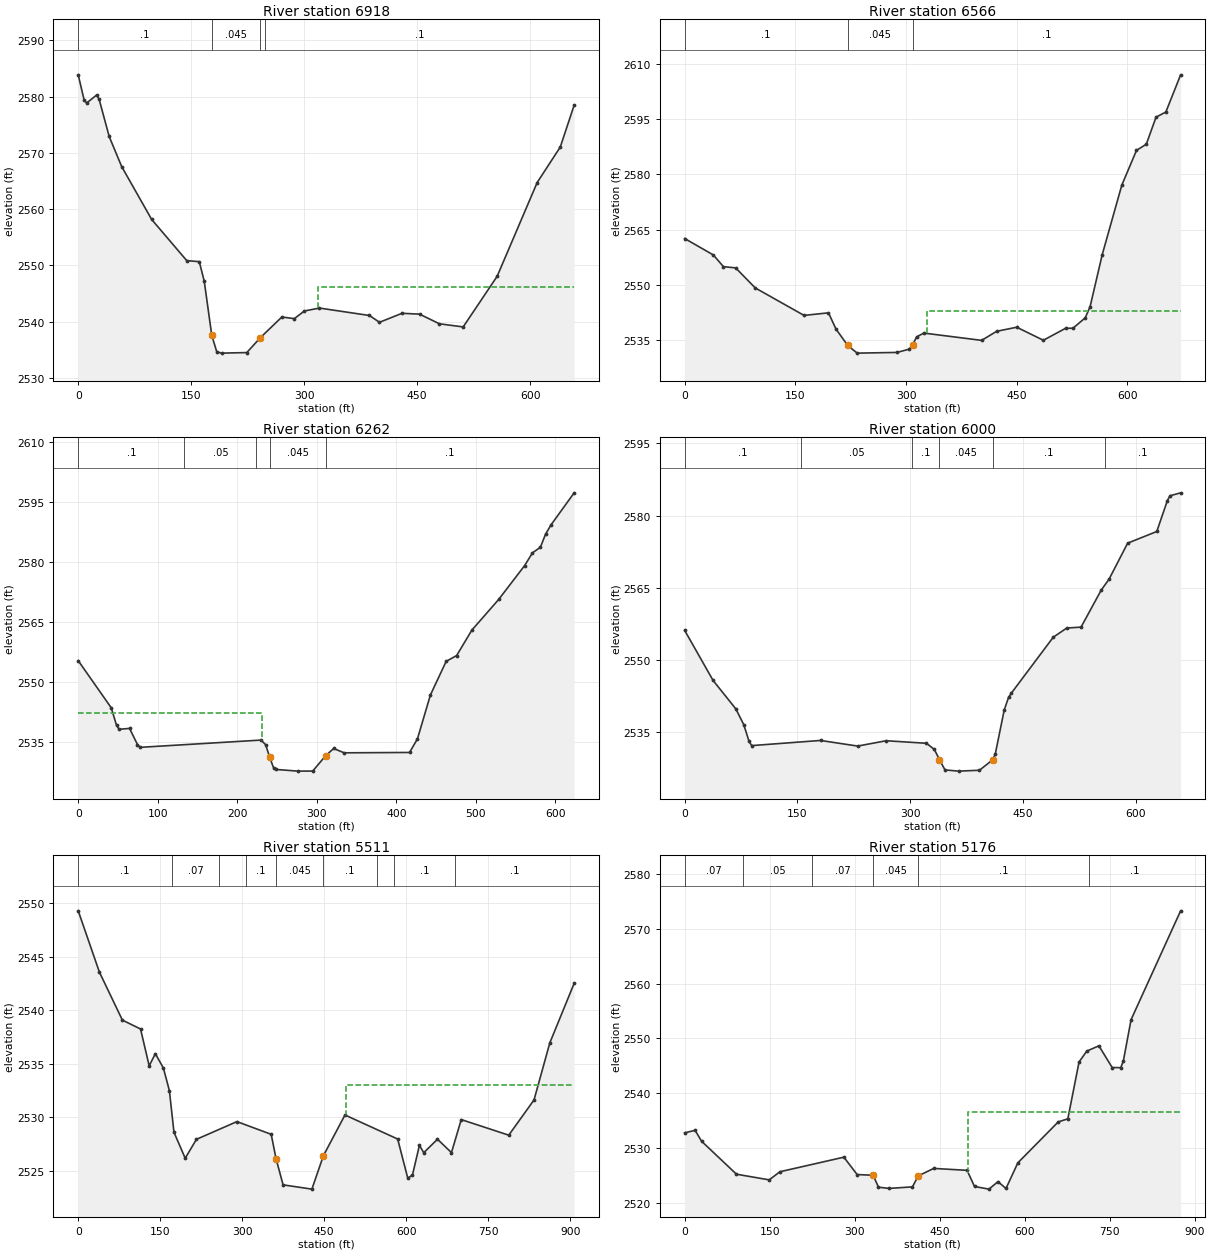
Type RM Length L Ch R = 1 ,6918    ,362.9,352.4,343.8
XS GIS Cut Line= 2
2089413.53838211420231.8505038622090063.53839445  420336.0169622
#Sta/Elev= 30
       0 2583.88     7.8 2579.43    11.2 2578.87    24.4 2580.28    27.8 2579.51
    41.1 2572.92    57.7 2567.57    97.5 2558.17   144.1 2550.85   160.7 2550.67
   167.3 2547.19   177.3 2537.55   183.9 2534.65   190.3 2534.41   223.8 2534.51
   241.8 2537.16   270.3 2540.83   286.9 2540.54   300.2  2541.9   320.2 2542.42
   386.6  2541.1   399.9 2539.89   429.8 2541.49   453.1 2541.34   479.5 2539.62
     511 2539.07   556.1 2548.07   609.2 2564.73   639.9 2571.05   658.3 2578.48
#Mann= 4 ,-1 , 0
       0      .1       0   177.3    .045       0   241.8      .1       0
  247.81      .1       0
#XS Ineff= 2 , 0
                          318.51         2546.21
Permanent Ineff=
       F       F
Bank Sta=177.3,241.8
XS Rating Curve= 0 ,0
Exp/Cntr=0.3,0.1

Type RM Length L Ch R = 1 ,6566    ,300.7,303.8,305.4
XS GIS Cut Line= 2
2089402.08007172 420650.600322532090067.70505279420557.892174616
#Sta/Elev= 30
       0 2562.62    38.9 2558.15    52.5 2554.99    69.1 2554.65    95.6 2549.22
   161.8 2541.76   194.9 2542.46   205.1 2538.04     221 2533.61   233.8 2531.53
   287.7 2531.72   304.3  2532.6   309.1 2533.81   314.2 2535.92   324.1 2536.97
   402.4 2534.99   422.7 2537.44     450 2538.56   486.1 2535.02   516.3 2538.28
   526.2 2538.28   542.8  2541.1   549.4 2544.11   565.9 2558.27   592.4  2577.1
   612.3 2586.52   625.6  2588.2   638.8 2595.54   652.1 2596.93   672.1 2607.02
#Mann= 3 , 0 , 0
       0      .1       0     221    .045       0   309.1      .1       0
#XS Ineff= 2 , 0
                          328.41         2542.86
Permanent Ineff=
       F       F
Bank Sta=221,309.1
XS Rating Curve= 0 ,0
Exp/Cntr=0.3,0.1

Type RM Length L Ch R = 1 ,6262    ,245.4,262.2,277.1
XS GIS Cut Line= 2
2089432.28834462420933.933745369 2090054.1634132420888.100503698
#Sta/Elev= 30
       0  2555.3    41.6 2543.51    48.2 2539.14    51.5 2538.16    64.6 2538.39
    74.5 2534.35    77.8 2533.66   229.9 2535.47   235.7 2534.31   240.7 2531.21
   245.6 2528.57   248.8 2528.14   276.1 2527.72   294.9 2527.74   311.1 2531.56
   321.2 2533.37   334.4 2532.29   416.6 2532.38   426.5 2535.74   442.9 2546.75
   462.7 2555.14   475.8 2556.56     495 2562.93   528.7 2570.58   561.4 2579.05
   571.2 2582.22   581.1  2583.6   587.7 2586.89   594.3 2589.14   623.6  2597.2
#Mann= 5 ,-1 , 0
       0      .1       0  133.47     .05       0  224.01      .1       0
   240.7    .045       0   311.1      .1       0
#XS Ineff= 2 , 0
          231.35 2542.31
Permanent Ineff=
       F       F
Bank Sta=240.7,311.1
XS Rating Curve= 0 ,0
Exp/Cntr=0.3,0.1

Type RM Length L Ch R = 1 ,6000    ,478.4,488.7,497.8
XS GIS Cut Line= 2
2089367.70514047421033.9338734452089982.28822887421274.558720276
#Sta/Elev= 30
       0 2556.12    37.8 2545.71    68.1 2539.79    78.7 2536.49    85.7 2533.02
    89.2 2532.16   180.8 2533.23   230.2 2532.06   268.2 2533.17   321.8 2532.64
   332.3 2531.35   339.1 2529.23   346.4  2527.1   364.5 2526.85   392.3 2527.03
   409.9 2529.21   413.4 2530.44   425.2 2539.53     431 2542.18   434.5 2543.02
   490.5  2554.7   508.5 2556.61   527.5  2556.8   554.2 2564.46   564.9 2566.81
   589.5 2574.26   628.3 2576.69   642.4 2583.13   645.9 2584.12     660 2584.73
#Mann= 6 ,-1 , 0
       0      .1       0  154.61     .05       0  302.23      .1       0
   339.1    .045       0   409.9      .1       0  559.04      .1       0
Bank Sta=339.1,409.9
XS Rating Curve= 0 ,0
Exp/Cntr=0.3,0.1

Type RM Length L Ch R = 1 ,5511    ,330.4,334.9,340.1
XS GIS Cut Line= 2
2089117.70498431421321.4336265332089840.62151745421869.350509703
#Sta/Elev= 30
       0 2549.31    38.7 2543.58    80.8 2539.08     114 2538.25   129.8  2534.8
   141.1 2535.94   155.8 2534.59   166.8 2532.47   175.1 2528.59   195.7 2526.15
   216.2 2527.92   290.3 2529.58     353 2528.39   361.8 2526.12   374.7 2523.66
   427.4 2523.26   448.5 2526.39   487.9  2530.2   584.3 2527.95   602.8 2524.28
   611.4 2524.59   624.1 2527.36     632 2526.67   657.1 2527.93   682.7 2526.68
   700.6 2529.77   787.5 2528.31   833.7 2531.61   862.6 2536.95   907.1 2542.52
#Mann= 9 ,-1 , 0
       0      .1       0  171.83     .07       0  258.07     .05       0
  307.35      .1       0   361.8    .045       0   448.5      .1       0
  546.01     .06       0  578.37      .1       0  689.98      .1       0
#XS Ineff= 2 , 0
                          490.66            2533
Permanent Ineff=
       F       F
Bank Sta=361.8,448.5
XS Rating Curve= 0 ,0
Exp/Cntr=0.3,0.1

Type RM Length L Ch R = 1 ,5176    ,484.8,494.6,513.5
XS GIS Cut Line= 2
2088983.32992497421580.8087639512089608.32998729422193.308851287
#Sta/Elev= 30
       0 2532.76    18.4 2533.22    29.8 2531.23    91.4 2525.21   149.2 2524.18
     168 2525.66   280.9 2528.32   304.3 2525.15   332.5 2525.02     342 2522.84
   360.6 2522.62   401.9  2522.9   412.1  2524.9   439.4 2526.27   498.3 2525.92
   511.4 2522.97   536.9 2522.49   552.8 2523.85     567 2522.61   587.9 2527.29
   659.1 2534.75   676.1 2535.32   695.9 2545.69   709.6 2547.68   730.9 2548.64
   754.3 2544.68   769.4 2544.65     774 2545.84   787.7 2553.42   875.1 2573.27
#Mann= 6 ,-1 , 0
       0     .07       0  103.66     .05       0  225.31     .07       0
   332.5    .045       0   412.1      .1       0  713.73      .1       0
#XS Ineff= 2 , 0
                          500.28         2536.58
Permanent Ineff=
       F       F
Bank Sta=332.5,412.1
XS Rating Curve= 0 ,0
Exp/Cntr=0.3,0.1