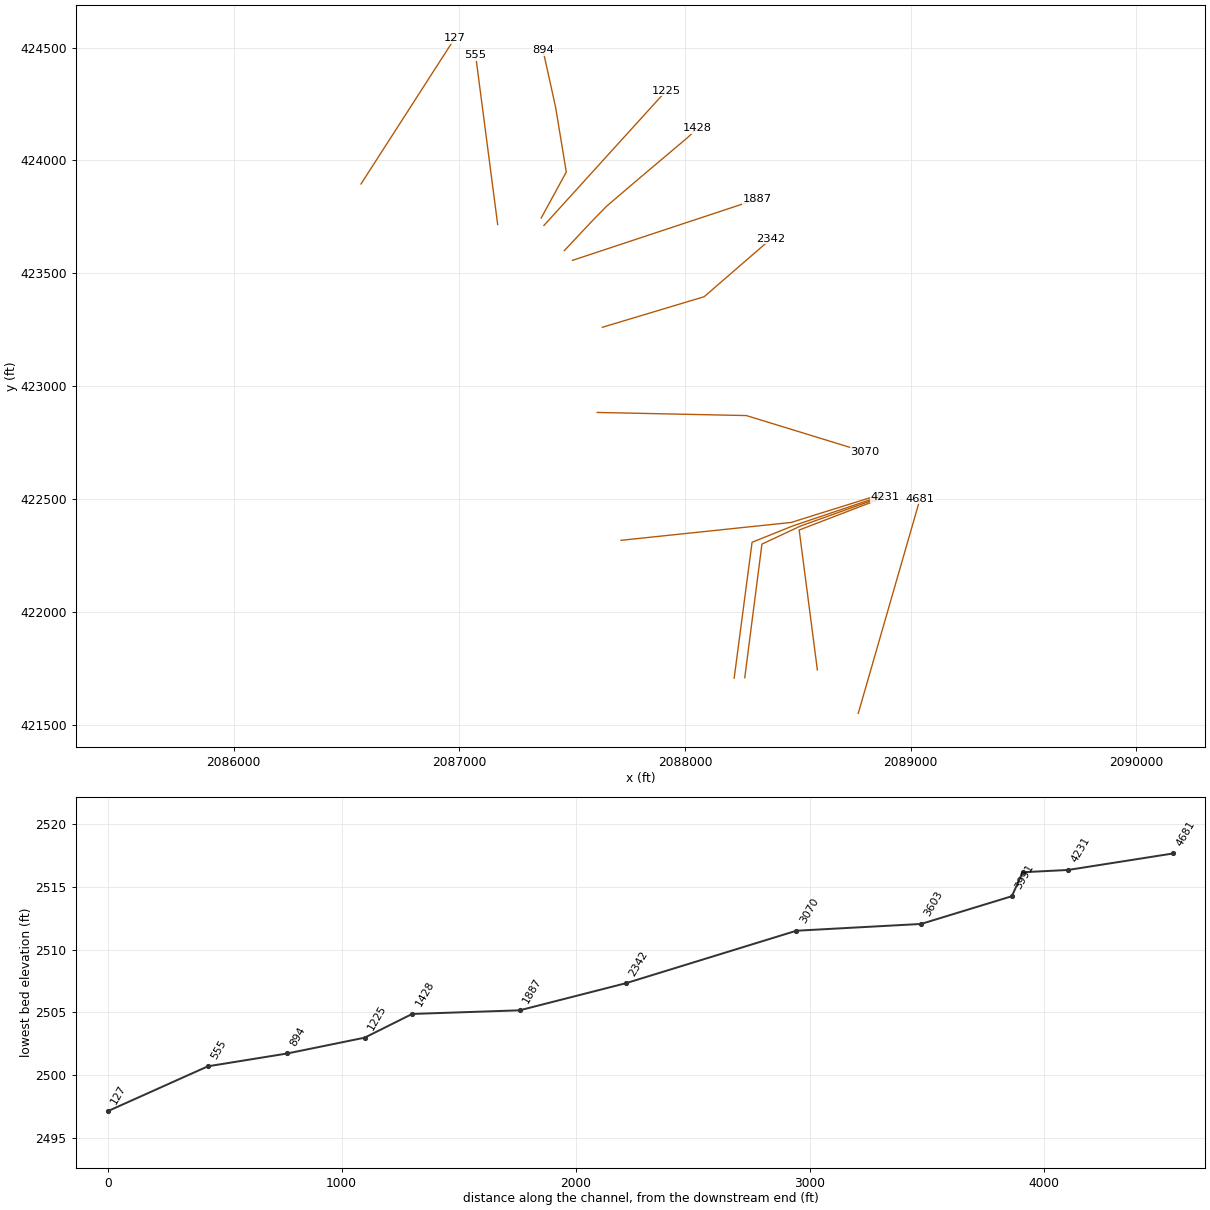
HEC-RAS study LAURELCK4.prj: LAURELCK4

--- LAURELCK4.g01 (geometry) --- (continued)

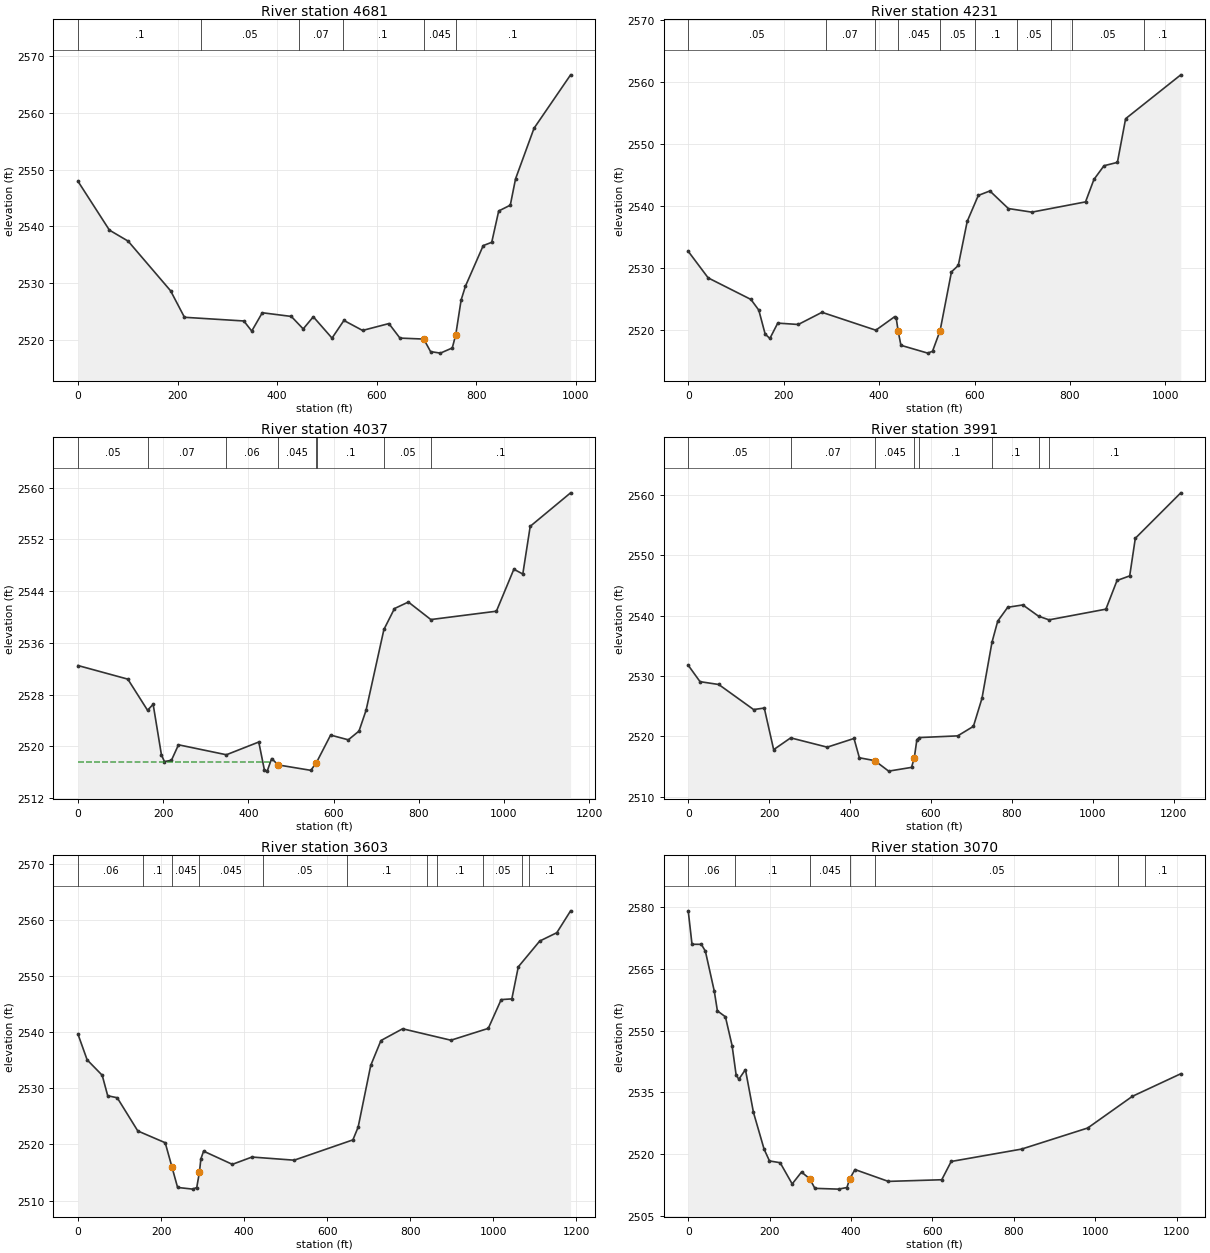
Type RM Length L Ch R = 1 ,4681    ,439.1,450.8,465.9
XS GIS Cut Line= 2
2088767.70502812421549.558826447 2089041.6634697422500.600559533
#Sta/Elev= 30
       0 2547.94      63 2539.35   100.6 2537.41   185.9 2528.66   213.8 2523.98
   333.1 2523.33     349 2521.55   370.2 2524.78   428.5 2524.13   452.4 2521.93
   472.7 2524.07   510.3 2520.31   534.2 2523.42   571.7 2521.66   624.6 2522.87
   646.8 2520.31   694.6 2520.14   708.3 2517.93     728 2517.66   751.9 2518.57
   758.9 2520.89   769.7 2527.03   778.4 2529.47   814.1 2536.62   831.2  2537.2
   845.2 2542.72   868.5 2543.75   879.1  2548.4   916.2 2557.31   989.7 2566.73
#Mann= 6 ,-1 , 0
       0      .1       0  246.65     .05       0  443.23     .07       0
  531.53      .1       0   694.6    .045       0   758.9      .1       0
Bank Sta=694.6,758.9
XS Rating Curve= 0 ,0
Exp/Cntr=0.3,0.1

Type RM Length L Ch R = 1 ,4231    ,205.3,193.7,182.6
XS GIS Cut Line= 3
2088586.45506254 421742.267102452088505.90141788422362.135613367
2088885.76056629 422508.23932378
#Sta/Elev= 30
       0 2532.73    41.8 2528.45   131.4 2524.98   147.9 2523.26   161.2 2519.41
   171.1  2518.7   187.6 2521.17   230.6 2520.95   280.3 2522.91   393.1 2520.03
   432.5  2522.2   435.8 2521.99     440 2519.83   445.7  2517.6   501.9 2516.34
   511.9 2516.64   527.8 2519.97   551.6 2529.42   565.9 2530.45   584.6 2537.55
   607.8 2541.72   632.1 2542.44   670.8 2539.61     720 2539.03   832.5 2540.68
   850.1 2544.29   871.2  2546.5   899.3 2547.04   916.5 2554.07  1032.1 2561.13
#Mann= 10 ,-1 , 0
       0     .05       0   288.8     .07       0  390.37     .06       0
     440    .045       0   527.8     .05       0  600.83      .1       0
  688.38     .05       0  759.95      .1       0  803.37     .05       0
  955.57      .1       0
Bank Sta=440,527.8
XS Rating Curve= 0 ,0
Exp/Cntr=0.5,0.3

Type RM Length L Ch R = 1 ,4037    ,47.8,46,45.3
XS GIS Cut Line= 4
2088264.72779255421707.4376923642088340.78757053422299.732984717
2088513.94493742422380.6476421432088861.02332576422504.677422026
#Sta/Elev= 30
       0 2532.48   116.9 2530.38   163.2 2525.57   176.4 2526.49   195.9 2518.66
   202.9 2517.64   219.4 2517.84   235.9 2520.23   348.4 2518.69   424.5 2520.66
   437.7 2516.33   444.3 2516.16   454.7 2518.11   469.9 2517.12   546.9 2516.28
   559.4 2517.46     561 2517.62   593.2 2521.73   634.8    2521   659.9 2522.35
   676.5 2525.57   718.4 2538.06   743.2 2541.29   775.8  2542.3   828.6 2539.59
   982.6 2540.88  1023.6 2547.37  1044.6 2546.63    1062    2554  1156.9 2559.18
#Mann= 8 ,-1 , 0
       0     .05       0   163.2     .07       0   348.4     .06       0
   469.9    .045       0   559.4     .05       0     561      .1       0
   718.4     .05       0   828.6      .1       0
#XS Ineff= 2 , 0
           449.9  2517.5   579.4          2517.5
Permanent Ineff=
       F       F
Bank Sta=469.9,559.4
XS Rating Curve= 0 ,0
Exp/Cntr(USF)=0,0
Exp/Cntr=0.5,0.3

Type RM Length L Ch R = 1 ,3991    ,431.2,388.1,335
XS GIS Cut Line= 4
2088217.79729125421705.8193992152088297.09365552 422307.82445046
2088478.34248816422380.6476421432088871.58772324 422513.34768032
#Sta/Elev= 30
       0 2531.79    29.2 2529.07    75.5  2528.6   161.6 2524.45     188  2524.7
   211.2 2517.81   253.3 2519.76   343.6 2518.22   409.8 2519.66   423.1 2516.46
     461 2515.99   495.5 2514.25     552 2514.87   558.7  2516.4   565.3 2519.48
   571.7 2519.81   666.1 2520.09     705 2521.67   726.2 2526.32   750.9  2535.6
   765.1  2539.1   789.8 2541.39   827.2 2541.78   866.1 2539.91     892 2539.31
  1032.5 2541.08    1060 2545.83  1091.3 2546.59  1105.2 2552.82  1217.6 2560.35
#Mann= 8 ,-1 , 0
       0     .05       0   253.3     .07       0     461    .045       0
   558.7     .05       0   571.7      .1       0   750.9      .1       0
   866.1     .05       0     892      .1       0
Bank Sta=461,558.7
XS Rating Curve= 0 ,0
Exp/Cntr(USF)=0,0
Exp/Cntr=0.5,0.3

Type RM Length L Ch R = 1 ,3603    ,538.1,532.8,528.3
XS GIS Cut Line= 3
2087716.45483404422316.5727123622088470.62163278422395.739220694
2088878.81602639422523.517180368
#Sta/Elev= 30
       0 2539.63    21.9 2535.09    58.2 2532.34    71.4 2528.69    94.4 2528.33
   143.9 2522.41   209.9 2520.31   226.4 2515.91   239.7 2512.34   276.3 2512.04
   285.8 2512.33   292.4 2515.11   295.7 2517.42   302.3 2518.81   371.5 2516.46
   418.8 2517.76   520.4  2517.2   661.8 2520.82   674.4 2523.09   704.7 2534.09
   729.3 2538.53   781.5 2540.63   897.8 2538.59   987.8  2540.7  1018.8 2545.83
  1044.5 2545.96    1060 2551.67  1111.6 2556.27  1152.8 2557.76    1186 2561.66
#Mann= 11 ,-1 , 0
       0     .06       0  155.62      .1       0   226.4    .045       0
   292.4    .045       0  444.91     .05       0  647.46      .1       0
  840.42     .05       0  864.43      .1       0  975.51     .05       0
 1068.08      .1       0  1086.6      .1       0
Bank Sta=226.4,292.4
XS Rating Curve= 0 ,0
Exp/Cntr=0.3,0.1

Type RM Length L Ch R = 1 ,3070    ,704.1,728.4,737.1
XS GIS Cut Line= 3
2087610.76049164422883.2392299472088271.87170222422869.350478202
2088796.87163645422708.239251867
#Sta/Elev= 30
       0 2579.13     9.3    2571    32.3 2570.99    42.2 2569.31      64 2559.64
    71.7 2554.82    91.4 2553.38   107.8 2546.38   117.6 2539.34   124.2 2538.18
   140.6 2540.54   160.3 2530.15   186.5  2521.2   199.7 2518.35   225.9 2517.92
   255.5 2512.76   278.4 2515.65   298.6 2514.01   311.2 2511.69   369.3  2511.5
     390 2511.89   396.6 2513.93   409.7 2516.26   491.7 2513.38     623 2513.78
   646.2 2518.22   819.2 2521.23   981.6 2526.35  1091.4 2534.05  1210.4 2539.54
#Mann= 7 ,-1 , 0
       0     .06       0  115.48      .1       0   298.6    .045       0
   396.6      .1       0  459.41     .05       0 1055.48      .1       0
 1121.43      .1       0
Bank Sta=298.6,396.6
XS Rating Curve= 0 ,0
Exp/Cntr=0.3,0.1

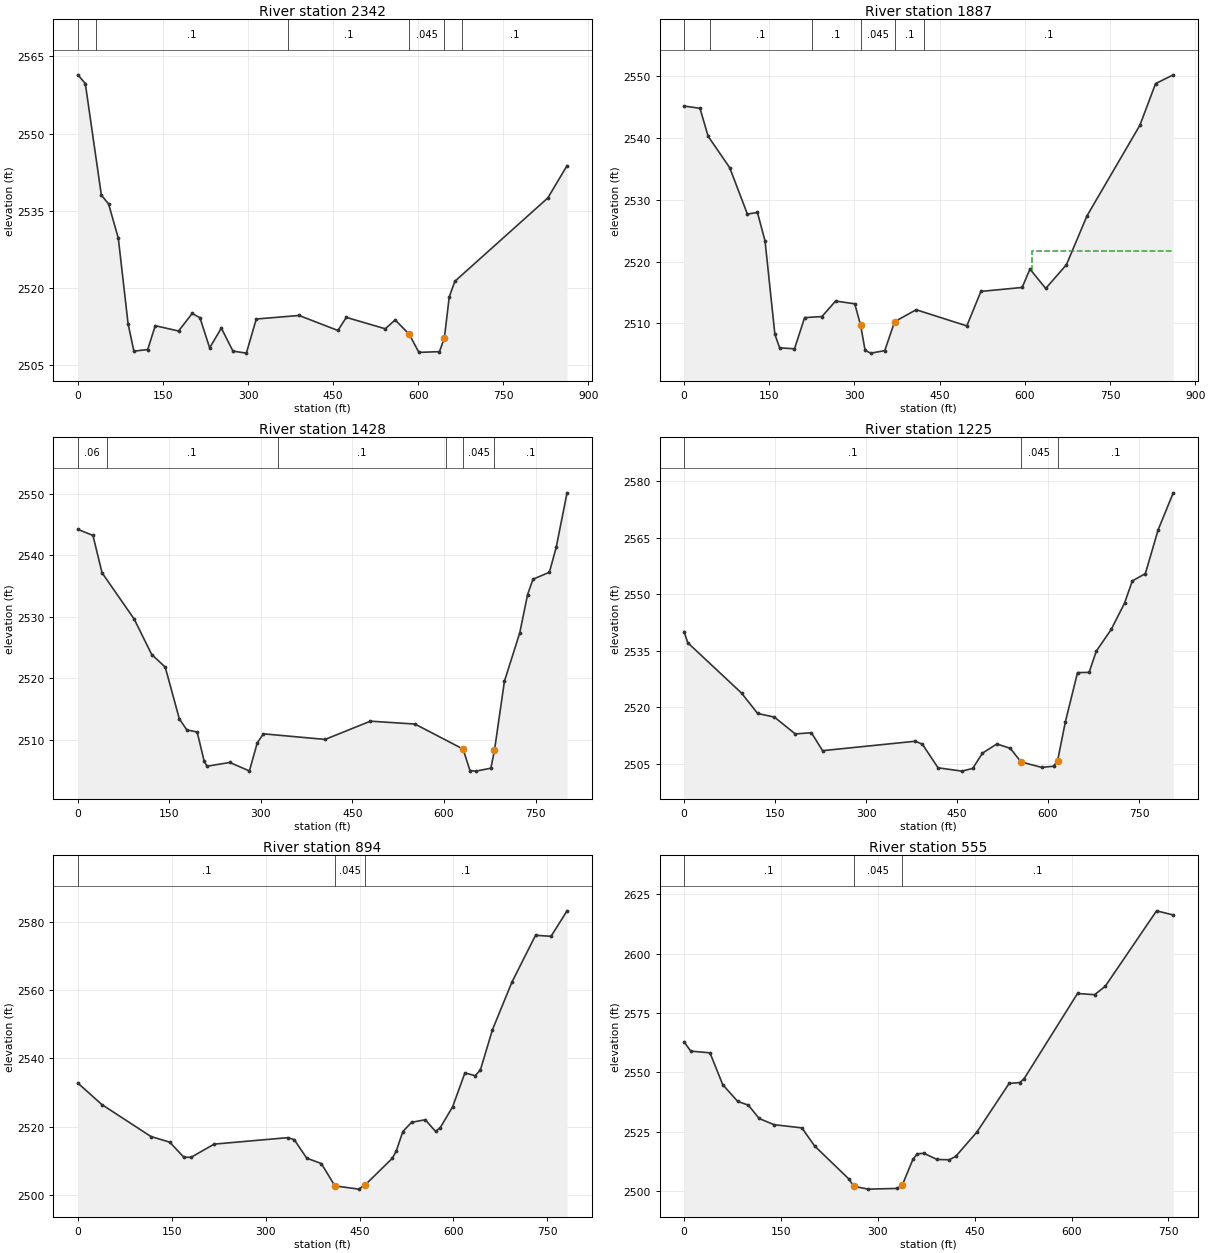
Type RM Length L Ch R = 1 ,2342    ,454.8,454.2,431.8
XS GIS Cut Line= 3
2087633.79292586423260.6699055282088084.83467472 423396.08662945
2088380.66807255423652.336445034
#Sta/Elev= 30
       0 2561.41    13.1 2559.72    41.4 2538.02    54.2  2536.3    71.3 2529.64
    88.5 2513.04    98.7  2507.7   123.1 2508.02   136.4 2512.65   177.5 2511.62
   201.5 2515.03   215.2  2514.2   232.3 2508.34   252.9 2512.18   273.4 2507.71
     297 2507.32   314.5 2513.95   389.9 2514.64   458.4 2511.72   473.2 2514.27
   541.9 2512.05   559.3 2513.78   584.3 2510.96   601.1 2507.46   637.4 2507.61
   646.1 2510.28   654.6 2518.22   664.5 2521.28   828.4 2537.48   862.3 2543.76
#Mann= 6 ,-1 , 0
       0     .06       0    31.4      .1       0  370.67      .1       0
   584.3    .045       0   646.1      .1       0  677.54      .1       0
Bank Sta=584.3,646.1
XS Rating Curve= 0 ,0
Exp/Cntr=0.3,0.1

Type RM Length L Ch R = 1 ,1887    ,451.2,459.4,460.7
XS GIS Cut Line= 2
2087501.15408355423557.1975276922088318.86242187423828.030975536
#Sta/Elev= 30
       0 2545.19      28 2544.83    42.3 2540.31    80.4  2535.2   111.5 2527.69
   129.2 2527.95   142.6 2523.32   159.9 2508.22   168.2 2506.02   194.4 2505.86
   212.3 2510.91   242.8 2511.09   266.8  2513.6   300.6 2513.15     311 2509.64
   318.8 2505.59   328.9 2505.16   353.4 2505.56   370.7 2510.25   408.7 2512.19
   497.9 2509.57   522.7 2515.16   595.3  2515.8   609.1 2518.78   636.8 2515.64
   673.3 2519.48   709.4 2527.38   802.7 2542.09   830.3 2548.83   861.4 2550.25
#Mann= 6 ,-1 , 0
       0     .06       0   46.12      .1       0  224.62      .1       0
     311    .045       0   370.7      .1       0  423.37      .1       0
#XS Ineff= 2 , 0
                          612.34         2521.78
Permanent Ineff=
       F       F
Bank Sta=311,370.7
XS Rating Curve= 0 ,0
Exp/Cntr=0.3,0.1

Type RM Length L Ch R = 1 ,1428    ,203.7,203.1,207.2
XS GIS Cut Line= 6
2087465.04293528423600.2532158642087593.16800714423736.711604372
2087653.58455297 423798.169814782087789.00127688423913.794911608
2088008.79283205424099.2115355282088054.62640178424141.919783443
#Sta/Elev= 30
       0 2544.21    24.7 2543.23    39.6 2537.15    92.3 2529.61   121.1 2523.83
   143.1 2521.81   166.3 2513.37   178.6 2511.57   195.5 2511.24   206.9  2506.5
   211.6 2505.67     249 2506.28   281.1  2504.9   293.9 2509.46   304.1 2510.94
   405.1 2510.03   479.4    2513   552.4 2512.53  631.262508.458   642.5 2504.97
   652.5 2504.87   676.8 2505.35   682.7 2508.28     699  2519.5   724.1 2527.37
   736.9 2533.59   745.8  2536.1   772.7 2537.24   783.8 2541.28   801.6 2550.16
#Mann= 6 ,-1 , 0
       0     .06       0   47.08      .1       0   327.5      .1       0
  602.81      .1       0  631.26    .045       0   682.7      .1       0
Bank Sta=631.26,682.7
XS Rating Curve= 0 ,0
Exp/Cntr=0.3,0.1

Type RM Length L Ch R = 1 ,1225    ,303.9,331,352.5
XS GIS Cut Line= 2
2087374.78790814423711.8577727622087916.75107468424309.002643533
#Sta/Elev= 30
       0 2540.08     6.1 2537.11    94.7 2523.74   121.3 2518.31     149 2517.34
   183.3 2512.87   209.9 2513.19   228.3 2508.42   381.3 2510.93   392.9 2510.13
   418.7 2503.86     458 2502.98   475.8  2503.7   491.9 2507.76   515.6 2510.21
   537.8 2509.04   555.5 2505.42   589.6 2503.97   609.1 2504.28   615.8  2505.8
   628.6 2516.11   648.6 2529.17   667.7 2529.23   679.6  2534.9   704.1 2540.64
   726.3  2547.7   738.9 2553.56   760.4 2555.48   781.5 2567.13   806.4 2576.97
#Mann= 3 ,-1 , 0
       0      .1       0   555.5    .045       0   615.8      .1       0
Bank Sta=555.5,615.8
XS Rating Curve= 0 ,0
Exp/Cntr(USF)=0,0
Exp/Cntr=0.3,0.1

Type RM Length L Ch R = 1 ,894     ,346.1,338.8,336.7
XS GIS Cut Line= 4
2087362.73777555423745.0977593412087473.81398623423948.737478923
2087426.20989594424237.0066923572087370.67179059 424488.25050223
#Sta/Elev= 30
       0 2532.78    38.3 2526.49   116.8 2517.12   146.8 2515.47   169.1 2511.09
   180.6 2511.02   217.7  2514.9   335.6  2516.8   345.6 2516.21   365.6 2510.79
   388.9 2509.21   410.6 2502.67   448.7 2501.72   459.1 2502.98   502.1 2510.71
   508.6 2512.85   519.1 2518.58     533 2521.28     555 2522.04   571.5  2518.6
     579 2519.75   598.7 2525.85   618.3 2535.75   634.8 2534.94   643.1 2536.67
   662.3  2548.4   693.2 2562.26   731.1 2576.05   755.9 2575.76781.4459 2583.22
#Mann= 3 ,-1 , 0
       0      .1       0   410.6    .045       0   459.1      .1       0
Bank Sta=410.6,459.1
XS Rating Curve= 0 ,0
Exp/Cntr(USF)=0,0
Exp/Cntr=0.3,0.1

Type RM Length L Ch R = 1 ,555     ,463.8,428.5,410.2
XS GIS Cut Line= 2
 2087169.6767427 423716.006370832087071.82389043424467.093128767
#Sta/Elev= 30
       0 2562.84    10.3  2558.9    40.1 2558.19    59.9 2544.73    83.1 2537.69
    99.6 2536.11   116.2  2530.5   139.3 2527.88   182.4 2526.53   202.2 2518.89
   255.1    2505   262.9 2501.89   284.9  2500.7   330.3    2501   337.9 2502.42
   354.4 2513.29     361 2515.59   371.3 2515.82   391.7 2513.21   410.6 2513.08
   420.6 2514.49   453.7 2524.88   503.3 2545.27   519.8 2545.66   526.5 2547.27
   609.2 2583.21   635.6  2582.7   652.1 2586.23   731.6 2618.07757.4341 2616.32
#Mann= 3 ,-1 , 0
       0      .1       0   262.9    .045       0   337.9      .1       0
Bank Sta=262.9,337.9
XS Rating Curve= 0 ,0
Exp/Cntr(USF)=0,0
Exp/Cntr=0.3,0.1

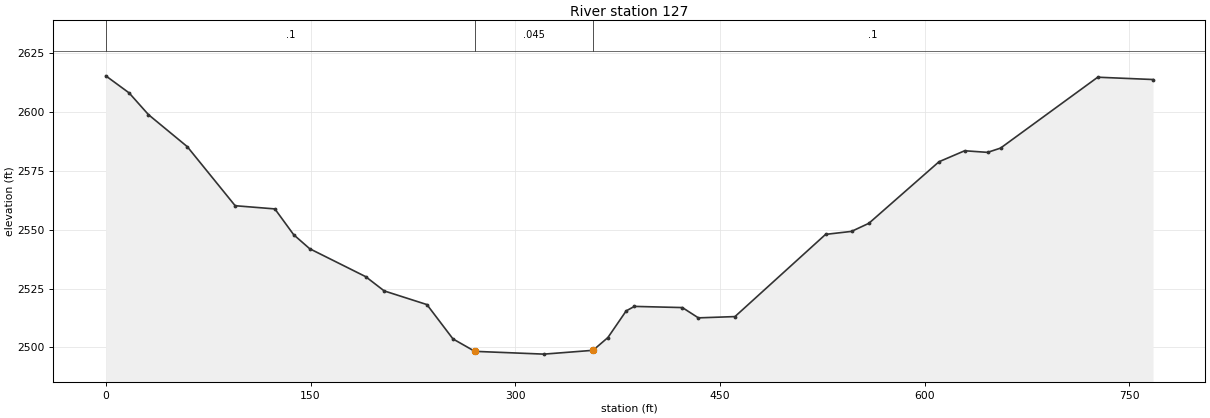
Type RM Length L Ch R = 1 ,127     ,127,127,127
XS GIS Cut Line= 2
2086564.04692732423895.8440452652086979.26038153424541.143935888
#Sta/Elev= 30
       0 2615.37    17.1 2608.11    31.3 2598.86    59.7 2585.28    94.8 2560.18
   123.9 2558.82   137.7 2547.84   149.4 2541.91   190.4 2530.05     204 2523.98
   235.3 2518.17   254.4 2503.58   270.4  2498.3   321.1 2497.12     357 2498.74
   367.9 2504.16   381.3 2515.49   387.3  2517.4   422.5  2516.9   434.2 2512.53
     461 2513.07   527.4    2548   546.4 2549.27   559.1  2552.7   610.5 2578.86
   629.3 2583.53   646.1 2582.85   655.6 2584.66   726.8 2614.78767.3423  2613.8
#Mann= 3 ,-1 , 0
       0      .1       0   270.4    .045       0     357      .1       0
Bank Sta=270.4,357
XS Rating Curve= 0 ,0
Exp/Cntr(USF)=0,0
Exp/Cntr=0.3,0.1
LCMann Table=0

Chan Stop Cuts=-1
Use User Specified Reach Order=0
Composite Channel Slope=5